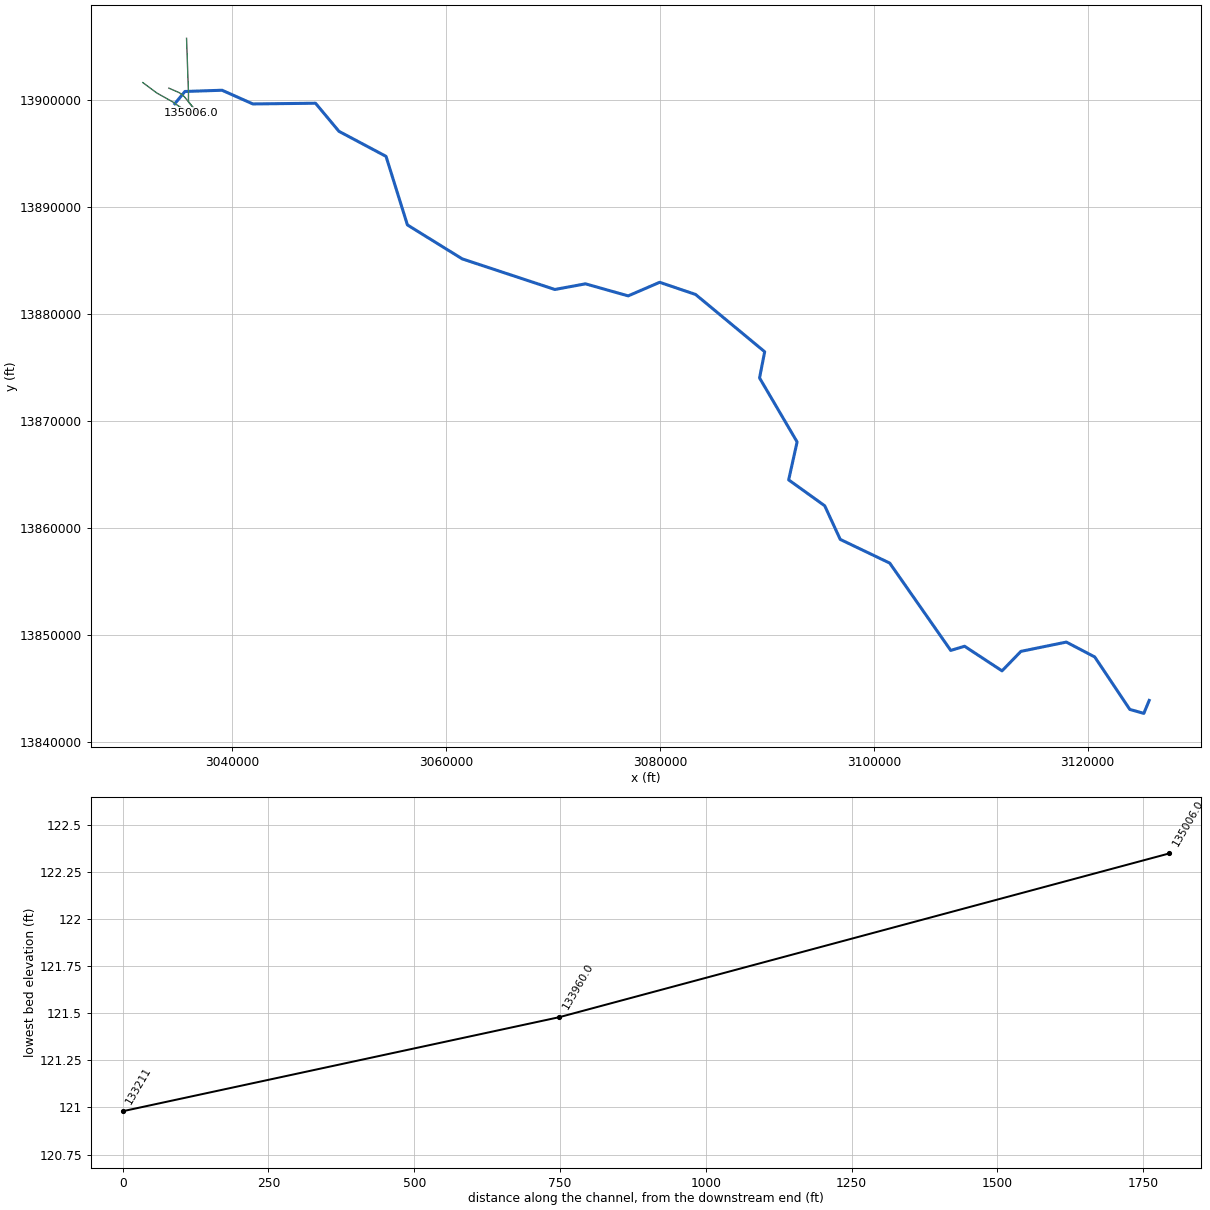
--- E100-00-00.prj (project) ---

Proj Title=E100-00-00
Current Plan=p02
Default Exp/Contr=0.3,0.1
English Units
Geom File=g01
Geom File=g02
Flow File=f01
Flow File=f02
Plan File=p01
Plan File=p02
Y Axis Title=Elevation
X Axis Title(PF)=Main Channel Distance
X Axis Title(XS)=Station
BEGIN DESCRIPTION:
HCFCD Watershed Unit ID: E
M3 Study Identifier: 2014_Effective_E
Engineer: HCFCD
Project Name: Effective FEMA Study for watershed White Oak Bayou (E)
Study Completion Date: [No Data]
FEMA Case Number: 10-06-0969P
FEMA Approval Date: 06/09/2014
Vertical Datum: NAVD 1988
Datum Note: 2001 ADJ
HYDRAULICS
HCFCD Unit No.:  E100-00-00
Hydraulic Program Name: HEC-RAS
Hydraulic Program Version: 4.0.0
Steady Hydraulic Model: Yes
Unsteady Hydraulic Model: No
END DESCRIPTION:
DSS File=dss
DSS Export Rating Curves= 0
DSS Export Rating Curve Sorted= 0
DSS Export Volume Flow Curves= 0
DXF OffsetX= 0
DXF OffsetY= 0
DXF ScaleX= 1
DXF ScaleY= 10

--- E100-00-00.p02 (plan) ---

Plan Title=Effective FW 2014
Program Version=4.00
Short Identifier=Eff FW
Geom File=g02
Flow File=f02
Subcritical Flow
K Sum by GR= 0
Std Step Tol= 0.01
Critical Tol= 0.01
Num of Std Step Trials= 20
Max Error Tol= 0.3
Flow Tol Ratio= 0.001
Split Flow NTrial= 30
Split Flow Tol= 0.02
Split Flow Ratio= 0.02
Log Output Level= 0
Friction Slope Method= 1
Unsteady Friction Slope Method= 2
Unsteady Bridges Friction Slope Method= 1
Parabolic Critical Depth
Global Vel Dist= 0 , 0 , 0
Global Log Level= 0
CheckData=True
Encroach Param=-1 ,0,0, 3
Encroach River=E100-00-00
Encroach Reach=E100-00-00_N034
Encroach Node=135006.0
       1  4974.1  5032.3       1  4974.1  5032.3
Encroach Node=133960.0
       1  4969.3  5032.8       1  4969.3  5032.8
Encroach Node=133211
       1  4969.3  5032.8       1  4969.3  5032.8
Encroach Node=133191
       1  4969.3  5032.8       1  4969.3  5032.8
Encroach Node=133109
       1  4946.4  5046.4       1  4946.4  5046.4
Encroach Node=132955.0
       1  4947.6  5050.5       1  4947.6  5050.5
Encroach Node=132844.0
       1  4947.6  5050.5       1  4947.6  5050.5
Encroach Node=132744.
       1  4946.7  5056.7       1  4946.7  5056.7
Encroach Node=131721.0
       1  4948.1  5044.9       1  4948.1  5044.9
Encroach Node=131453.0
       1 4948.04 5045.54       1 4948.04 5045.54
Encroach Node=131432.0
       1 4948.04 5045.54       1 4948.04 5045.54
Encroach Node=131331.
       1    4940    5060       1    4940    5060
Encroach Node=130861.0
       1  4946.8  5056.5       1  4946.8  5056.5
Encroach Node=129818.0
       1  4940.8    5056       1  4940.8    5056
Encroach Node=128748.
       1  4937.5    5097       1  4937.5    5097
Encroach Node=128646.0
       1  4939.3  5056.2       1  4939.3  5056.2
Encroach Node=128540.0
       1  4939.3  5056.2       1  4939.3  5056.2
Encroach Node=128236.0
       1  4937.6    5059       1  4937.6    5059
Encroach Node=127300.0
       1  4930.1  5049.6       1  4930.1  5049.6
Encroach Node=126183.0
       1  4928.3    5049       1  4928.3    5049
Encroach Node=125563.
       1  4913.4  5073.4       1  4913.4  5073.4
Encroach Node=125461.0
       1  4925.7  5070.7       1  4925.7  5070.7
Encroach Node=125344.0
       1  4925.7  5070.7       1  4925.7  5070.7
Encroach Node=125237.
       1    4934    5074       1    4934    5074
Encroach Node=125059.
       1  4923.3  5053.3       1  4923.3  5053.3
Encroach Node=124956.0
       1 4927.87 5046.97       1 4927.87 5046.97
Encroach Node=124931.0
       1 4927.87 5046.97       1 4927.87 5046.97
Encroach Node=124809.
       1  4919.4  5059.4       1  4919.4  5059.4
Encroach Node=124344.0
       1  4953.2  5072.6       1  4953.2  5072.6
Encroach Node=123541.0
       1  4912.5  5044.7       1  4912.5  5044.7
Encroach Node=122719.
       1  4945.9  5065.9       1  4945.9  5065.9
Encroach Node=122616.0
       1  4953.2    5057       1  4953.2    5057
Encroach Node=122498.0
       1  4953.2    5057       1  4953.2    5057
Encroach Node=122396.
       1    4938    5068       1    4938    5068
Encroach Node=121745.0
       1  4916.4  5041.7       1  4916.4  5041.7
Encroach Node=121010.0
       1  4934.5    5075       1  4934.5    5075
Encroach Node=120253.0
       1    4935    5058       1    4935    5058
Encroach Node=119390.0
       1  4935.9    5066       1  4935.9    5066
Encroach Node=118660.0
       1 4786.12    5078       1 4786.12    5078
Encroach Node=117779.0
       1 4751.43 5079.66       1 4751.43 5079.66
Encroach Node=116759.
       1    4270    5095       1    4300    5140
Encroach Node=116680
       1    4320    5260       1    4315    5270
Encroach Node=116529
       1    4715    5445       1    4665    5440
Encroach Node=116453.
       1    4755    5510       1    4755    5510
Encroach Node=115807.0
       1    4918    5510       1    4918    5510
Encroach Node=114948.0
       1    4819    5472       1    4819    5472
Encroach Node=114246.0
       1    4649    5116       1    4649    5116
Encroach Node=113821.
       1    4679    5094       1    4679    5094
Encroach Node=113668.0
       1    4781    5131       1    4781    5131
Encroach Node=113632.0
       1    4801    5131       1    4801    5131
Encroach Node=113539.
       1    4849    5098       1    4849    5098
Encroach Node=113080.0
       1    4880    5090       1    4880    5090
Encroach Node=112547.0
       1    4921    5119       1    4921    5119
Encroach Node=111983.
       1    4900    5280       1    4900    5280
Encroach Node=111861.0
       1    4905    5520       1    4905    5520
Encroach Node=111799.0
       1    4905    5520       1    4905    5520
Encroach Node=111699.
       1  4905.8    5573       1  4905.8    5573
Encroach Node=111409.0
       1    4916    5595       1    4916    5595
Encroach Node=110813.0
       1    4923    5335       1    4923    5335
Encroach Node=110549.
       1    4915    5264       1    4915    5264
Encroach Node=110454.0
       1    4912    5257       1    4912    5257
Encroach Node=110346.0
       1    4895    5240       1    4895    5240
Encroach Node=110243.
       1    4873    5222       1    4873    5222
Encroach Node=109208.0
       1    4885    5195       1    4885    5195
Encroach Node=108454
       1    4875    5155       1    4875    5155
Encroach Node=108354
       1    4877    5142       1    4877    5133
Encroach Node=108323
       1    4881    5131       1    4881    5131
Encroach Node=108221
       1    4900    5129       1    4900    5128
Encroach Node=107598.0
       1    4855    5071       1  4856.8 5068.75
Encroach Node=106727.0
       1    4848    5067       1  4852.1    5065
Encroach Node=105640.0
       1    4853    5106       1  4864.7    5101
Encroach Node=104527.0
       1    4872  5084.4       1    4872  5084.4
Encroach Node=103364.0
       1    4337 5651.27       1    4337 5651.27
Encroach Node=102317.0
       1    4528 5641.58       1    4528 5641.58
Encroach Node=101430.
       1 4645.79 5742.39       1 4645.79 5742.39
Encroach Node=101325.0
       1    4564    5708       1    4564    5708
Encroach Node=101274.0
       1    4550    5708       1    4555    5708
Encroach Node=101172.
       1    4475    5574       1    4475    5574
Encroach Node=100723.0
       1 4508.47  5232.1       1 4508.47  5232.1
Encroach Node=99963.0
       1    4915    5423       1    4921    5423
Encroach Node=99304.
       1    4780 5332.24       1 4790.59 5332.24
Encroach Node=99202.0
       1    4730    5275       1  4742.9    5275
Encroach Node=99154.0
       1    4715    5257       1  4724.9    5257
Encroach Node=99044.
       1 4625.48 5231.95       1 4625.48 5231.95
Encroach Node=98564.0
       1    4435    5111       1    4435    5111
Encroach Node=97673.
       1 4590.27 5443.46       1 4590.27 5443.46
Encroach Node=97571.0
       1 4576.77    5491       1 4576.77    5491
Encroach Node=97546.0
       1 4576.77    5501       1 4576.77    5501
Encroach Node=97445.
       1 4544.19    5493       1 4544.19    5493
Encroach Node=97054.0
       1    4398    5260       1    4398 5241.49
Encroach Node=96688.
       1  4839.8  5077.3       1  4839.8  5077.3
Encroach Node=96586.0
       1  4877.4  5074.2       1  4877.4  5074.2
Encroach Node=96514.0
       1  4877.4  5074.2       1  4877.4  5074.2
Encroach Node=96459.0
       1  4903.3  5101.1       1  4903.3  5101.1
Encroach Node=96298.0
       1  4903.3  5101.1       1  4903.3  5101.1
Encroach Node=96244.0
       1    4895  5092.7       1    4895  5092.7
Encroach Node=96176.0
       1    4895  5092.7       1    4895  5092.7
Encroach Node=96077.
       1  4909.7 5169.58       1  4909.7 5169.58
Encroach Node=95826.70
       1 4886.67    5192       1 4886.67    5192
Encroach Node=95629.0
       1  4917.5 5203.96       1  4917.5 5203.96
Encroach Node=95449.5
       1 4888.75    5231       1 4888.75    5231
Encroach Node=95294.10
       1 4904.99 5354.48       1 4904.99 5354.48
Encroach Node=95027.60
       1 4785.15    5256       1 4785.15    5256
Encroach Node=94745.39
       1    4682 5282.01       1    4682 5282.01
Encroach Node=94536.70
       1 4594.23    5177       1 4594.23    5177
Encroach Node=94345.79
       1    4568    5085       1    4568    5085
Encroach Node=94197.20
       1 4582.36    5087       1 4582.36    5087
Encroach Node=94064.60
       1 4587.87 5071.68       1 4587.87 5071.68
Encroach Node=93748.70
       1 4645.36    5167       1 4645.36    5167
Encroach Node=93630.
       1    4668    5288       1    4668    5288
Encroach Node=93534.0
       1    4758    5359       1    4758    5359
Encroach Node=93419.0
       1    4870    5359       1    4870    5359
Encroach Node=93320.
       1  4921.3 5261.25       1  4921.3 5261.25
Encroach Node=92851.0
       1    4936 5228.44       1    4936 5228.44
Encroach Node=92147.
       1    4569  5075.9       1    4569  5075.9
Encroach Node=91972.0
       1  4499.1  5385.9       1  4499.1  5385.9
Encroach Node=91923.0
       1  4499.1    5475       1  4499.1    5475
Encroach Node=91823.
       1    4529    5695       1    4529    5695
Encroach Node=91339.0
       1    4631    5820       1    4631    5820
Encroach Node=90490.0
       1    4740    5870       1    4740    5870
Encroach Node=88972.0
       1  4334.2    5722       1  4334.2    5722
Encroach Node=87610.
       1    4612    5882       1    4612    5882
Encroach Node=87508.0
       1    4614    6057       1    4614    6057
Encroach Node=87390.0
       1    4634    6157       1    4634    6157
Encroach Node=87171.
       1    4737    6354       1    4737    6354
Encroach Node=86973.10
       1    4820    6419       1    4820    6419
Encroach Node=86924.79
       1    4783    6383       1    4783    6383
Encroach Node=86535.60
       1    4813    6542       1    4813    6542
Encroach Node=86342.39
       1    4742    6591       1    4742    6591
Encroach Node=86132.20
       1    4496    6645       1    4496    6645
Encroach Node=85832.39
       1    4441    6522       1    4441    6522
Encroach Node=85534.79
       1    4447    6438       1    4447    6438
Encroach Node=85293.70
       1    4506    6541       1    4506    6541
Encroach Node=85091
       1    4631    6732       1    4631    6732
Encroach Node=84932.0
       1    4758    6902       1    4758    6902
Encroach Node=84716.0
       1    4756    7041       1    4756    7041
Encroach Node=84692.0
       1    4756    7056       1    4756    7056
Encroach Node=84548.0
       1    4624    7037       1    4624    7037
Encroach Node=83815.0
       1    4590    7425       1    4590    7425
Encroach Node=82633.0
       1    3700    6610       1    3700    6610
Encroach Node=81638.0
       1 3743.97 5743.04       1 3743.97 5743.04
Encroach Node=80800.0
       1    4075    5670       1    4075    5670
Encroach Node=79748.0
       1    3770    5705       1    3770    5705
Encroach Node=78804.0
       1    3875    5575       1    3875    5575
Encroach Node=77625.0
       1    4543 5881.68       1    4543 5881.68
Encroach Node=77447.0
       1    4522    5651       1    4522    5651
Encroach Node=77436.0
       1    4522    5646       1    4522    5646
Encroach Node=77333.
       1  4424.9 5505.46       1  4424.9 5505.46
Encroach Node=77129.0
       1    4430 5609.63       1 4452.16 5609.63
Encroach Node=76222.0
       1    4770 5387.81       1 4770.42 5387.81
Encroach Node=76041.0
       1    4908  5079.7       1    4908  5079.7
Encroach Node=75927.0
       1    4908  5079.7       1    4908  5079.7
Encroach Node=75698.0
       1  4920.1  5086.7       1  4920.1  5086.7
Encroach Node=75102.0
       1 4442.45  5078.7       1 4442.45  5078.7
Encroach Node=74115.0
       1 3823.11  5086.6       1 3823.11  5086.6
Encroach Node=73083.0
       1  4911.5  5075.7       1  4911.5  5075.7
Encroach Node=72999.0
       1  4908.6  5074.1       1  4908.6  5074.1
Encroach Node=72965.0
       1  4908.6  5074.1       1  4908.6  5074.1
Encroach Node=72931.0
       1  4917.7    5079       1  4917.7    5079
Encroach Node=72908.0
       1  4917.7    5079       1  4917.7    5079
Encroach Node=72828.0
       1  4916.2 5593.37       1  4916.2 5593.37
Encroach Node=71493.0
       1    4770 6429.42       1    4770 6429.42
Encroach Node=70642.
       1    3940    5767       1    3940    5767
Encroach Node=70472.0
       1 3874.85    5635       1 3874.85    5635
Encroach Node=70450.0
       1 3874.85    5635       1 3874.85    5635
Encroach Node=70347.0
       1 4122.71 5616.26       1 4122.71 5616.26
Encroach Node=70266.0
       1 4122.71 5616.26       1 4122.71 5616.26
Encroach Node=70166.
       1 4037.05 5615.94       1 4037.05 5615.94
Encroach Node=69408.0
       1 4156.01    5401       1 4156.01    5401
Encroach Node=68633.
       1    4221    5205       1    4221    5205
Encroach Node=68533.0
       1    4260    5143       1    4260    5143
Encroach Node=68503.0
       1    4311    5170       1    4311    5170
Encroach Node=68398.
       1    4210  5102.8       1    4210  5102.8
Encroach Node=67624.0
       1 4193.15 5220.18       1 4193.15 5220.18
Encroach Node=67364.0
       1 4054.38 5229.76       1 4054.38 5229.76
Encroach Node=67246.0
       1 4054.38 5229.76       1 4054.38 5229.76
Encroach Node=67095.
       1 4102.93  5105.9       1 4102.93  5105.9
Encroach Node=66832.0
       1    4171 5079.38       1    4171 5079.38
Encroach Node=66806.0
       1    4162 5079.38       1    4162 5079.38
Encroach Node=66695.0
       1    4118  5068.5       1    4118  5068.5
Encroach Node=66585.0
       1    4118  5068.5       1    4118  5068.5
Encroach Node=66480.
       1    4170  5106.5       1    4170  5106.5
Encroach Node=65878.0
       1    4239  5081.6       1    4239  5081.6
Encroach Node=65650.
       1 4548.07  5111.9       1 4548.07  5111.9
Encroach Node=65504.0
       1    4000 4574.95       1    4000 4574.95
Encroach Node=65425.0
       1    4002    4603       1    4002    4603
Encroach Node=65422.0
       1    4189 4545.76       1    4189 4545.76
Encroach Node=65401.0
       1    4214 4545.76       1    4214 4545.76
Encroach Node=65268.
       1    4850  5100.8       1    4850  5100.8
Encroach Node=65068.0
       1  4914.2  5086.3       1  4914.2  5086.3
Encroach Node=63780.0
       1    4900  5088.7       1    4900  5088.7
Encroach Node=62890.0
       1    4632  5085.4       1    4632  5085.4
Encroach Node=62522
       1 4881.67    5146       1 4881.67    5146
Encroach Node=61936.0
       1  4909.9    5463       1  4909.9    5463
Encroach Node=61125
       1    4563 5102.96       1    4563 5102.96
Encroach Node=60801
       1    4316  5085.4       1    4316  5085.4
Encroach Node=60338
       1    4274 5127.18       1    4274 5127.18
Encroach Node=59972.0
       1    4398    5224       1    4398    5224
Encroach Node=59440
       1 4810.72    5111       1 4810.72    5111
Encroach Node=58797.0
       1    4358  5080.3       1    4358  5080.3
Encroach Node=58544
       1    4425 5089.04       1    4425 5089.04
Encroach Node=58305
       1    4522    5250       1    4522    5250
Encroach Node=57991
       1    4805    5300       1    4805    5300
Encroach Node=57918.0
       1    4879    5296       1    4879    5296
Encroach Node=57015.
       1    4479    5335       1    4479    5335
Encroach Node=56811.0
       1    3080    3845       1    3080    3845
Encroach Node=56621.0
       1    3095    3845       1    3095    3845
Encroach Node=56486.
       1    4450    5127       1    4450    5127
Encroach Node=56239.0
       1    4500    5105       1    4500    5105
Encroach Node=56231.0
       1    4500    5110       1    4500    5110
Encroach Node=55757.0
       1    4551  5090.2       1    4551  5090.2
Encroach Node=55190.
       1    4593  5101.2       1    4593  5101.2
Encroach Node=55112.0
       1    4568    5107       1    4568    5107
Encroach Node=55059.0
       1    4563    5117       1    4563    5117
Encroach Node=54895.0
       1  4535.5 5125.34       1  4535.5 5125.34
Encroach Node=54667.0
       1 4516.82  5091.9       1 4516.82  5091.9
Encroach Node=54545.0
       1    4526  5091.9       1    4526  5091.9
Encroach Node=54398.
       1 4610.75  5106.7       1 4610.75  5106.7
Encroach Node=54053.0
       1    4615  5091.9       1    4615  5091.9
Encroach Node=53766.
       1    4704  5106.9       1    4704  5106.9
Encroach Node=53664.0
       1    4740    5140       1    4740    5140
Encroach Node=53642.0
       1    4740    5140       1    4740    5140
Encroach Node=53459.0
       1    4637    5225       1    4637    5225
Encroach Node=53282.0
       1    4722    5325       1    4722    5325
Encroach Node=53116.
       1    4753    5268       1    4753    5268
Encroach Node=52833.
       1    4682    5330       1    4682    5330
Encroach Node=52760.0
       1    4610    5350       1    4610    5350
Encroach Node=52722.0
       1    4570    5350       1    4570    5350
Encroach Node=52589.0
       1    4565    5400       1    4565    5400
Encroach Node=51777.0
       1  4906.3 5643.31       1  4906.3 5643.31
Encroach Node=51021.
       1  4893.2    5664       1  4893.2    5664
Encroach Node=50921.0
       1  4896.4    5665       1  4896.4    5665
Encroach Node=50808.0
       1  4896.4 5671.65       1  4896.4 5671.65
Encroach Node=50694.
       1    4880    5680       1    4880    5680
Encroach Node=49824.0
       1    4400    5200       1    4400    5200
Encroach Node=49564.
       1    4363    5199       1    4363    5199
Encroach Node=49457.0
       1    4342    5213       1    4342    5213
Encroach Node=49437.0
       1    4320    5200       1    4320    5200
Encroach Node=49281.
       1 4322.19    5124       1 4322.19    5124
Encroach Node=48942.0
       1    4370  5102.2       1    4370  5102.2
Encroach Node=47857.0
       1    4494  5096.2       1    4494  5096.2
Encroach Node=46827.0
       1 4525.26  5100.7       1 4525.26  5100.7
Encroach Node=46096.0
       1    4658 5191.68       1    4658 5191.68
Encroach Node=45120.
       1 4879.67 5179.83       1 4879.67 5179.83
Encroach Node=44983.0
       1 4883.92  5096.2       1 4883.92  5096.2
Encroach Node=44945.0
       1 4883.92    5101       1 4883.92    5101
Encroach Node=44711.0
       1    4820    5200       1    4820    5200
Encroach Node=44688.0
       1    4820    5220       1    4820    5220
Encroach Node=44556.
       1    4815    5300       1    4815    5300
Encroach Node=44372.0
       1    4800    5250       1    4800    5250
Encroach Node=43626.
       1    4400    5550       1    4400    5550
Encroach Node=43420.0
       1    3400    4560       1    3400    4560
Encroach Node=43276.0
       1    3400    4630       1    3400    4630
Encroach Node=42932.
       1    4480    5755       1    4480    5755
Encroach Node=42650.0
       1    4475    5750       1    4475    5750
Encroach Node=42555.0
       1    4465    5695       1    4465    5695
Encroach Node=42356.
       1    4460    5505       1    4460    5505
Encroach Node=41337.0
       1    4642    5533       1    4642    5533
Encroach Node=40384.0
       1    4580    5300       1    4580    5300
Encroach Node=39567.
       1    4630    5130       1    4630    5130
Encroach Node=39419.0
       1  4236.9 4675.16       1  4236.9 4675.16
Encroach Node=39017.0
       1  4236.9 4675.16       1  4236.9 4675.16
Encroach Node=38877.
       1    4732    5149       1    4732    5149
Encroach Node=37857.0
       1    4850    5231       1    4850    5231
Encroach Node=36870.0
       1    4850    5216       1    4850    5216
Encroach Node=36505.
       1    4800    5150       1    4800    5150
Encroach Node=36318.0
       1    4200    4550       1    4200    4550
Encroach Node=36296.0
       1    4200    4550       1    4200    4550
Encroach Node=36134.
       1 4750.58  5114.1       1 4750.58  5114.1
Encroach Node=35718.0
       1    4700    5150       1    4700    5150
Encroach Node=35158.
       1 4549.86    5146       1 4549.86    5146
Encroach Node=35006.0
       1    4421    5176       1    4421    5176
Encroach Node=34895.0
       1    4396  5181.5       1    4396  5181.5
Encroach Node=34645.
       1    4500  5099.2       1    4500  5099.2
Encroach Node=34206.0
       1 4443.25  5112.1       1 4443.25  5112.1
Encroach Node=33962.58
       1    4078 5135.51       1    4078 5135.51
Encroach Node=33909.08
       1 4047.05 5135.52       1 4047.05 5135.52
Encroach Node=33770.
       1    3934  5119.9       1    3934  5119.9
Encroach Node=33681.0
       1    3862  5103.2       1    3862  5103.2
Encroach Node=33610.0
       1    3832  5103.2       1    3832  5103.2
Encroach Node=33357.
       1    3865  5140.5       1    3865  5140.5
Encroach Node=32570.0
       1 4225.53    5113       1 4225.53    5113
Encroach Node=31583.0
       1 4411.99    5230       1 4411.99    5230
Encroach Node=30779.0
       1    4662    5303       1    4662    5303
Encroach Node=29659.
       1    4554    5288       1    4554    5288
Encroach Node=29368.0
       1    2790    3385       1    2790    3360
Encroach Node=29203.0
       1    2785    3385       1    2785    3360
Encroach Node=28775.
       1    4595 5404.21       1    4595 5404.21
Encroach Node=28375.0
       1    4885    5700       1    4885 5669.36
Encroach Node=28330.0
       1    4886    5714       1    4886    5674
Encroach Node=28190.0
       1    4850    5733       1    4900    5688
Encroach Node=28113.0
       1    4850    5718       1    4900    5683
Encroach Node=27982.
       1    4865    5642       1  4888.4    5602
Encroach Node=27429.0
       1    4875    5135       1  4872.9    5135
Encroach Node=26598.
       1  4875.1    5135       1  4875.1  5125.1
Encroach Node=26498.0
       1  4888.9  5129.7       1  4888.9  5129.7
Encroach Node=26366.0
       1  4888.9  5129.7       1  4888.9  5129.7
Encroach Node=26307.3
       1 4710.33 4967.64       1 4710.33 4967.64
Encroach Node=26225
       1 4823.12 5087.08       1 4823.12 5087.08
Encroach Node=26140.
       1  4883.6  5113.6       1  4883.6  5113.6
Encroach Node=25536.0
       1  4888.4  5121.8       1  4888.4  5121.8
Encroach Node=25132.
       1    4880  5107.3       1    4880  5107.3
Encroach Node=24817.0
       1    4853  5098.2       1    4853  5098.2
Encroach Node=24758.0
       1    4853  5098.2       1    4853  5098.2
Encroach Node=24636.
       1    4850  5134.6       1    4850  5134.6
Encroach Node=23934.0
       1  4826.1    5133       1  4826.1    5133
Encroach Node=23550.0
       1 2551.63    2940       1 2551.63    2940
Encroach Node=23444.0
       1 2551.63    2935       1 2551.63    2935
Encroach Node=23180.
       1    4735    5265       1    4735    5265
Encroach Node=22983.
       1    4725    5225       1    4725    5225
Encroach Node=22834.0
       1    4724    5280       1    4724    5280
Encroach Node=22758.0
       1    4750    5280       1    4750    5280
Encroach Node=22610.
       1    4775    5250       1    4775    5250
Encroach Node=22224.0
       1    4800  5371.4       1    4800  5371.4
Encroach Node=21444.0
       1    4670  5257.2       1    4670  5257.2
Encroach Node=20746.0
       1  4879.7  5211.4       1  4879.7  5211.4
Encroach Node=20644.0
       1 4893.59    5176       1 4893.59    5176
Encroach Node=20622.0
       1 4893.59    5166       1 4893.59    5166
Encroach Node=20521.
       1 4898.42  5097.1       1 4898.42  5097.1
Encroach Node=19917.0
       1    4898    5125       1    4898    5125
Encroach Node=19463.0
       1    4853 5139.37       1    4853 5139.37
Encroach Node=18377.
       1    4750    5200       1    4750    5200
Encroach Node=18234.0
       1    3697 4139.11       1    3697 4139.11
Encroach Node=18199.0
       1    3679 4139.11       1    3679 4139.11
Encroach Node=18176.0
       1    3655    4144       1    3655    4144
Encroach Node=18082.0
       1    3576 4099.31       1    3576 4099.31
Encroach Node=17905.
       1    4590    5120       1    4590    5120
Encroach Node=17756.0
       1    4610    5161       1    4610    5161
Encroach Node=17597.0
       1    4710    5171       1    4710    5171
Encroach Node=17318.
       1  4858.3  5128.3       1  4858.3  5128.3
Encroach Node=16831.0
       1    4529  5164.2       1    4529  5164.2
Encroach Node=15795.0
       1  4889.6  5368.6       1  4889.6  5368.6
Encroach Node=15278.
       1    4840  5156.3       1    4840  5156.3
Encroach Node=14977.0
       1    3346    3660       1    3346    3660
Encroach Node=14897.0
       1 3365.55    3660       1 3365.55    3660
Encroach Node=14590.0
       1  4892.2    5255       1  4892.2    5255
Encroach Node=14532.0
       1  4892.2    5305       1  4892.2    5305
Encroach Node=14354.0
       1    4836    5410       1    4836    5410
Encroach Node=13924.0
       1  4871.4    5730       1  4871.4    5730
Encroach Node=13898.0
       1  4853.4    5720       1  4853.4    5720
Encroach Node=13494.
       1  4838.6    5580       1  4838.6    5580
Encroach Node=13220.0
       1 4828.65    5460       1 4828.65    5460
Encroach Node=13143.0
       1  4829.6    5460       1  4829.6    5460
Encroach Node=12698.
       1  4844.3  5254.3       1  4844.3  5254.3
Encroach Node=12066.0
       1  4795.6  5319.4       1  4795.6  5319.4
Encroach Node=11546.0
       1 4772.48  5379.1       1 4772.48  5379.1
Encroach Node=11021.
       1 4772.07  5255.8       1 4772.07  5255.8
Encroach Node=10908.0
       1    4670  5221.8       1    4670  5221.8
Encroach Node=10804.0
       1    4675  5221.8       1    4675  5221.8
Encroach Node=10643.
       1    4767  5175.2       1    4767  5175.2
Encroach Node=9779.0
       1    4715  5274.3       1    4715  5274.3
Encroach Node=8532.0
       1    4517  5358.4       1    4517  5358.4
Encroach Node=8140.
       1 4402.88    5345       1 4402.88    5345
Encroach Node=7649.0
       1    4390    5160       1    4390    5160
Encroach Node=7568.0
       1    4415    5160       1    4415    5160
Encroach Node=7546.0
       1    4410    5155       1    4410    5155
Encroach Node=7529.0
       1    4410    5155       1    4410    5155
Encroach Node=7353.
       1  4486.2  5172.9       1  4486.2  5172.9
Encroach Node=6975.0
       1    3465 4172.26       1    3465 4172.26
Encroach Node=6898.0
       1    3465 4172.26       1    3465 4172.26
Encroach Node=6775.
       1  4487.7  5163.6       1  4487.7  5163.6
Encroach Node=6473.0
       1    4662    5244       1    4662    5244
Encroach Node=6423.0
       1    4670    5244       1    4670    5244
Encroach Node=6174.0
       1 3930.35    4770       1 3930.35    4770
Encroach Node=6068.0
       1 3930.35    4770       1 3930.35    4770
Encroach Node=5525.0
       1  4748.8    5440       1  4748.8    5440
Encroach Node=4994.0
       1    4653 5306.09       1    4653 5306.09
Encroach Node=4961.0
       1    4635 5306.09       1    4635 5306.09
Encroach Node=4812.0
       1  4617.7  5207.7       1  4617.7  5207.7
Encroach Node=4687.0
       1  4617.7  5207.7       1  4617.7  5207.7
Encroach Node=4407.
       1 4784.03 5367.76       1 4784.03 5367.76
Encroach Node=4014.0
       1    4645 5329.05       1    4645 5329.05
Encroach Node=3976.0
       1    4645 5329.05       1    4645 5329.05
Encroach Node=3681.
       1  4728.5 5271.62       1  4728.5 5271.62
Encroach Node=3585.0
       1  4720.6 5268.19       1  4720.6 5268.19
Encroach Node=2298.0
       1 4597.16 5208.46       1 4597.16 5208.46
Encroach Node=1580.
       1  4830.5    5900       1  4830.5    5900
Encroach Node=1353.0
       1    4455  5795.3       1    4455  5795.3
Encroach Node=1319.0
       1 4465.68    5845       1 4465.68    5845
Encroach Node=984.0
       1  4817.3    6303       1  4817.3    6303
Encroach Node=851.0
       1  4817.3    6357       1  4817.3    6357
Encroach Node=654.0
       1  4830.9  6357.7       1  4830.9  6357.7
Encroach Node=400.0
       1  4876.4 6327.13       1  4876.4 6327.13
Encroach Node=365.0
       1  4876.4 6327.13       1  4876.4 6327.13
Encroach Node=210.0
       1    4923  6249.5       1    4923  6249.5
Encroach Node=173.0
       1    4923  6249.5       1    4923  6249.5
BEGIN DESCRIPTION:
FEMA Effective Floodway June 2014
END DESCRIPTION:
Computation Interval=1HOUR
Output Interval=1HOUR
Run HTab= 0
Run UNet= 0
Run PostProcess= 0
Run WQNet= 0
UNET Theta= 1
UNET Theta Warmup= 1
UNET ZTol= 0.02
UNET ZSATol= 0.1
UNET MxIter= 20
UNET MaxInSteps= 20
UNET DtIC= 0
UNET DtMin= 0
UNET MaxCRTS= 20
UNET WFStab= 2
UNET SFStab= 1
UNET WFX= 1
UNET SFX= 1
UNET DSS MLevel= 4
UNET DZMax Abort= 100
UNET Convert EG Bridges=-1
UNET Use Existing IB Tables=-1
UNET Froude Reduction=False
UNET Froude Limit= 1
UNET Froude Power= 10
UNET Time Slicing=0,0, 5
Instantaneous Interval=1HOUR
DSS File=dss
Write IC File= 0
IC Time=0,,
Echo Input=False
Echo Output=False
Write Detailed= 0
Detailed Automatic Start=False, 10
WQ ULTIMATE=-1
WQ Max Comp Step=1HOUR
WQ Output Interval=15MIN
WQ Output Selected Increments= 0
WQ Output face flow=0
WQ Output face velocity=0
WQ Output face area=0
WQ Output face dispersion=0
WQ Output cell volume=0
WQ Output cell surface area=0
WQ Output cell continuity=0
WQ Output face conc=0
WQ Output face dconc_dx=0
WQ Output face courant=0
WQ Output face peclet=0
WQ Output face adv mass=0
WQ Output face disp mass=0
WQ Output cell mass=0
WQ Output cell source sink temp=0
WQ Output cell source sink nsm=0
WQ Output MaxMinRange=-1
WQ Daily Max Min Mean=-1
WQ Daily Range=0
WQ Daily Time=0
WQ Create Restart=0
WQ Fixed Restart=0
WQ System Summary=False
WQ Profile= 1
Sorting and Armoring Iterations= 10
XS Update Threshold= 0.02
Hydraulics Update Threshold= 0.02
Energy Slope Method= 1
Volume Change Method= 0
XS Weighting Method= 0
Number of US Weighted Cross Sections= 1
Number of DS Weighted Cross Sections= 1
Upstream XS Weight=0.25
Main XS Weight=0.5
Downstream XS Weight=0.25
Number of DS XS's Weighted with US Boundary= 1
Upstream Boundary Weight= 1
Weight of XSs Associated with US Boundary= 0
Number of US XS's Weighted with DS Boundary= 1
Downstream Boundary Weight= 0.5
Weight of XSs Associated with DS Boundary= 0.5
Sediment Output Level= 4
Mass or Volume Output= 0
Output Increment Type= 1
Profile and TS Output Increment= 10
XS Output Flag= 0
XS Output Increment= 10
Disregard all LS=0
Disregard all Conn=0
Disregard all Breaches=0
Disregard all Pumps=0

--- E100-00-00.p01 (plan) ---

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Plan Title=Effective MP 2014
Short Identifier=Eff MP
Geom File=g01
Flow File=f01
Encroach Param=-1 ,0,0, 0
FEMA Effective Multi-Profile June 2014
UNET ZSATol= 0.05
UNET MaxInSteps= 0
UNET Convert EG Bridges= 0

--- E100-00-00.f02 (steady flow) ---

Flow Title=Effective FW 2014
Program Version=4.00
Number of Profiles= 2
Profile Names=1PCT_100yr,1PCTFloodway_100yr
River Rch & RM=E100-00-00,E100-00-00_N034 ,135006.0
     251     251
River Rch & RM=E100-00-00,E100-00-00_N034 ,133960.0
     363     363
River Rch & RM=E100-00-00,E100-00-00_N034 ,133211
     366     366
River Rch & RM=E100-00-00,E100-00-00_N034 ,133191
     381     381
River Rch & RM=E100-00-00,E100-00-00_N034 ,133109
     411     411
River Rch & RM=E100-00-00,E100-00-00_N034 ,132955.0
     456     456
River Rch & RM=E100-00-00,E100-00-00_N034 ,132744.
     548     548
River Rch & RM=E100-00-00,E100-00-00_N034 ,131721.0
     575     575
River Rch & RM=E100-00-00,E100-00-00_N034 ,131453.0
     588     588
River Rch & RM=E100-00-00,E100-00-00_N034 ,131331.
     640     640
River Rch & RM=E100-00-00,E100-00-00_N034 ,129818.0
    1968    1968
River Rch & RM=E100-00-00,E100-00-00_N034 ,128748.
    2039    2039
River Rch & RM=E100-00-00,E100-00-00_N034 ,128236.0
    2175    2175
River Rch & RM=E100-00-00,E100-00-00_N034 ,127300.0
    2350    2350
River Rch & RM=E100-00-00,E100-00-00_N034 ,126183.0
    2454    2454
River Rch & RM=E100-00-00,E100-00-00_N034 ,125563.
    2585    2585
River Rch & RM=E100-00-00,E100-00-00_N034 ,124809.
    2670    2670
River Rch & RM=E100-00-00,E100-00-00_N034 ,124344.0
    2823    2823
River Rch & RM=E100-00-00,E100-00-00_N034 ,123541.0
    2988    2988
River Rch & RM=E100-00-00,E100-00-00_N034 ,122719.
    3056    3056
River Rch & RM=E100-00-00,E100-00-00_N034 ,122396.
    3197    3197
River Rch & RM=E100-00-00,E100-00-00_N034 ,121745.0
    3364    3364
River Rch & RM=E100-00-00,E100-00-00_N034 ,120253.0
    5581    5581
River Rch & RM=E100-00-00,E100-00-00_N034 ,119390.0
    5751    5751
River Rch & RM=E100-00-00,E100-00-00_N034 ,118660.0
    5963    5963
River Rch & RM=E100-00-00,E100-00-00_N034 ,117779.0
    6239    6239
River Rch & RM=E100-00-00,E100-00-00_N034 ,116680
    6453    6453
River Rch & RM=E100-00-00,E100-00-00_N034 ,115807.0
    6671    6671
River Rch & RM=E100-00-00,E100-00-00_N034 ,114948.0
    6855    6855
River Rch & RM=E100-00-00,E100-00-00_N034 ,114246.0
    7172    7172
River Rch & RM=E100-00-00,E100-00-00_N034 ,113080.0
    7518    7518
River Rch & RM=E100-00-00,E100-00-00_N034 ,111861.0
    7829    7829
River Rch & RM=E100-00-00,E100-00-00_N034 ,110813.0
    7939    7939
River Rch & RM=E100-00-00,E100-00-00_N034 ,110454.0
    8280    8280
River Rch & RM=E100-00-00,E100-00-00_N034 ,108221
    8378    8378
River Rch & RM=E100-00-00,E100-00-00_N034 ,107598.0
    8693    8693
River Rch & RM=E100-00-00,E100-00-00_N034 ,104527.0
   10734   10734
River Rch & RM=E100-00-00,E100-00-00_N034 ,103364.0
   11001   11001
River Rch & RM=E100-00-00,E100-00-00_N034 ,102317.0
   11420   11420
River Rch & RM=E100-00-00,E100-00-00_N034 ,100723.0
   11911   11911
River Rch & RM=E100-00-00,E100-00-00_N034 ,93748.70
   13637   13637
River Rch & RM=E100-00-00,E100-00-00_N034 ,90490.0
   12588   12588
River Rch & RM=E100-00-00,E100-00-00_N034 ,82633.0
   13111   13111
River Rch & RM=E100-00-00,E100-00-00_N034 ,77129.0
   15063   15063
River Rch & RM=E100-00-00,E100-00-00_N034 ,63780.0
   18126   18126
River Rch & RM=E100-00-00,E100-00-00_N034 ,62890.0
   18631   18631
River Rch & RM=E100-00-00,E100-00-00_N034 ,55757.0
   23224   23224
River Rch & RM=E100-00-00,E100-00-00_N034 ,52833.
   23787   23787
River Rch & RM=E100-00-00,E100-00-00_N034 ,46827.0
   32438   32438
River Rch & RM=E100-00-00,E100-00-00_N034 ,35718.0
   32482   32482
River Rch & RM=E100-00-00,E100-00-00_N034 ,28190.0
   32654   32654
River Rch & RM=E100-00-00,E100-00-00_N034 ,16831.0
   32623   32623
River Rch & RM=E100-00-00,E100-00-00_N034 ,6775.
   44376   44376
Boundary for River Rch & Prof#=E100-00-00,E100-00-00_N034 , 1
Up Type= 0
Dn Type= 1
Dn Known WS=34.05
Boundary for River Rch & Prof#=E100-00-00,E100-00-00_N034 , 2
Up Type= 0
Dn Type= 1
Dn Known WS=35.05
Observed WS=E100-00-00      ,E100-00-00_N034       ,961.5   ,2,,,
Observed WS=E100-00-00      ,E100-00-00_N034       ,7608.5  ,2,,,
Observed WS=E100-00-00      ,E100-00-00_N034       ,17597.0 ,0,,,
Observed WS=E100-00-00      ,E100-00-00_N034       ,17678.5 ,2,,,
Observed WS=E100-00-00      ,E100-00-00_N034       ,22796.5 ,2,,,
Observed WS=E100-00-00      ,E100-00-00_N034       ,28152.5 ,2,,,
Observed WS=E100-00-00      ,E100-00-00_N034       ,33645.5 ,2,,,
Observed WS=E100-00-00      ,E100-00-00_N034       ,34951.5 ,2,,,
Observed WS=E100-00-00      ,E100-00-00_N034       ,39017.0 ,0,,,
Observed WS=E100-00-00      ,E100-00-00_N034       ,42603.0 ,2,,,
Observed WS=E100-00-00      ,E100-00-00_N034       ,50865.0 ,2,,,
Observed WS=E100-00-00      ,E100-00-00_N034       ,54606.0 ,2,,,
Observed WS=E100-00-00      ,E100-00-00_N034       ,56718.5 ,2,,,
Observed WS=E100-00-00      ,E100-00-00_N034       ,65467.5 ,2,,,
Observed WS=E100-00-00      ,E100-00-00_N034       ,66641.5 ,2,,,
Observed WS=E100-00-00      ,E100-00-00_N034       ,70266.0 ,0,,,
Observed WS=E100-00-00      ,E100-00-00_N034       ,70306.5 ,2,,,
Observed WS=E100-00-00      ,E100-00-00_N034       ,75984.0 ,2,,,
Observed WS=E100-00-00      ,E100-00-00_N034       ,84703.5 ,2,,,
Observed WS=E100-00-00      ,E100-00-00_N034       ,87449.0 ,2,,,
Observed WS=E100-00-00      ,E100-00-00_N034       ,91947.5 ,2,,,
Observed WS=E100-00-00      ,E100-00-00_N034       ,93477.0 ,2,,,
Observed WS=E100-00-00      ,E100-00-00_N034       ,99176.0 ,2,,,
Observed WS=E100-00-00      ,E100-00-00_N034       ,110399.0,2,,,
Observed WS=E100-00-00      ,E100-00-00_N034       ,116605.5,2,,,
Observed WS=E100-00-00      ,E100-00-00_N034       ,122558.0,2,,,
DSS Import GetInterval= 0
DSS Import GetPeak= 0
DSS Import FillOption= 0

--- E100-00-00.f01 (steady flow) ---

Flow Title=Effective MP 2014
Program Version=4.00
Number of Profiles= 4
Profile Names=10PCT_10yr,2PCT_50yr,1PCT_100yr,0.2PCT_500yr
River Rch & RM=E100-00-00,E100-00-00_N034 ,135006.0
     142     214     251     358
River Rch & RM=E100-00-00,E100-00-00_N034 ,133960.0
     205     309     363     518
River Rch & RM=E100-00-00,E100-00-00_N034 ,133211
     207     312     366     523
River Rch & RM=E100-00-00,E100-00-00_N034 ,133191
     216     325     381     545
River Rch & RM=E100-00-00,E100-00-00_N034 ,133109
     233     351     411     588
River Rch & RM=E100-00-00,E100-00-00_N034 ,132955.0
     258     389     456     652
River Rch & RM=E100-00-00,E100-00-00_N034 ,132744.
     310     468     548     783
River Rch & RM=E100-00-00,E100-00-00_N034 ,131721.0
     326     491     575     822
River Rch & RM=E100-00-00,E100-00-00_N034 ,131453.0
     333     502     588     840
River Rch & RM=E100-00-00,E100-00-00_N034 ,131331.
     362     546     640     914
River Rch & RM=E100-00-00,E100-00-00_N034 ,129818.0
    1119    1683    1968    2796
River Rch & RM=E100-00-00,E100-00-00_N034 ,128748.
    1162    1746    2039    2889
River Rch & RM=E100-00-00,E100-00-00_N034 ,128236.0
    1245    1868    2175    3069
River Rch & RM=E100-00-00,E100-00-00_N034 ,127300.0
    1351    2024    2350    3297
River Rch & RM=E100-00-00,E100-00-00_N034 ,126183.0
    1414    2116    2454    3431
River Rch & RM=E100-00-00,E100-00-00_N034 ,125563.
    1495    2234    2585    3601
River Rch & RM=E100-00-00,E100-00-00_N034 ,124809.
    1547    2310    2670    3711
River Rch & RM=E100-00-00,E100-00-00_N034 ,124344.0
    1641    2448    2823    3907
River Rch & RM=E100-00-00,E100-00-00_N034 ,123541.0
    1743    2597    2988    4119
River Rch & RM=E100-00-00,E100-00-00_N034 ,122719.
    1785    2658    3056    4206
River Rch & RM=E100-00-00,E100-00-00_N034 ,122396.
    1873    2786    3197    4386
River Rch & RM=E100-00-00,E100-00-00_N034 ,121745.0
    1977    2937    3364    4598
River Rch & RM=E100-00-00,E100-00-00_N034 ,120253.0
    3270    4843    5581    7687
River Rch & RM=E100-00-00,E100-00-00_N034 ,119390.0
    3419    4998    5751    7861
River Rch & RM=E100-00-00,E100-00-00_N034 ,118660.0
    3608    5192    5963    8077
River Rch & RM=E100-00-00,E100-00-00_N034 ,117779.0
    3859    5444    6239    8355
River Rch & RM=E100-00-00,E100-00-00_N034 ,116680
    4001    5639    6453    8577
River Rch & RM=E100-00-00,E100-00-00_N034 ,115807.0
    4146    5837    6671    8801
River Rch & RM=E100-00-00,E100-00-00_N034 ,114948.0
    4268    6004    6855    8988
River Rch & RM=E100-00-00,E100-00-00_N034 ,114246.0
    4479    6293    7172    9309
River Rch & RM=E100-00-00,E100-00-00_N034 ,113080.0
    4711    6610    7518    9656
River Rch & RM=E100-00-00,E100-00-00_N034 ,111861.0
    4920    6895    7829    9965
River Rch & RM=E100-00-00,E100-00-00_N034 ,110813.0
    4993    6995    7939   10073
River Rch & RM=E100-00-00,E100-00-00_N034 ,110454.0
    5223    7314    8280   10459
River Rch & RM=E100-00-00,E100-00-00_N034 ,108221
    5290    7406    8378   10570
River Rch & RM=E100-00-00,E100-00-00_N034 ,107598.0
    5503    7702    8693   10925
River Rch & RM=E100-00-00,E100-00-00_N034 ,104527.0
    6755    9536   10734   13901
River Rch & RM=E100-00-00,E100-00-00_N034 ,103364.0
    6917    9766   11001   14315
River Rch & RM=E100-00-00,E100-00-00_N034 ,102317.0
    7170   10127   11420   14968
River Rch & RM=E100-00-00,E100-00-00_N034 ,100723.0
    7760   10590   11911   15245
River Rch & RM=E100-00-00,E100-00-00_N034 ,93748.70
    8890   12159   13637   17583
River Rch & RM=E100-00-00,E100-00-00_N034 ,90490.0
    8809   11601   12588   15208
River Rch & RM=E100-00-00,E100-00-00_N034 ,82633.0
    8947   12016   13111   16279
River Rch & RM=E100-00-00,E100-00-00_N034 ,77129.0
    9859   13547   15063   19678
River Rch & RM=E100-00-00,E100-00-00_N034 ,63780.0
   11496   15965   18126   25001
River Rch & RM=E100-00-00,E100-00-00_N034 ,62890.0
   12022   16364   18631   25660
River Rch & RM=E100-00-00,E100-00-00_N034 ,55757.0
   15172   20514   23224   31674
River Rch & RM=E100-00-00,E100-00-00_N034 ,52833.
   15840   21391   23787   31827
River Rch & RM=E100-00-00,E100-00-00_N034 ,46827.0
   21750   29307   32438   42091
River Rch & RM=E100-00-00,E100-00-00_N034 ,35718.0
   22599   29511   32482   42191
River Rch & RM=E100-00-00,E100-00-00_N034 ,28190.0
   23359   29876   32654   42102
River Rch & RM=E100-00-00,E100-00-00_N034 ,16831.0
   23524   29964   32623   41687
River Rch & RM=E100-00-00,E100-00-00_N034 ,6775.
   31625   40965   44376   54399
River Rch & RM=E100-00-00,E100-00-00_N034 ,-442
   38441   51660   59250   80561
River Rch & RM=E100-00-00,E100-00-00_N034 ,-2814.3
   38563   51891   59499   80918
Boundary for River Rch & Prof#=E100-00-00,E100-00-00_N034 , 1
Up Type= 0
Dn Type= 1
Dn Known WS=22
Boundary for River Rch & Prof#=E100-00-00,E100-00-00_N034 , 2
Up Type= 0
Dn Type= 1
Dn Known WS=27.45
Boundary for River Rch & Prof#=E100-00-00,E100-00-00_N034 , 3
Up Type= 0
Dn Type= 1
Dn Known WS=30.05
Boundary for River Rch & Prof#=E100-00-00,E100-00-00_N034 , 4
Up Type= 0
Dn Type= 1
Dn Known WS=35.2
Observed WS=E100-00-00      ,E100-00-00_N034 ,961.5   ,2,,,,
Observed WS=E100-00-00      ,E100-00-00_N034 ,7608.5  ,2,,,,
Observed WS=E100-00-00      ,E100-00-00_N034 ,17597.0 ,0,,,,
Observed WS=E100-00-00      ,E100-00-00_N034 ,17678.5 ,2,,,,
Observed WS=E100-00-00      ,E100-00-00_N034 ,22796.5 ,2,,,,
Observed WS=E100-00-00      ,E100-00-00_N034 ,28152.5 ,2,,,,
Observed WS=E100-00-00      ,E100-00-00_N034 ,33645.5 ,2,,,,
Observed WS=E100-00-00      ,E100-00-00_N034 ,34951.5 ,2,,,,
Observed WS=E100-00-00      ,E100-00-00_N034 ,39017.0 ,0,,,,
Observed WS=E100-00-00      ,E100-00-00_N034 ,42603.0 ,2,,,,
Observed WS=E100-00-00      ,E100-00-00_N034 ,50865.0 ,2,,,,
Observed WS=E100-00-00      ,E100-00-00_N034 ,54606.0 ,2,,,,
Observed WS=E100-00-00      ,E100-00-00_N034 ,56718.5 ,2,,,,
Observed WS=E100-00-00      ,E100-00-00_N034 ,65467.5 ,2,,,,
Observed WS=E100-00-00      ,E100-00-00_N034 ,66641.5 ,2,,,,
Observed WS=E100-00-00      ,E100-00-00_N034 ,70266.0 ,0,,,,
Observed WS=E100-00-00      ,E100-00-00_N034 ,70306.5 ,2,,,,
Observed WS=E100-00-00      ,E100-00-00_N034 ,75984.0 ,2,,,,
Observed WS=E100-00-00      ,E100-00-00_N034 ,84703.5 ,2,,,,
Observed WS=E100-00-00      ,E100-00-00_N034 ,87449.0 ,2,,,,
Observed WS=E100-00-00      ,E100-00-00_N034 ,91947.5 ,2,,,,
Observed WS=E100-00-00      ,E100-00-00_N034 ,93477.0 ,2,,,,
Observed WS=E100-00-00      ,E100-00-00_N034 ,99176.0 ,2,,,,
Observed WS=E100-00-00      ,E100-00-00_N034 ,110399.0,2,,,,
Observed WS=E100-00-00      ,E100-00-00_N034 ,116605.5,2,,,,
Observed WS=E100-00-00      ,E100-00-00_N034 ,122558.0,2,,,,
DSS Import GetInterval= 0
DSS Import GetPeak= 0
DSS Import FillOption= 0

--- E100-00-00.g02 (geometry) ---

Geom Title=E100-00-00 2014(Unext for FW)
Program Version=4.00
BEGIN GEOM DESCRIPTION:
-Added XS 26225 and 26307.3 from Dodson's Worthshire LOMR model
-Added XS 33909.08 and 33962.58 from Dodson's W. 21st Street LOMR model
-Updated North Houston Rosslyn bridge deck & ineffective areas.
-Replaced 0.99 n-values in E500-04-00 with ineffective areas
-Contraction/expansion coeff. of 75698 and 75102 increase to 0.4/0.6 to reflect abrupt channel area increase for E500-04-00.
-Added new cross sections between 57918 and 62890 (Sept 2009)
-Updated geometry of 610 and RR bridge near Yale to reflect survey data (Sept 2009)
-Updated N values along WOB (Sept 2009)
END GEOM DESCRIPTION:

River Reach=E100-00-00      ,E100-00-00_N034
Reach XY= 30
      3034649.98     13899658.53       3035600.5     13900806.97
      3039070.03     13900922.17      3041947.75       13899641.
      3047808.75     13899707.76      3049999.72     13897081.02
       3054399.9     13894741.61      3056401.71     13888326.87
      3061527.19     13885154.59      3070183.44     13882294.35
      3073045.25       13882823.      3077039.48     13881696.62
      3079983.92     13882966.59        3083338.       13881830.
      3089801.47     13876474.14      3089321.44     13874027.09
      3092832.48     13868042.07      3092044.28     13864494.33
      3095414.08     13862073.32      3096866.33     13858928.35
      3101492.31     13856714.34      3107195.43     13848549.41
      3108490.57     13848939.17      3111991.44     13846638.82
      3113757.07     13848460.87      3118002.72     13849329.79
      3120658.57     13847939.46       3123937.1     13843034.56
       3125249.5       13842664.      3125750.73      13843875.2

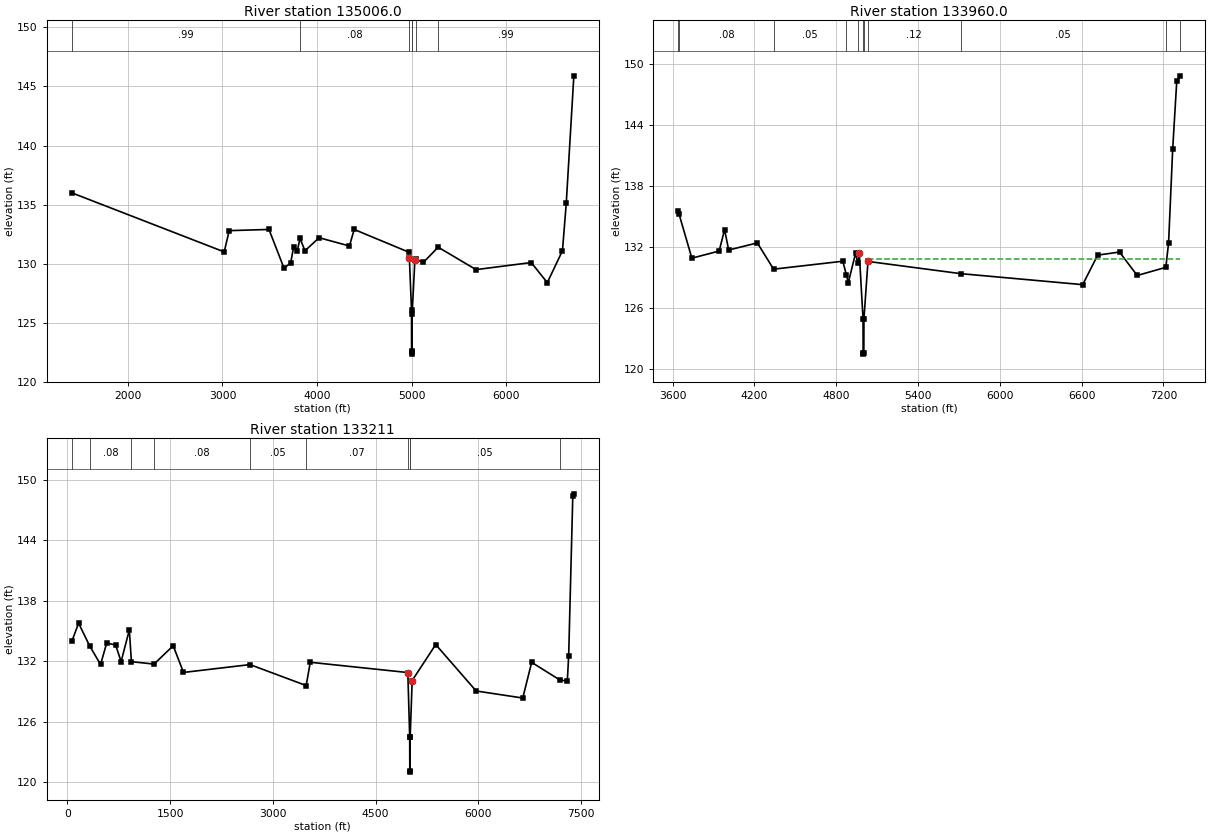
Type RM Length L Ch R = 1 ,135006.0,1046.7,1046,1043.9
BEGIN DESCRIPTION:
Cross Section E100-00-00-X103
END DESCRIPTION:
XS GIS Cut Line= 6
      3031664.05     13901637.52      3032973.73     13900662.07
      3034477.46     13899820.77      3034896.43     13899522.89
      3035278.17     13899266.81      3036136.71     13898807.84
#Sta/Elev= 30
    1408     136  3018.1     131  3071.1   132.8  3491.1   132.9  3651.1   129.6
  3721.1   130.1  3751.1   131.4  3791.1   131.1  3818.6  132.15  3871.1   131.1
  4021.1   132.2  4341.1   131.5  4391.1   132.9  4967.6  130.98  4974.1   130.5
  4996.8  126.05  4997.5  122.56  5002.2  122.35  5002.6  122.58  5003.4  125.78
  5032.3  130.31  5039.6  130.37  5123.2  130.12  5278.3   131.4  5678.3   129.5
  6261.2   130.1  6431.2   128.4  6591.2   131.1  6631.2   135.1  6711.5   145.9
#Mann= 7 ,-1 , 0
    1408     .99       0  3818.6     .08       0  4967.6     .04       0
  4996.8    .015       0  5003.4     .04       0  5039.6     .12       0
  5278.3     .99       0
Bank Sta=4974.1,5032.3
XS Rating Curve= 0 ,0
Exp/Cntr=0.3,0.1

Type RM Length L Ch R = 1 ,133960.0,764.8,749,728.8
BEGIN DESCRIPTION:
Cross Section E100-00-00-X102
END DESCRIPTION:
XS GIS Cut Line= 4
      3034095.65     13901118.88      3035092.43     13900684.22
      3035536.71     13900328.39      3036811.66     13898753.85
#Sta/Elev= 30
  3641.2   135.5  3647.9  135.19  3741.2   130.9  3941.2   131.6  3981.2   133.7
  4011.2   131.7  4221.2   132.4  4340.6  129.82  4848.6   130.6  4873.8  129.28
  4888.6   128.5  4942.1  131.39  4958.2  130.38  4969.3  131.37  4996.6  124.94
  4997.5  121.58  4998.1  121.48  5002.4  121.62  5003.4  124.96  5032.8  130.58
  5713.4  129.38  6607.8   128.3  6717.8   131.2  6877.8   131.5  7007.8   129.2
  7217.6     130  7237.8   132.4  7267.8   141.6  7297.8   148.3  7323.8   148.8
#Mann= 11 ,-1 , 0
  3641.2     .07       0  3647.9     .08       0  4340.6     .05       0
  4873.8     .07       0  4958.2     .04       0  4996.6    .015       0
  5003.4     .04       0  5032.8     .12       0  5713.4     .05       0
  7217.6     .08       0  7323.8     .99       0
#XS Ineff= 2 , 0
                          5052.4          130.81
Permanent Ineff=
       F       F
Bank Sta=4969.3,5032.8
XS Rating Curve= 0 ,0
Exp/Cntr=0.3,0.1

Type RM Length L Ch R = 1 ,133211  ,20,20,20
BEGIN DESCRIPTION:
E100-00-00-X101.5
END DESCRIPTION:
XS GIS Cut Line= 5
      3035750.82     13905774.74      3035917.55     13901043.58
      3035930.57     13900647.74      3035929.68     13899847.78
      3036807.77     13898760.64
#Sta/Elev= 30
    66.1  133.96   166.1  135.77   326.1  133.53   486.1  131.67   576.1  133.81
   706.1   133.6   786.1  131.96   906.1  135.11   936.1  131.95  1266.1  131.71
  1546.1  133.53  1696.1  130.88  2666.1  131.66  3486.1  129.58  3546.1  131.89
  4969.3  130.87  4996.6  124.44  4998.1  120.98  5002.4  121.12  5003.4  124.46
  5032.8  130.08  5376.2  133.65  5966.2  129.04  6646.2  128.34  6776.2  131.88
  7186.2  130.14  7296.2  130.01  7316.2  132.55  7376.2  148.42  7391.6  148.62
#Mann= 10 ,-1 , 0
    66.1     .99       0   326.1     .08       0   936.1     .07       0
  1266.1     .08       0  2666.1     .05       0  3486.1     .07       0
  4969.3     .04       0  4996.6    .015       0  5003.4     .05       0
  7186.2     .08       0
Bank Sta=4969.3,5032.8
XS Rating Curve= 0 ,0
Exp/Cntr=0.5,0.3