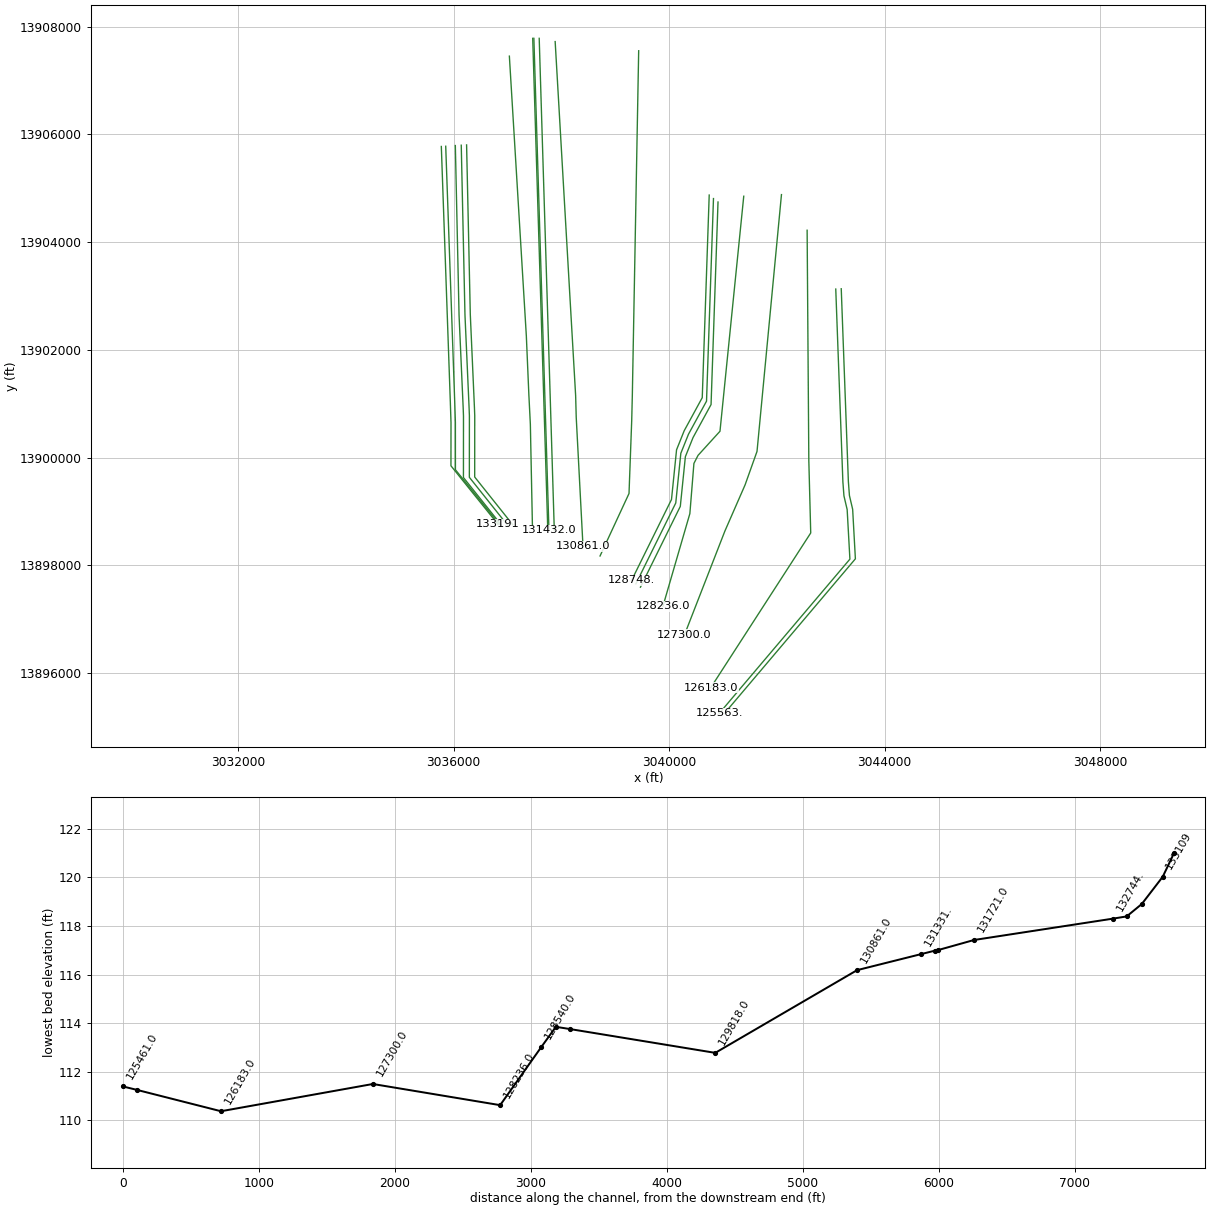
HEC-RAS study E100-00-00.prj: E100-00-00

--- E100-00-00.g02 (geometry) --- (continued)

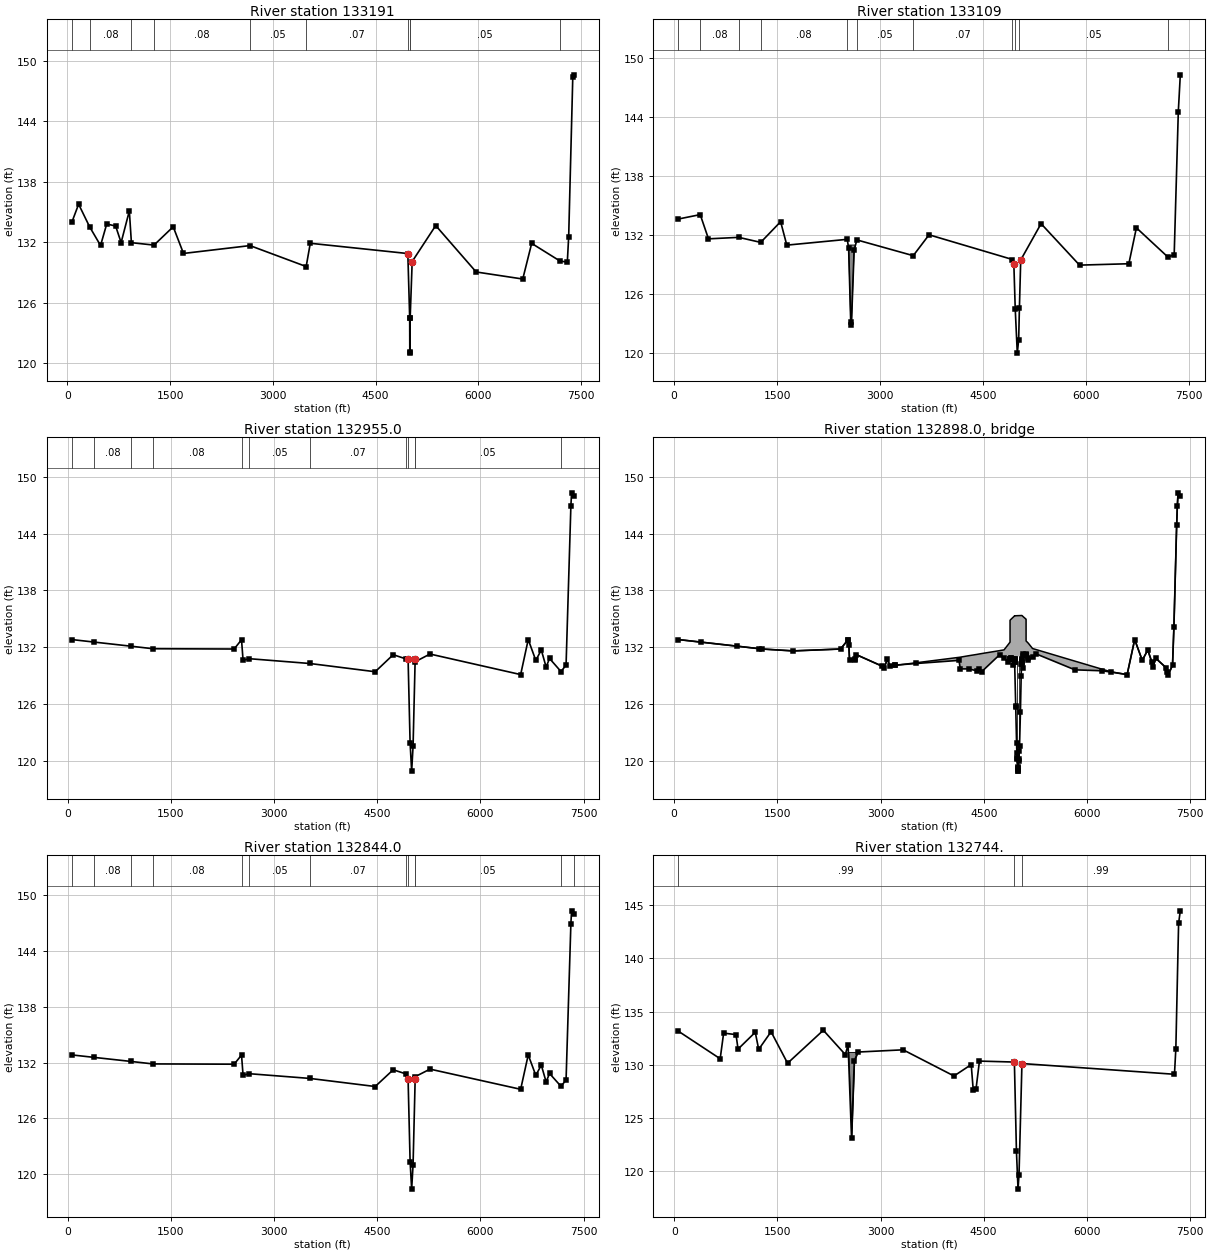
Type RM Length L Ch R = 1 ,133191  ,83,82,81.8
BEGIN DESCRIPTION:
E100-00-00-X101.5
END DESCRIPTION:
XS GIS Cut Line= 5
      3035770.82     13905774.74      3035937.55     13901043.58
      3035950.57     13900647.74      3035949.68     13899847.78
      3036824.45     13898760.65
#Sta/Elev= 30
    66.1  133.96   166.1  135.77   326.1  133.53   486.1  131.67   576.1  133.81
   706.1   133.6   786.1  131.96   906.1  135.11   936.1  131.95  1266.1  131.71
  1546.1  133.53  1696.1  130.88  2666.1  131.66  3486.1  129.58  3546.1  131.89
  4969.3  130.87  4996.6  124.44  4998.1  120.98  5002.4  121.12  5003.4  124.46
  5032.8  130.08  5376.2  133.65  5966.2  129.04  6646.2  128.34  6776.2  131.88
  7186.2  130.14  7296.2  130.01  7316.2  132.55  7376.2  148.42  7391.6  148.62
#Mann= 10 ,-1 , 0
    66.1     .99       0   326.1     .08       0   936.1     .07       0
  1266.1     .08       0  2666.1     .05       0  3486.1     .07       0
  4969.3     .04       0  4996.6    .015       0  5003.4     .05       0
  7186.2     .08       0
Bank Sta=4969.3,5032.8
XS Rating Curve= 0 ,0
Exp/Cntr=0.5,0.3

Type RM Length L Ch R = 1 ,133109  ,155,154,153.8
BEGIN DESCRIPTION:
E100-00-00-X101.3
END DESCRIPTION:
XS GIS Cut Line= 5
      3035852.39     13905778.96      3036019.12      13901047.8
      3036032.14     13900651.96      3036032.66     13899774.65
      3036848.36     13898763.46
#Sta/Elev= 30
    62.3  133.64   382.3  134.09   502.3  131.63   942.3  131.78  1262.3  131.27
  1552.3  133.37  1642.3  130.99  2522.3  131.58  2542.3  130.65  2572.3  123.23
  2582.3  122.89  2622.3   130.5  2662.3  131.52  3482.3  129.92  3712.3  132.04
  4926.4  129.53  4946.4  129.07  4966.4  124.55  4996.4  120.02  5016.4  121.35
 5027.17  124.56  5046.4  129.48  5342.4  133.17  5902.4  128.96  6619.8   129.1
  6729.8  132.75  7189.8  129.77  7279.8  130.03  7339.8  144.56  7368.9  148.29
#Mann= 11 ,-1 , 0
    62.3     .99       0   382.3     .08       0   942.3     .07       0
  1262.3     .08       0  2522.3     .04       0  2662.3     .05       0
  3482.3     .07       0  4926.4     .04       0  4966.4    .015       0
 5027.17     .05       0  7189.8     .08       0
#Block Obstruct= 2 , 0
       0    2685     131               0
Bank Sta=4946.4,5046.4
XS Rating Curve= 0 ,0
Exp/Cntr=0.5,0.3

Type RM Length L Ch R = 1 ,132955.0,112,111,109.9
BEGIN DESCRIPTION:
Upstream Section of Bridge/Culvert/Weir
END DESCRIPTION:
XS GIS Cut Line= 6
      3036031.04     13905792.27      3036100.03     13902642.67
      3036176.75     13900916.51      3036182.29     13900769.07
      3036181.43     13899630.05      3036888.02     13898744.18
#Sta/Elev= 30
    59.2   132.8     387  132.53   917.1   132.1  1238.8  131.83  2419.2   131.8
  2526.7  132.78  2549.2   130.6  2635.1  130.78  3519.2  130.27  4469.5   129.4
  4731.4   131.2  4910.4  130.77  4947.6  130.77    4977  121.87  4999.6   118.9
  5020.1  121.52  5050.5  130.71    5054  130.47  5266.4  131.27    6584   129.1
    6694   132.8    6804   130.6    6884   131.7    6954   129.9    7004   130.8
  7170.2  129.42    7244   130.1    7314   146.9    7324   148.3  7357.1     148
#Mann= 12 ,-1 , 0
    59.2      .2       0     387     .08       0   917.1     .07       0
  1238.8     .08       0  2526.7     .04       0  2635.1     .05       0
  3519.2     .07       0  4910.4     .04       0  4947.6     .04       0
  5050.5     .04       0    5054     .05       0  7170.2     .08       0
#XS Ineff= 2 , 0
       0  4937.2     130 5060.49       0     130
Permanent Ineff=
       F       F
Bank Sta=4947.6,5050.5
XS Rating Curve= 0 ,0
Exp/Cntr=0.5,0.3

Type RM Length L Ch R = 3 ,132898.0,,,
BEGIN DESCRIPTION:
HUFFMEISTER
Structure ID: E100-00-00-59
END DESCRIPTION:
Bridge Culvert--1,0,-1,-1, 0
Deck Dist Width WeirC Skew NumUp NumDn MinLoCord MaxHiCord MaxSubmerge Is_Ogee
10,94,2.6,0, 60, 60, , , 0.95, 0, ,,,
    59.2  1279.2  1729.2  2419.2  2529.2  2539.2  2549.2  2629.2  2649.2  3019.2
  3049.2  3099.2  3139.2  4139.5  4159.5  4279.5  4399.5  4429.5  4469.5  4731.4
  4794.9  4859.2 4882.09  4882.2  4890.1  4918.7  4927.8  4947.6 4948.57 4948.66
 5048.62 5048.73  5050.5  5054.9  5064.1    5074  5107.2  5115.3 5115.41  5148.1
  5209.4  5266.4    5825    6224  6343.5    6584    6694    6804    6884    6944
    6954    7004    7154    7184    7244    7264    7304    7314    7324  7357.1
   132.8   131.8   131.6   131.8   132.8   132.2   130.6   130.6   131.2     130
   129.8   130.7     130  130.92  130.94  131.09  131.23  131.27  131.32  131.63
  131.71  132.31  132.53  134.83   134.9   135.1  135.16   135.3   135.3  135.31
  135.34  135.34  135.34  135.34  135.28  135.21     135  134.95  132.65  132.41
  131.85  131.73  130.52  129.66   129.4   129.1   132.8   130.6   131.7   130.4
   129.9   130.8   129.8   129.1   130.1   134.1   144.9   146.9   148.3     148
   132.8   131.8   131.6   131.8   132.8   132.2   130.6   130.6   131.2     130
   129.8   130.7     130   130.6   129.7   129.7   129.5   129.7   129.4   131.2
  130.83  130.46  130.73  130.74  130.83  130.74   130.1  130.77  130.48  131.01
  131.04  130.24  130.71  130.41  129.79  131.25  131.31  131.17  131.17  130.61
  130.95  131.27   129.6   129.5  129.37   129.1   132.8   130.6   131.7   130.4
   129.9   130.8   129.8   129.1   130.1   134.1   144.9   146.9   148.3     148
    59.2  1279.2  1729.2  2419.2  2529.2  2539.2  2549.2  2629.2  2649.2  3019.2
  3049.2  3099.2  3139.2  4139.5  4159.5  4279.5  4399.5  4429.5  4469.5  4731.4
  4794.9  4859.2 4882.09  4882.2  4890.1  4918.7  4927.8  4947.6 4948.57 4948.66
 5048.62 5048.73  5050.5  5054.9  5064.1    5074  5107.2  5115.3 5115.41  5148.1
  5209.4  5266.4    5825    6224  6343.5    6584    6694    6804    6884    6944
    6954    7004    7154    7184    7244    7264    7304    7314    7324  7357.1
   132.8   131.8   131.6   131.8   132.8   132.2   130.6   130.6   131.2     130
   129.8   130.7     130  130.92  130.94  131.09  131.23  131.27  131.32  131.63
  131.71  132.31  132.53  134.83   134.9   135.1  135.16   135.3   135.3  135.31
  135.34  135.34  135.34  135.34  135.28  135.21     135  134.95  132.65  132.41
  131.85  131.73  130.52  129.66   129.4   129.1   132.8   130.6   131.7   130.4
   129.9   130.8   129.8   129.1   130.1   134.1   144.9   146.9   148.3     148
   132.3   131.3   131.1   131.3   132.3   131.7   130.1   130.1   130.7   129.5
   129.3   130.2   129.5   130.1   129.2   129.2     129   129.2   128.9   130.7
  130.33  129.96  130.23  130.24  130.33  130.24   129.6  130.27  129.98  130.51
  130.54  129.74  130.21  129.91  129.29  130.75  130.81  130.67  130.67  130.11
  130.45  130.77   129.1     129  128.87   128.6   132.3   130.1   131.2   129.9
   129.4   130.3   129.3   128.6   129.6   133.6   144.4   146.4   147.8   147.5
Pier Skew, UpSta & Num, DnSta & Num=  ,4984.299, 2 ,4984.299, 2 , 0 , 0 , 0 ,,
     1.3     1.3
  119.37  132.06
     1.3     1.3
  118.87  131.56
Pier Skew, UpSta & Num, DnSta & Num=  ,5014, 2 ,5014, 2 , 0 , 0 , 0 ,,
     1.3     1.3
  119.19  132.05
     1.3     1.3
  118.69  131.55
BR Coef= 1 , 1 , 0 ,1.25, 0 ,,,0.8,0,2,0,
WSPro=,,,, 1 ,,,, 0 ,,,, 0 ,,,,-1 ,-1 ,-1 , 0 , 0 , 0 , 0 , 0
BR U #Sta/Elev= 94
    59.2   132.8     387  132.53   917.1   132.1  1238.8  131.83  1279.2   131.8
  1729.2   131.6  2419.2   131.8  2526.7  132.78  2529.2   132.8  2539.2   132.2
  2549.2   130.6  2629.2   130.6  2635.1  130.78  2649.2   131.2  3019.2     130
  3049.2   129.8  3099.2   130.7  3139.2     130  3209.5   130.1  3213.7   130.1
  3519.2  130.27  4139.5   130.6  4159.5   129.7  4279.5   129.7  4399.5   129.5
  4429.5   129.7  4469.5   129.4  4731.4   131.2  4794.9  130.83  4859.2  130.46
 4882.09  130.73  4882.2  130.74 4882.31  130.74  4889.6  130.82  4890.1  130.83
  4910.4  130.77  4918.7  130.74  4927.8   130.1  4947.4  130.76  4947.6  130.77
 4948.57  130.48 4948.66  130.46  4964.5   125.8  4964.8  125.71    4977  121.87
  4984.3  120.22  4986.3  120.83  4990.5  120.26  4995.8  119.26  4997.2  118.96
  4999.6   118.9  5002.7  119.09  5004.2  119.37  5007.2  119.96    5014  120.21
  5014.3  120.99  5020.1  121.52  5032.9   125.1  5043.8  128.94 5048.62  130.21
 5048.73  130.24  5050.5  130.71    5054  130.47  5054.9  130.41  5064.1  129.79
  5072.7  131.06    5074  131.25  5107.2  131.31 5115.19  131.17  5115.3  131.17
 5115.41  131.17  5136.2  130.81  5148.1  130.61  5209.4  130.95  5266.4  131.27
    5825   129.6    6224   129.5  6343.5  129.37    6584   129.1    6694   132.8
    6804   130.6    6884   131.7    6944   130.4    6954   129.9    7004   130.8
    7154   129.8  7170.2  129.42    7184   129.1    7244   130.1    7264   134.1
    7304   144.9    7314   146.9    7324   148.3  7357.1     148
BR U #Mann= 12
    59.2      .2     387     .08   917.1     .07  1238.8     .08  2526.7     .04
  2635.1     .05  3519.2     .07  4910.4     .04  4947.6    .035  5050.5     .04
    5054     .05  7170.2     .08
BR U Banks=4947.6,5050.5
BR D #Sta/Elev= 94
    59.2   132.8     387  132.53   917.1   132.1  1238.8  131.83  1279.2   131.8
  1729.2   131.6  2419.2   131.8  2526.7  132.78  2529.2   132.8  2539.2   132.2
  2549.2   130.6  2629.2   130.6  2635.1  130.78  2649.2   131.2  3019.2     130
  3049.2   129.8  3099.2   130.7  3139.2     130  3209.5   130.1  3213.7   130.1
  3519.2  130.27  4139.5   130.6  4159.5   129.7  4279.5   129.7  4399.5   129.5
  4429.5   129.7  4469.5   129.4  4731.4   131.2  4794.9  130.83  4859.2  130.46
 4882.09  130.73  4882.2  130.74 4882.31  130.74  4889.6  130.82  4890.1  130.83
  4910.4  130.77  4918.7  130.74  4927.8   130.1  4947.4  130.26  4947.6  130.27
 4948.57  129.98 4948.66  129.96  4964.5   125.3  4964.8  125.21    4977  121.37
  4984.3  119.72  4986.3  120.33  4990.5  119.76  4995.8  118.76  4997.2  118.46
  4999.6   118.4  5002.7  118.59  5004.2  118.87  5007.2  119.46    5014  119.71
  5014.3  120.49  5020.1  121.02  5032.9   124.6  5043.8  128.44 5048.62  129.71
 5048.73  129.74  5050.5  130.21    5054  130.47  5054.9  130.41  5064.1  129.79
  5072.7  131.06    5074  131.25  5107.2  131.31 5115.19  131.17  5115.3  131.17
 5115.41  131.17  5136.2  130.81  5148.1  130.61  5209.4  130.95  5266.4  131.27
    5825   129.6    6224   129.5  6343.5  129.37    6584   129.1    6694   132.8
    6804   130.6    6884   131.7    6944   130.4    6954   129.9    7004   130.8
    7154   129.8  7170.2  129.42    7184   129.1    7244   130.1    7264   134.1
    7304   144.9    7314   146.9    7324   148.3  7357.1     148
BR D #Mann= 12
    59.2      .2     387     .08   917.1     .07  1238.8     .08  2526.7     .04
  2635.1     .05  3519.2     .07  4910.4     .04  4947.6    .035  5050.5     .04
    5054     .05  7170.2     .08
BR D Banks=4947.6,5050.5
BC Design=,, 0 ,, 0 ,,,,,,
BC HTab HWMax=148.33
BC Use User HTab Curves=0
BC User HTab FreeFlow(D)= 0

Type RM Length L Ch R = 1 ,132844.0,100,99,99.2
BEGIN DESCRIPTION:
Downstream Section of Bridge/Culvert/Weir
END DESCRIPTION:
XS GIS Cut Line= 6
      3036140.77     13905798.16      3036209.76     13902648.51
      3036286.47      13900922.3      3036292.01     13900774.98
      3036291.15     13899634.31      3036998.84     13898747.06
#Sta/Elev= 30
    59.2  132.83     387  132.56   917.1  132.13  1238.8  131.86  2419.2  131.83
  2526.7  132.81  2549.2  130.63  2635.1  130.81  3519.2   130.3  4469.5  129.43
  4731.4  131.23  4910.4   130.84947.599  130.26    4977  121.36  4999.6  118.39
5020.101  121.01  5050.5   130.2    5054   130.5  5266.4   131.3    6584  129.13
    6694  132.836803.999  130.63    6884  131.736954.001  129.93    7004  130.83
  7170.2  129.457243.999  130.13    7314  146.93    7324  148.337357.099  148.03
#Mann= 13 ,-1 , 0
    59.2     .99       0     387     .08       0   917.1     .07       0
  1238.8     .08       0  2526.7     .04       0  2635.1     .05       0
  3519.2     .07       0  4910.4     .04       04947.599     .04       0
  5050.5     .04       0    5054     .05       0  7170.2     .08       0
7357.099     .99       0
#XS Ineff= 2 , 0
       0  4937.2     130 5060.49       0     130
Permanent Ineff=
       F       F
Bank Sta=4947.599,5050.5
XS Rating Curve= 0 ,0
Exp/Cntr=0.5,0.3

Type RM Length L Ch R = 1 ,132744. ,1021.5,1023.96,124
BEGIN DESCRIPTION:
Huffmeister - D\S - XS 1
END DESCRIPTION:
XS GIS Cut Line= 6
      3036239.81     13905803.82      3036308.81     13902654.17
      3036385.52     13900927.96      3036391.06     13900780.64
       3036390.2     13899639.97      3037097.88     13898752.72
#Sta/Elev= 30
    58.4  133.16   668.4  130.56   718.4  132.97   898.4  132.83   928.4  131.47
  1178.4  133.05  1228.4  131.44  1408.4   133.1  1648.4  130.14  2168.4  133.24
  2488.4  130.95  2528.4  131.88  2578.4  123.15  2618.4  130.33  2668.4  131.19
  3328.8   131.4  4068.8  128.94  4318.8  130.01  4348.8  127.58  4388.8  127.72
  4438.8  130.34  4946.7  130.25  4976.7  121.85 4999.83   118.3 5014.02  119.65
  5056.7  130.11  7274.8   129.1  7294.8  131.52  7334.8   143.3  7359.7  144.47
#Mann= 3 ,-1 , 0
    58.4     .99       0  4946.7     .04       0  5056.7     .99       0
#Block Obstruct= 1 ,-1
 2527.09 2674.01   131.2
Bank Sta=4946.7,5056.7
XS Rating Curve= 0 ,0
Exp/Cntr=0.3,0.1

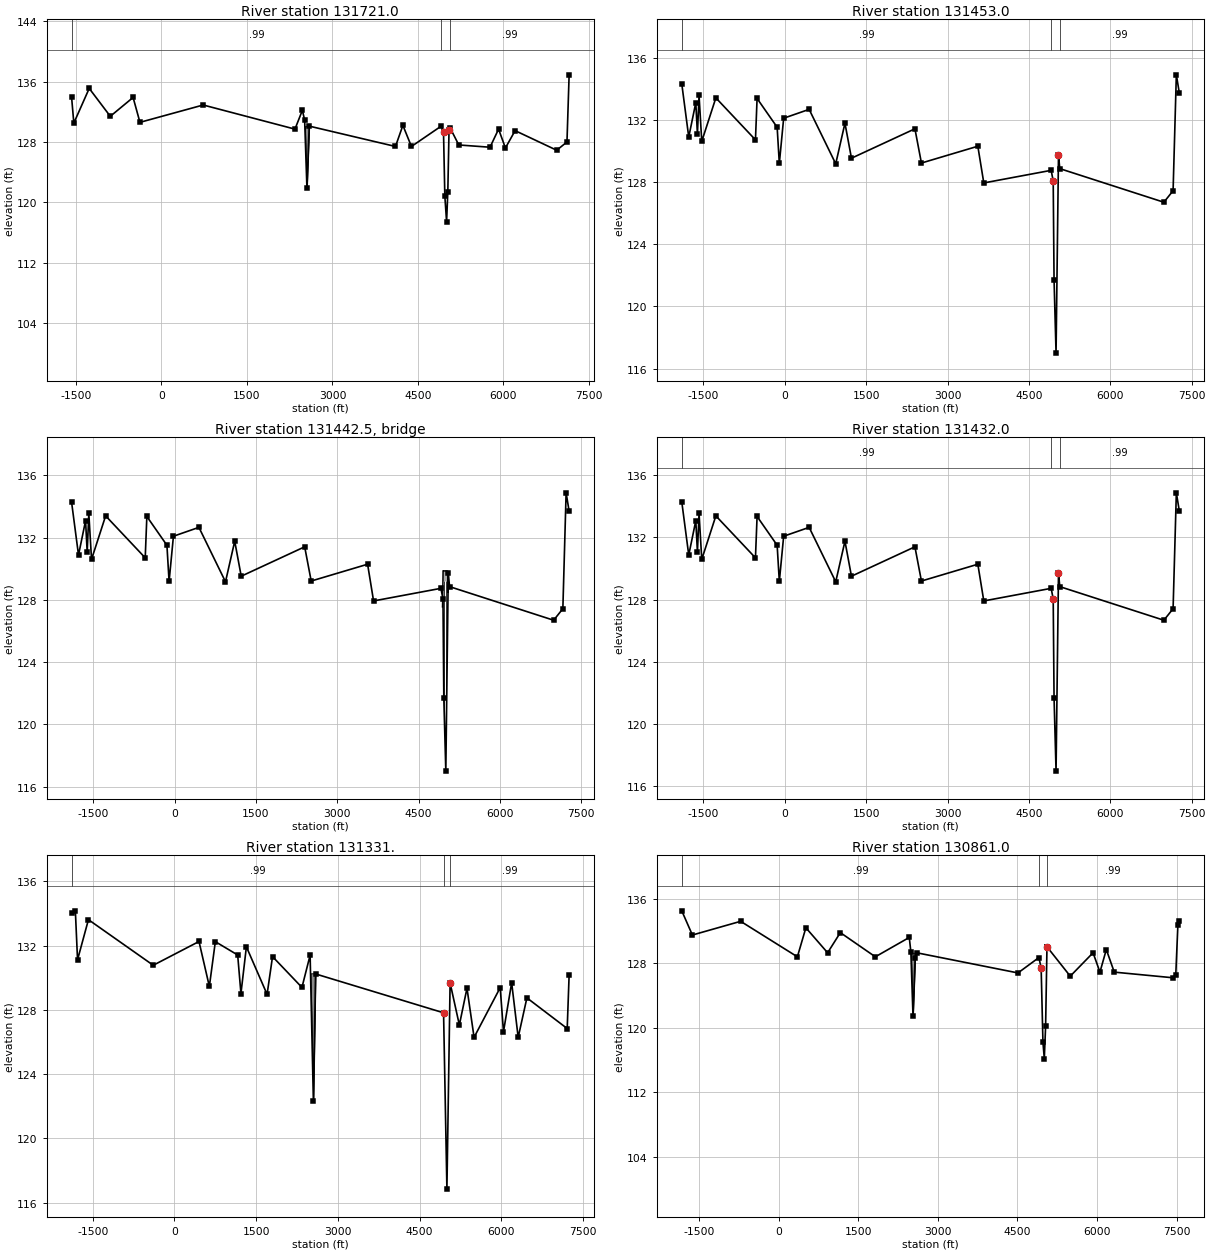
Type RM Length L Ch R = 1 ,131721.0,269.4,268,267.6
BEGIN DESCRIPTION:
Cross Section E100-00-00-X101
END DESCRIPTION:
XS GIS Cut Line= 5
      3037033.79     13907451.76      3037348.86      13902257.8
      3037396.07     13901157.92      3037423.34     13900620.38
      3037461.81     13898732.96
#Sta/Elev= 30
 -1578.2     134 -1538.2   130.5 -1268.2   135.1  -898.2   131.4  -498.2   133.9
  -378.2   130.6   731.8   132.9  2341.8   129.7  2471.8   132.2  2511.8   130.9
  2551.8   121.9  2591.8   130.1  4105.3   127.4  4235.3   130.2  4385.3   127.4
  4906.1  130.09  4948.1  129.36  4971.4  120.83  5002.2  117.42  5023.6  121.34
  5044.9  129.53  5065.8  129.84  5216.2   127.6  5764.4   127.3  5914.4   129.7
  6034.4   127.2  6204.4   129.5  6934.4   126.9  7114.4     128  7152.2   136.9
#Mann= 3 ,-1 , 0
 -1578.2     .99       0  4906.1     .04       0  5065.8     .99       0
#Block Obstruct= 2 ,-1
    2517  2591.8   130.1    2592  2592.5     100
Bank Sta=4948.1,5044.9
XS Rating Curve= 0 ,0
Exp/Cntr=0.5,0.3

Type RM Length L Ch R = 1 ,131453.0,21.6,21,20
BEGIN DESCRIPTION:
Upstream Section of Bridge/Culvert/Weir
END DESCRIPTION:
XS GIS Cut Line= 2
      3037467.04     13907781.79      3037747.07     13898650.92
#Sta/Elev= 30
 -1900.1  134.31 -1771.7  130.89 -1641.7   133.1 -1611.7  131.08 -1581.7  133.57
 -1531.7  130.61 -1271.7  133.41  -541.7  130.71  -511.7  133.37  -141.7  131.52
  -101.7  129.19   -21.7   132.1   448.3  132.67   938.3  129.17  1108.3  131.78
  1228.3  129.53  2398.3  131.42  2518.3  129.22  3558.3   130.3  3668.3  127.94
  4910.1  128.75 4948.04  128.07 4963.64  121.71 5000.44     117 5045.54  129.75
  5069.1  128.86  6988.3   126.7  7158.3  127.44  7218.3  134.89  7273.9  133.71
#Mann= 3 ,-1 , 0
 -1900.1     .99       0  4910.1     .04       0  5069.1     .99       0
#XS Ineff= 2 , 0
       0 4938.04  127.27 5055.54       0   126.4
Permanent Ineff=
       F       F
Bank Sta=4948.04,5045.54
XS Rating Curve= 0 ,0
Exp/Cntr=0.5,0.3

Type RM Length L Ch R = 3 ,131442.5,,,
BEGIN DESCRIPTION:
PL1_E100-00-00-58A
END DESCRIPTION:
Bridge Culvert--1,0,-1,-1, 0
Deck Dist Width WeirC Skew NumUp NumDn MinLoCord MaxHiCord MaxSubmerge Is_Ogee
10,1,2.6,0, 22, 22, , , 0.95, 0, ,,,
 4939.04  4939.9 4943.21  4943.3 4948.04 4949.74 4955.64 4963.64 4972.24 4976.54
 4986.74 4996.54 5000.44 5003.44 5011.04 5011.44 5021.24 5033.64 5034.94  5039.9
 5041.77 5041.88
  127.55  127.61   128.1  128.12  129.41  129.87  129.87  129.87  129.86  129.86
  129.86  129.86  129.86  129.86  129.86  129.86  129.85  129.85  129.85   128.5
  128.59  128.49
  127.55   127.6  127.79  127.79  128.74   129.2   129.2   129.2  129.19  129.19
  129.19  129.19  129.19  129.19  129.19  129.19  129.18  129.18  129.18  127.83
  128.46  128.49
 4939.04  4939.9 4943.21  4943.3 4948.04 4949.74 4955.64 4963.64 4972.24 4976.54
 4986.74 4996.54 5000.44 5003.44 5011.04 5011.44 5021.24 5033.64 5034.94  5039.9
 5041.77 5041.88
  127.55  127.61   128.1  128.12  129.41  129.87  129.87  129.87  129.86  129.86
  129.86  129.86  129.86  129.86  129.86  129.86  129.85  129.85  129.85   128.5
  128.59  128.49
  127.55   127.6  127.79  127.79  128.74   129.2   129.2   129.2  129.19  129.19
  129.19  129.19  129.19  129.19  129.19  129.19  129.18  129.18  129.18  127.83
  128.46  128.49
Pier Skew, UpSta & Num, DnSta & Num=  ,4972.2, 2 ,4972.2, 2 , 0 , 0 , 0 ,,
     1.5     1.5
  119.76  130.19
     1.5     1.5
  119.76  130.19
Pier Skew, UpSta & Num, DnSta & Num=  ,5011.4, 2 ,5011.4, 2 , 0 , 0 , 0 ,,
     1.5     1.5
  117.74  130.19
     1.5     1.5
  117.74  130.19
BR Coef= 1 , 1 , 0 ,1.25, 0 ,,,0.8,0,2,0,
WSPro=,,,, 1 ,,,, 0 ,,,, 0 ,,,,-1 ,-1 ,-1 , 0 , 0 , 0 , 0 , 0
BR U #Sta/Elev= 30
 -1900.1   134.3 -1771.7  130.88 -1641.7  133.09 -1611.7  131.07 -1581.7  133.56
 -1531.7   130.6 -1271.7   133.4  -541.7   130.7  -511.7  133.36  -141.7  131.51
  -101.7  129.18   -21.7  132.09   448.3  132.66   938.3  129.16  1108.3  131.77
  1228.3  129.52  2398.3  131.41  2518.3  129.21  3558.3  130.29  3668.3  127.93
  4910.1  128.74 4948.04  128.06 4963.64   121.7 5000.44  116.99 5045.54  129.74
  5069.1  128.85  6988.3  126.69  7158.3  127.43  7218.3  134.88  7273.9   133.7
BR U #Mann= 3
 -1900.1     .99  4910.1     .04  5069.1     .99
BR U Banks=4948.04,5045.54
BR D #Sta/Elev= 30
 -1900.1   134.3 -1771.7  130.88 -1641.7  133.09 -1611.7  131.07 -1581.7  133.56
 -1531.7   130.6 -1271.7   133.4  -541.7   130.7  -511.7  133.36  -141.7  131.51
  -101.7  129.18   -21.7  132.09   448.3  132.66   938.3  129.16  1108.3  131.77
  1228.3  129.52  2398.3  131.41  2518.3  129.21  3558.3  130.29  3668.3  127.93
  4910.1  128.74 4948.04  128.06 4963.64   121.7 5000.44  116.99 5045.54  129.74
  5069.1  128.85  6988.3  126.69  7158.3  127.43  7218.3  134.88  7273.9   133.7
BR D #Mann= 3
 -1900.1     .99  4910.1     .04  5069.1     .99
BR D Banks=4948.04,5045.54
BC Design=,, 0 ,, 0 ,,,,,,
BC HTab HWMax=134.89
BC Use User HTab Curves=0
BC User HTab FreeFlow(D)= 0

Type RM Length L Ch R = 1 ,131432.0,99,100,101
BEGIN DESCRIPTION:
Downstream Section of Bridge/Culvert/Weir
END DESCRIPTION:
XS GIS Cut Line= 2
      3037488.65      13907782.1      3037768.67     13898651.23
#Sta/Elev= 30
 -1900.1  134.29 -1771.7  130.87 -1641.7  133.08 -1611.7  131.06 -1581.7  133.55
 -1531.7  130.59 -1271.7  133.39  -541.7  130.69  -511.7  133.35  -141.7   131.5
  -101.7  129.17   -21.7  132.08   448.3  132.65   938.3  129.15  1108.3  131.76
  1228.3  129.51  2398.3   131.4  2518.3   129.2  3558.3  130.28  3668.3  127.92
  4910.1  128.73 4948.04  128.05 4963.64  121.69 5000.44  116.98 5045.54  129.73
  5069.1  128.84  6988.3  126.68  7158.3  127.42  7218.3  134.87  7273.9  133.69
#Mann= 3 ,-1 , 0
 -1900.1     .99       0  4910.1     .04       0  5069.1     .99       0
#XS Ineff= 2 , 0
       0 4941.37  127.27 5052.21       0   126.4
Permanent Ineff=
       F       F
Bank Sta=4948.04,5045.54
XS Rating Curve= 0 ,0
Exp/Cntr=0.5,0.3

Type RM Length L Ch R = 1 ,131331. ,472,470.99,470
BEGIN DESCRIPTION:
Pipe - D\S - XS 1
END DESCRIPTION:
XS GIS Cut Line= 2
      3037587.69      13907782.1      3037867.72     13898651.23
#Sta/Elev= 30
   -1890  134.02   -1820  134.17   -1780  131.12   -1580  133.62    -390  130.78
     450  132.26     640  129.46     750  132.25    1160  131.42    1220  129.02
    1320  131.93    1700  128.97    1800  131.32    2340   129.4    2490  131.41
    2550  122.34    2590  130.24    4940  127.82 5001.43  116.84    5060  129.68
    5230  127.06    5370  129.35    5500  126.29    5980  129.39    6040  126.64
    6190  129.69    6310  126.29    6470  128.75    7210  126.84  7245.2  130.18
#Mann= 3 ,-1 , 0
   -1890     .99       0    4940     .04       0    5060     .99       0
#Block Obstruct= 1 ,-1
 2435.26 2600.55  130.28
Bank Sta=4940,5060
XS Rating Curve= 0 ,0
Exp/Cntr=0.3,0.1

Type RM Length L Ch R = 1 ,130861.0,1044,1043,1038.1
BEGIN DESCRIPTION:
Cross Section E100-00-00-X100
END DESCRIPTION:
XS GIS Cut Line= 4
      3037883.88     13907721.78      3038263.91     13901151.16
      3038274.79     13900747.37      3038400.41      13898353.3
#Sta/Elev= 30
 -1829.9   134.5 -1629.9   131.5  -719.9   133.2   350.1   128.8   510.1   132.4
   920.1   129.3  1160.1   131.8  1820.1   128.8  2460.1   131.2  2490.1   129.4
  2530.1   121.5  2570.1   128.6  2600.1   129.3  4510.1   126.8    4905  128.71
  4946.8  127.38  4980.6  118.22  5006.1  116.18    5031  120.22  5056.5  130.01
  5061.9     130  5495.6   126.4  5925.6   129.3  6055.6   126.9  6175.6   129.7
  6325.6   126.9  7435.6   126.2  7485.6   126.6  7525.6   132.8    7553   133.2
#Mann= 3 ,-1 , 0
 -1829.9     .99       0    4905     .04       0  5061.9     .99       0
#Block Obstruct= 2 ,-1
    2489    2600   129.3    2601    2602     100
Bank Sta=4946.8,5056.5
XS Rating Curve= 0 ,0
Exp/Cntr=0.3,0.1

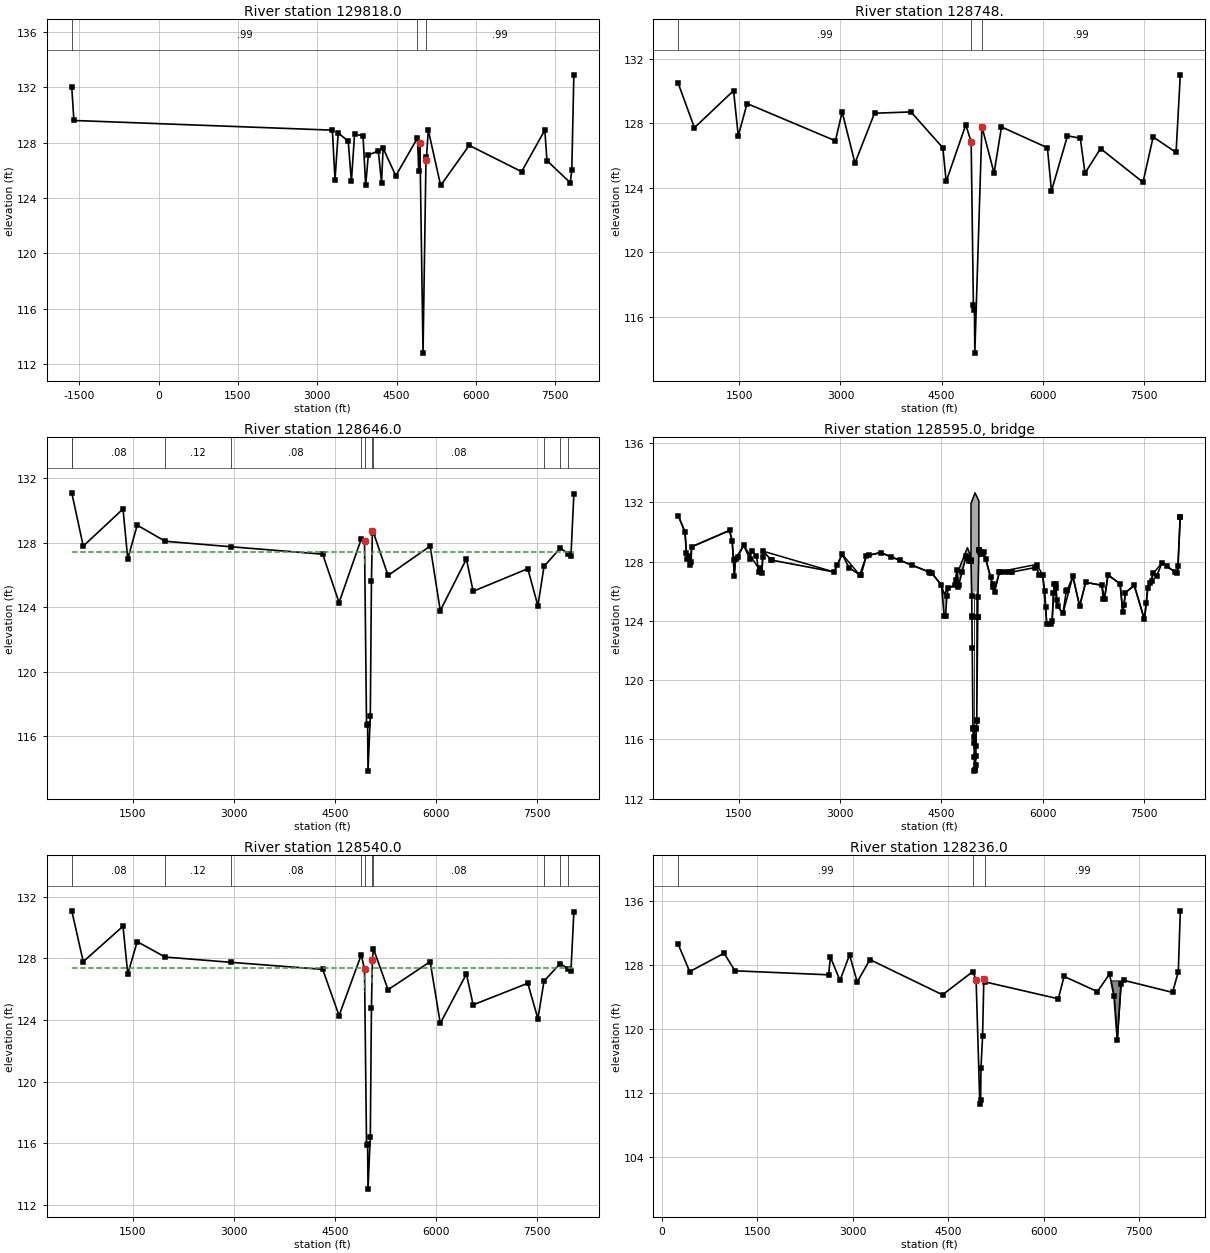
Type RM Length L Ch R = 1 ,129818.0,1094.1,1070,1037.9
BEGIN DESCRIPTION:
Cross Section E100-00-00-X99
END DESCRIPTION:
XS GIS Cut Line= 5
      3039434.02     13907551.77      3039316.03     13901148.08
      3039304.53     13900684.33      3039254.65     13899334.09
       3038716.8     13898174.02
#Sta/Elev= 30
 -1644.9     132 -1604.9   129.6  3285.1   128.9  3335.1   125.3  3395.1   128.7
  3585.1   128.1  3645.1   125.2  3705.1   128.6  3865.1   128.5  3915.1   124.9
  3965.1   127.1  4155.1   127.4  4215.1   125.1  4245.1   127.6  4485.1   125.6
  4895.4  128.33  4918.9  125.97  4940.8  127.98  5000.4  112.78    5056  126.76
    5066  126.98  5099.9   128.9  5333.8   124.9  5873.8   127.8  6864.9   125.9
  7304.9   128.9  7344.9   126.7  7784.9   125.1  7814.9     126  7853.6   132.9
#Mann= 3 ,-1 , 0
 -1644.9     .99       0  4895.4     .04       0    5066     .99       0
Bank Sta=4940.8,5056
XS Rating Curve= 0 ,0
Exp/Cntr=0.3,0.1

Type RM Length L Ch R = 1 ,128748. ,102.1,102,100.7
BEGIN DESCRIPTION:
Wortham - U\S - XS 4
END DESCRIPTION:
XS GIS Cut Line= 6
      3040743.09     13904873.07      3040613.96     13901112.81
      3040278.85     13900498.77      3040137.11      13900145.2
      3040043.02     13899222.53      3039302.95     13897722.39
#Sta/Elev= 30
     595  130.48     835  127.73    1415  130.03    1485  127.22    1615  129.23
    2925  126.92    3025  128.71    3215  125.54    3505  128.63    4045  128.71
  4517.5  126.49  4567.5   124.4  4857.5  127.91  4937.5  126.86 4970.67  116.73
 4985.95  116.46 4991.73  113.76    5097   127.8    5277  124.92    5387  127.78
    6068  126.49    6128  123.81  6365.4  127.23  6555.4  127.08  6625.4  124.92
  6855.4  126.44  7485.4  124.35  7635.4  127.16  7975.4   126.2  8038.2  131.01
#Mann= 3 ,-1 , 0
     595     .99       0  4937.5     .04       0    5097     .99       0
Bank Sta=4937.5,5097
XS Rating Curve= 0 ,0
Exp/Cntr=0.5,0.3

Type RM Length L Ch R = 1 ,128646.0,107,106,105.4
BEGIN DESCRIPTION:
Upstream Section of Bridge/Culvert/Weir
END DESCRIPTION:
XS GIS Cut Line= 6
      3040822.33     13904807.98       3040693.2     13901047.72
      3040358.09     13900433.69      3040216.35     13900080.11
      3040122.26     13899157.44      3039382.19      13897657.3
#Sta/Elev= 30
   599.5  131.09   769.5  127.79  1359.5  130.09  1429.5  126.99  1569.5  129.09
  1984.1  128.09  2955.6  127.75  4319.5  127.29    4562  124.29  4890.8  128.23
  4939.3  128.12  4969.3  116.72  4985.2  116.77  4990.9  113.85  5025.1  117.25
  5042.1  125.62  5056.2  128.74  5071.7  128.63  5288.7  125.97  5912.5  127.79
  6062.5  123.79  6449.9  126.99  6549.9  124.99  7359.9  126.39  7509.9  124.09
  7600.6  126.53  7841.7  127.67  7958.4  127.32  7999.9  127.19  8042.7  130.99
#Mann= 11 , 1 , 0
   599.5     .99       0   599.5     .08       0  1984.1     .12       0
  2955.6     .08       0  4890.8     .04       0  4939.3     .04       0
  5056.2     .04       0  5071.7     .08       0  7600.6     .05       0
  7841.7     .04       0  7958.4     .05       0
#XS Ineff= 2 , 0
       0  4943.2   127.4  5049.4       0   127.4
Permanent Ineff=
       F       F
Bank Sta=4939.3,5056.2
XS Rating Curve= 0 ,0
Exp/Cntr=0.5,0.3

Type RM Length L Ch R = 3 ,128595.0,,,
BEGIN DESCRIPTION:
WORTHAM*** SEE NOTE ***
Structure ID: E100-00-00-58
Energy was the only low flow method that gave reasonable output for both the multiple profiles and the floodway runs.
END DESCRIPTION:
Bridge Culvert--1,0,-1,-1, 0
Deck Dist Width WeirC Skew NumUp NumDn MinLoCord MaxHiCord MaxSubmerge Is_Ogee
10,82,2.6,0, 60, 60, , , 0.95, 0, ,,,
   599.5   699.5   729.5   769.5   799.5  1359.5  1399.5  1429.5  1449.5  1569.5
  1839.5  1859.5  2909.5  3029.5  3289.5  3389.5  3599.5    4362    4502    4542
    4602    4702    4732  4749.2  4886.5 4939.59  4939.7 4953.41  4953.5  4999.2
 5039.26 5039.37  5056.4 5056.51    5130  5288.7  5361.5  5912.5  6002.5  6062.5
  6142.5  6172.5  6222.5  6302.5  6449.9  6549.9  6639.9  6879.9  6919.9  6969.9
  7149.9  7189.9  7229.9  7359.9  7509.9  7559.9  7639.9  7769.9  7999.9  8042.7
   131.1     130   128.2   127.8     129   130.1   129.4     127   128.2   129.1
   127.2   128.7   127.3   128.5   127.1   128.4  128.61  127.21  126.41  125.82
  126.21  126.41  127.41  127.36  128.94  128.31  131.91  132.08  132.08  132.64
  132.26  132.26   132.1  128.76  128.63  125.99  127.31  127.81  127.11   123.8
     124   126.5     125   124.5     127     125   126.6   126.4   125.5   127.1
   126.5   124.6   125.9   126.4   124.1   126.2   127.2   127.9   127.2     131
   131.1     130   128.2   127.8     129   130.1   129.4     127   128.2   129.1
   127.2   128.7   127.3   128.5   127.1   128.4   128.6   127.2   126.4   124.3
   126.2   126.4   127.4  126.28  128.27  128.07  128.04  124.32  125.48  126.04
  125.66  124.29  128.75  128.75  128.62  125.98   127.3   127.8   127.1   123.8
     124   126.5     125   124.5     127     125   126.6   126.4   125.5   127.1
   126.5   124.6   125.9   126.4   124.1   126.2   127.2   127.9   127.2     131
   599.5   699.5   729.5   769.5   799.5  1359.5  1399.5  1429.5  1449.5  1569.5
  1839.5  1859.5  2909.5  3029.5  3289.5  3389.5  3599.5    4362    4502    4542
    4602    4702    4732  4749.2  4886.5 4939.59  4939.7 4953.41  4953.5  4999.2
 5039.26 5039.37  5056.4 5056.51    5130  5288.7  5361.5  5912.5  6002.5  6062.5
  6142.5  6172.5  6222.5  6302.5  6449.9  6549.9  6639.9  6879.9  6919.9  6969.9
  7149.9  7189.9  7229.9  7359.9  7509.9  7559.9  7639.9  7769.9  7999.9  8042.7
   131.1     130   128.2   127.8     129   130.1   129.4     127   128.2   129.1
   127.2   128.7   127.3   128.5   127.1   128.4  128.61  127.21  126.41  125.82
  126.21  126.41  127.41  127.36  128.94  128.31  131.91  132.08  132.08  132.64
  132.26  132.26   132.1  128.76  128.63  125.99  127.31  127.81  127.11   123.8
     124   126.5     125   124.5     127     125   126.6   126.4   125.5   127.1
   126.5   124.6   125.9   126.4   124.1   126.2   127.2   127.9   127.2     131
   131.1     130   128.2   127.8     129   130.1   129.4     127   128.2   129.1
   127.2   128.7   127.3   128.5   127.1   128.4   128.6   127.2   126.4   124.3
   126.2   126.4   127.4  126.28  128.27  128.07  128.04  124.32  125.48  126.04
  125.66  124.29  128.75  128.75  128.62  125.98   127.3   127.8   127.1   123.8
     124   126.5     125   124.5     127     125   126.6   126.4   125.5   127.1
   126.5   124.6   125.9   126.4   124.1   126.2   127.2   127.9   127.2     131
Pier Skew, UpSta & Num, DnSta & Num=  ,4981.8, 2 ,4981.8, 2 , 0 , 0 , 0 ,,
     1.3     1.3
  114.82  126.84
     1.3     1.3
  114.07  126.09
Pier Skew, UpSta & Num, DnSta & Num=  ,5012.8, 2 ,5012.8, 2 , 0 , 0 , 0 ,,
     1.3     1.3
  113.86  126.91
     1.3     1.3
  113.11  126.16
Abutment Skew #Up #Dn= , 2 , 2
  4953.3  4969.3
  125.48  116.73
  4953.3  4969.3
  124.73  115.98
Abutment Skew #Up #Dn= , 2 , 2
  5025.2 5039.46
  117.31  125.66
  5025.2 5039.46
  116.56  124.91
BR Coef= 1 , 0 , 0 ,1.25, 0 ,,,0.8,0,2,0,
WSPro=,,,, 1 ,,,, 0 ,,,, 0 ,,,,-1 ,-1 ,-1 , 0 , 0 , 0 , 0 , 0
BR U #Sta/Elev= 145
   599.5   131.1   699.5     130   719.5   128.6   729.5   128.2   759.5   128.4
   769.5   127.8   789.5     128   799.5     129  1359.5   130.1  1399.5   129.4
  1419.5   128.1  1429.5     127  1449.5   128.2  1479.5   128.3  1569.5   129.1
  1659.5   128.2  1689.5   128.7  1759.5   128.4  1789.5   127.3  1809.5   127.6
  1839.5   127.2  1849.5   128.3  1859.5   128.7  1979.5   128.1  1984.1   128.1
  2909.5   127.3  2955.6  127.76  3029.5   128.5  3129.5   127.6  3289.5   127.1
  3309.5   127.1  3389.5   128.4  3423.8  128.43  3599.5   128.6  3750.4  128.33
  3880.4  128.09  4067.2  127.76  4319.5   127.3  4336.5  127.26    4362   127.2
    4502   126.4    4542   124.3    4562   124.3    4582   125.7    4602   126.2
    4702   126.4  4713.4  126.78    4732   127.4  4749.2  126.28  4758.5  126.44
  4807.4   127.3  4870.6   128.4  4886.5  128.27  4890.8  128.24  4911.1  128.07
  4939.3  128.13 4939.59  128.07  4939.7  128.04 4939.81  128.02  4950.5  125.68
 4953.41  124.32  4953.5  124.28  4958.1  122.14  4969.2  116.78  4969.3  116.73
  4976.9  116.19  4981.8  115.76  4985.2  116.78  4987.5  114.81  4990.9  113.86
  4998.7  113.91  4999.2  113.91  5006.6   114.3  5012.5  114.89  5012.8  115.54
  5014.2  116.78  5019.5   116.7  5025.1  117.26  5025.2  117.31 5039.26  124.23
 5039.37  124.29  5042.1  125.63  5056.2  128.75 5056.29  128.75  5056.4  128.75
 5056.51  128.75  5066.7  128.68  5071.7  128.64  5091.6   128.5  5097.3  128.52
    5130  128.62  5156.6  128.18  5228.8  126.98  5258.8  126.48  5268.8  126.31
  5288.7  125.98  5361.5   127.3  5364.4   127.3  5442.5   127.3  5520.1   127.3
  5552.5   127.3  5892.5   127.6  5912.5   127.8  5942.5   127.1  6002.5   127.1
  6032.5     126  6047.4  124.91  6062.5   123.8  6132.5   123.8  6142.5     124
  6162.5   125.9  6172.5   126.5  6192.5   126.5  6202.5   126.2  6212.5   125.4
  6222.5     125  6302.5   124.5  6352.5     126  6369.9   126.1  6449.9     127
  6549.9     125  6639.9   126.6  6879.9   126.4  6899.9   125.5  6919.9   125.5
  6969.9   127.1  7149.9   126.5  7189.9   124.6  7209.9   125.1  7229.9   125.9
  7359.9   126.4  7509.9   124.1  7539.9   125.2  7559.9   126.2  7600.6  126.54
  7619.9   126.7  7639.9   127.2  7689.9     127  7769.9   127.9  7841.7  127.68
  7958.4  127.33  7999.9   127.2  8009.9   127.7  8039.9     131  8042.7     131
BR U #Mann= 11
   599.5     .99   599.5     .08  1984.1     .12  2955.6     .08  4890.8     .04
  4939.3    .035  5056.2     .04  5071.7     .08  7600.6     .05  7841.7     .04
  7958.4     .05
BR U Banks=4939.3,5056.2
BR D #Sta/Elev= 145
   599.5   131.1   699.5     130   719.5   128.6   729.5   128.2   759.5   128.4
   769.5   127.8   789.5     128   799.5     129  1359.5   130.1  1399.5   129.4
  1419.5   128.1  1429.5     127  1449.5   128.2  1479.5   128.3  1569.5   129.1
  1659.5   128.2  1689.5   128.7  1759.5   128.4  1789.5   127.3  1809.5   127.6
  1839.5   127.2  1849.5   128.3  1859.5   128.7  1979.5   128.1  1984.1   128.1
  2909.5   127.3  2955.6  127.76  3029.5   128.5  3129.5   127.6  3289.5   127.1
  3309.5   127.1  3389.5   128.4  3423.8  128.43  3599.5   128.6  3750.4  128.33
  3880.4  128.09  4067.2  127.76  4319.5   127.3  4336.5  127.26    4362   127.2
    4502   126.4    4542   124.3    4562   124.3    4582   125.7    4602   126.2
    4702   126.4  4713.4  126.78    4732   127.4  4749.2  126.28  4758.5  126.44
  4807.4   127.3  4870.6   128.4  4886.5  128.27  4890.8  128.24  4911.1  128.07
  4939.3  128.13 4939.59  128.07  4939.7  128.04 4939.81  128.02  4950.5  125.68
 4953.41  124.32  4953.5  124.28  4958.1  121.39  4969.2  116.03  4969.3  115.98
  4976.9  115.44  4981.8  115.01  4985.2  116.03  4987.5  114.06  4990.9  113.11
  4998.7  113.16  4999.2  113.16  5006.6  113.55  5012.5  114.14  5012.8  114.79
  5014.2  116.03  5019.5  115.95  5025.1  116.51  5025.2  116.56 5039.26  124.23
 5039.37  124.29  5042.1  125.63  5056.2  128.75 5056.29  128.75  5056.4  128.75
 5056.51  128.75  5066.7  128.68  5071.7  128.64  5091.6   128.5  5097.3  128.52
    5130  128.62  5156.6  128.18  5228.8  126.98  5258.8  126.48  5268.8  126.31
  5288.7  125.98  5361.5   127.3  5364.4   127.3  5442.5   127.3  5520.1   127.3
  5552.5   127.3  5892.5   127.6  5912.5   127.8  5942.5   127.1  6002.5   127.1
  6032.5     126  6047.4  124.91  6062.5   123.8  6132.5   123.8  6142.5     124
  6162.5   125.9  6172.5   126.5  6192.5   126.5  6202.5   126.2  6212.5   125.4
  6222.5     125  6302.5   124.5  6352.5     126  6369.9   126.1  6449.9     127
  6549.9     125  6639.9   126.6  6879.9   126.4  6899.9   125.5  6919.9   125.5
  6969.9   127.1  7149.9   126.5  7189.9   124.6  7209.9   125.1  7229.9   125.9
  7359.9   126.4  7509.9   124.1  7539.9   125.2  7559.9   126.2  7600.6  126.54
  7619.9   126.7  7639.9   127.2  7689.9     127  7769.9   127.9  7841.7  127.68
  7958.4  127.33  7999.9   127.2  8009.9   127.7  8039.9     131  8042.7     131
BR D #Mann= 10
   599.5     .08  1984.1     .12  2955.6     .08  4890.8     .04  4939.3    .035
  5056.2     .04  5071.7     .08  7600.6     .05  7841.7     .04  7958.4     .05
BR D Banks=4939.3,5056.2
BC Design=,, 0 ,, 0 ,,,,,,
BC HTab HWMax=131.09
BC Use User HTab Curves=0
BC User HTab FreeFlow(D)= 0

Type RM Length L Ch R = 1 ,128540.0,314.5,304,290.6
BEGIN DESCRIPTION:
Downstream Section of Bridge/Culvert/Weir
END DESCRIPTION:
XS GIS Cut Line= 6
      3040906.52     13904743.91      3040777.43     13900984.82
      3040442.76     13900371.63      3040300.64     13900017.07
      3040206.56      13899094.6      3039466.89     13897595.27
#Sta/Elev= 30
   599.5  131.09   769.5  127.79  1359.5  130.09  1429.5  126.99  1569.5  129.09
  1984.1  128.09  2955.6  127.75  4319.5  127.29    4562  124.29  4890.8  128.23
  4939.3   127.3  4969.3   115.9  4985.2  115.95  4990.9  113.03  5025.1  116.43
  5042.1   124.8  5056.2  127.92  5071.7  128.63  5288.7  125.97  5912.5  127.79
  6062.5  123.79  6449.9  126.99  6549.9  124.99  7359.9  126.39  7509.9  124.09
  7600.6  126.53  7841.7  127.67  7958.4  127.32  7999.9  127.19  8042.7  130.99
#Mann= 10 ,-1 , 0
   599.5     .08       0  1984.1     .12       0  2955.6     .08       0
  4890.8     .04       0  4939.3     .04       0  5056.2     .04       0
  5071.7     .08       0  7600.6     .05       0  7841.7     .04       0
  7958.4     .05       0
#XS Ineff= 2 , 0
       0  4943.2   127.4  5049.4       0   127.4
Permanent Ineff=
       F       F
Bank Sta=4939.3,5056.2
XS Rating Curve= 0 ,0
Exp/Cntr=0.5,0.3

Type RM Length L Ch R = 1 ,128236.0,917,936,962.4
BEGIN DESCRIPTION:
Cross Section E100-00-00-X98
END DESCRIPTION:
XS GIS Cut Line= 6
      3041384.21     13904851.51      3040943.03     13900489.12
       3040535.8     13900041.43      3040459.22     13899891.76
      3040384.11     13898960.95      3039884.07     13897240.79
#Sta/Elev= 30
   260.7   130.6   440.7   127.2   980.7   129.5  1150.7   127.3  2620.7   126.8
  2650.7     129  2800.7   126.1  2950.7   129.3  3070.7   125.9  3270.7   128.7
  4410.7   124.3  4883.4  127.19  4937.6  126.19  4996.1  110.63    5009  111.15
  5013.9  115.15  5039.4  119.14    5059  126.33  5079.1  125.91  6228.7   123.8
  6318.7   126.6  6842.5   124.7  7032.5   126.9  7102.5   124.1  7152.5   118.7
  7212.5   125.7  7262.5   126.1  8022.5   124.6  8112.5   127.2  8143.9   134.8
#Mann= 3 ,-1 , 0
   260.7     .99       0  4883.4     .04       0  5079.1     .99       0
#Block Obstruct= 2 ,-1
    7058  7262.5   126.1    7266  7266.2     100
Bank Sta=4937.6,5059
XS Rating Curve= 0 ,0
Exp/Cntr=0.3,0.1

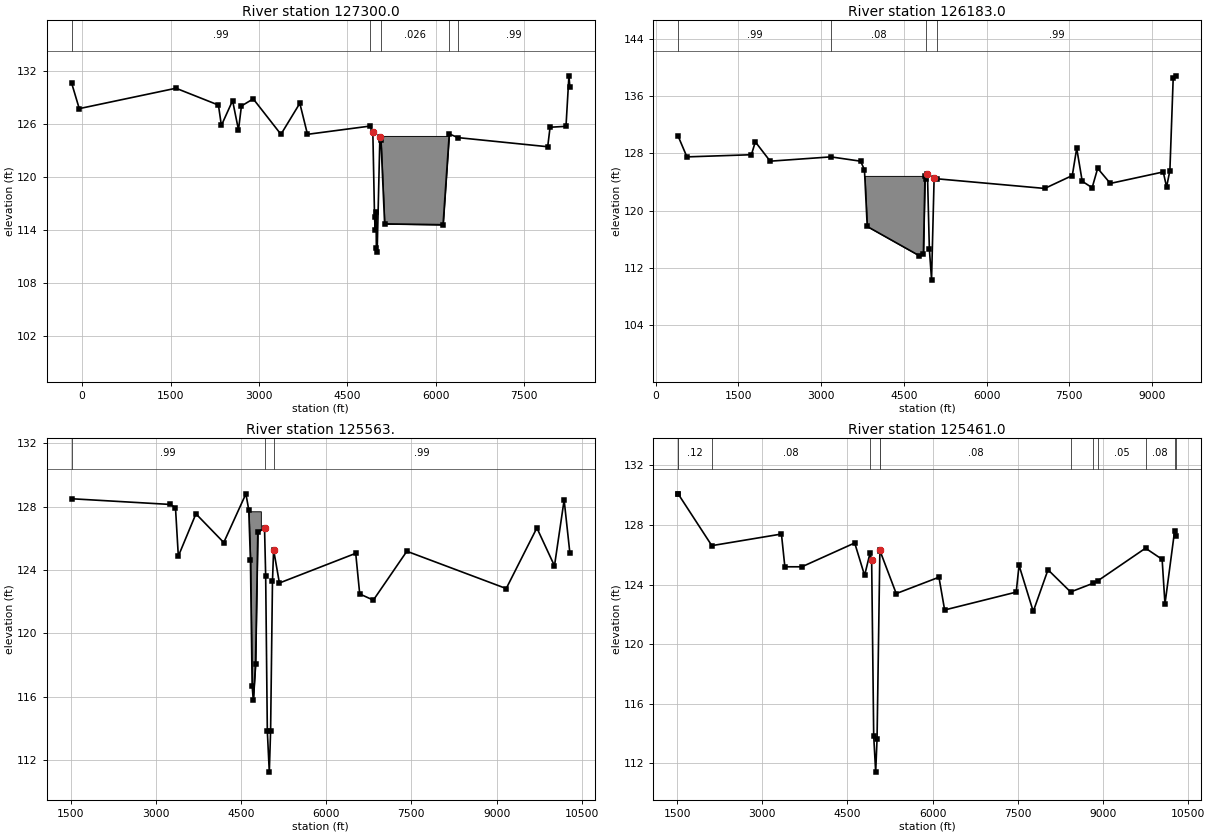
Type RM Length L Ch R = 1 ,127300.0,1095.2,1117,1142.6
BEGIN DESCRIPTION:
Cross Section E100-00-00-X97
END DESCRIPTION:
XS GIS Cut Line= 5
      3042084.28     13904881.51      3041630.45     13900114.96
      3041408.56      13899492.8      3041034.08     13898636.59
       3040284.1     13896710.74
#Sta/Elev= 30
  -178.1   130.6   -48.1   127.7  1591.9     130  2311.9   128.1  2361.9   125.8
  2551.9   128.6  2651.9   125.3  2701.9     128  2901.9   128.8  3371.9   124.8
  3691.9   128.3  3821.9   124.8  4882.4  125.73  4930.1  125.01  4959.2  115.42
  4972.1  113.95  4984.6  116.01  4989.7  111.98  5003.1   111.5  5049.6  124.53
  5066.9  124.19    5130   114.7  6120.6   114.6    6226  124.85  6371.6  124.43
  7895.1   123.4  7935.1   125.6  8205.1   125.7  8255.1   131.4  8271.8   130.1
#Mann= 5 ,-1 , 0
  -178.1     .99       0  4882.4     .04       0  5066.9    .026       0
    6226     .05       0  6371.6     .99       0
#Block Obstruct= 2 ,-1
  5058.3    6226  124.62  6226.2  6226.4     100
Bank Sta=4930.1,5049.6
XS Rating Curve= 0 ,0
Exp/Cntr=0.3,0.1

Type RM Length L Ch R = 1 ,126183.0,618.8,620,621.3
BEGIN DESCRIPTION:
Cross Section E100-00-00-X96
END DESCRIPTION:
XS GIS Cut Line= 4
      3042560.57      13904220.2      3042591.97     13899945.28
      3042627.37     13898601.31      3040771.73     13895729.94
#Sta/Elev= 30
   405.7   130.4   565.7   127.5  1735.7   127.8  1805.7   129.6  2075.7   126.9
  3175.7   127.5  3715.7   126.9  3785.7   125.7  3835.7   117.8  4782.7  113.71
  4854.5  113.93  4883.6   124.8  4900.7  124.35  4928.3  125.11  4962.5  114.68
  5002.5  110.38    5049  124.53  5093.3  124.45  7055.2   123.1  7555.2   124.9
  7635.2   128.7  7735.2   124.1  7915.2   123.2  8015.2   125.9  8245.2   123.8
  9205.2   125.4  9265.2   123.3  9325.2   125.6  9385.2   138.5    9444   138.8
#Mann= 4 ,-1 , 0
   405.7     .99       0  3175.7     .08       0  4900.7     .04       0
  5093.3     .99       0
#Block Obstruct= 2 ,-1
    3790  4897.2  124.85  4897.5  4897.7     100
Bank Sta=4928.3,5049
XS Rating Curve= 0 ,0
Exp/Cntr=0.3,0.1

Type RM Length L Ch R = 1 ,125563. ,101,102,102.2
BEGIN DESCRIPTION:
Addicks - Fairbanks ( Neldrid ) - U\S - XS 4
END DESCRIPTION:
XS GIS Cut Line= 6
      3043091.92     13903128.47      3043224.16     13899551.03
      3043243.87     13899290.16      3043303.69     13899034.56
      3043354.44     13898115.49      3040929.21     13895252.72
#Sta/Elev= 30
  1515.3  128.49  3255.3  128.13  3345.3  127.92  3395.3  124.87  3705.3  127.54
  4195.3  125.73  4585.3   128.8  4635.3   127.8  4665.3  124.62  4695.3  116.69
  4715.3   115.8  4755.3  118.08  4795.3  126.39  4913.4  126.66  4933.4  123.65
 4962.61  113.85 4997.43  111.26 5020.45  113.88  5053.4   123.3  5073.4  125.27
  5175.2  123.18  6519.3  125.05  6589.8  122.49  6829.8   122.1  7419.8  125.18
  9169.8  122.83  9709.8  126.65 10019.8  124.26 10189.8  128.41 10291.8  125.04
#Mann= 3 ,-1 , 0
  1515.3     .99       0  4913.4     .04       0  5073.4     .99       0
#Block Obstruct= 1 ,-1
 4606.06 4848.48   127.7
Bank Sta=4913.4,5073.4
XS Rating Curve= 0 ,0
Exp/Cntr=0.5,0.3

Type RM Length L Ch R = 1 ,125461.0,119.5,117,116.5
BEGIN DESCRIPTION:
Upstream Section of Bridge/Culvert/Weir
END DESCRIPTION:
XS GIS Cut Line= 6
       3043193.8     13903134.13      3043326.04     13899556.69
      3043345.74     13899295.82      3043405.57     13899040.22
      3043456.32     13898121.15      3041031.09     13895258.38
#Sta/Elev= 30
    1517  130.09  1517.1  130.09  2110.9  126.61  3337.1  127.39  3397.1  125.19
  3697.1  125.19  4627.1  126.79  4801.4  124.61  4896.6   126.1  4925.7  125.66
  4961.9  113.83  4996.6   111.4  5020.9  113.64  5070.7  126.29  5074.4  126.25
  5358.6  123.39  6111.1  124.49  6211.1  122.29  7471.6  123.49  7521.6  125.29
  7771.6  122.19  8031.6  124.99  8429.9   123.5  8823.9  124.08  8913.3  124.26
  9749.3  126.44 10041.6  125.69 10091.6  122.69 10260.2  127.56 10293.6  127.29
#Mann= 12 , 1 , 0
    1517     .99       0  1517.1     .12       0  2110.9     .08       0
  4896.6    .035       0  5070.7     .04       0  5074.4     .08       0
  8429.9     .05       0  8823.9     .08       0  8913.3     .05       0
  9749.3     .08       0 10260.2      .1       0 10293.6     .99       0
#XS Ineff= 2 , 0
       0 4918.34  125.66 5074.57       0  126.19
Permanent Ineff=
       F       F
Bank Sta=4925.7,5070.7
XS Rating Curve= 0 ,0
Exp/Cntr=0.5,0.3