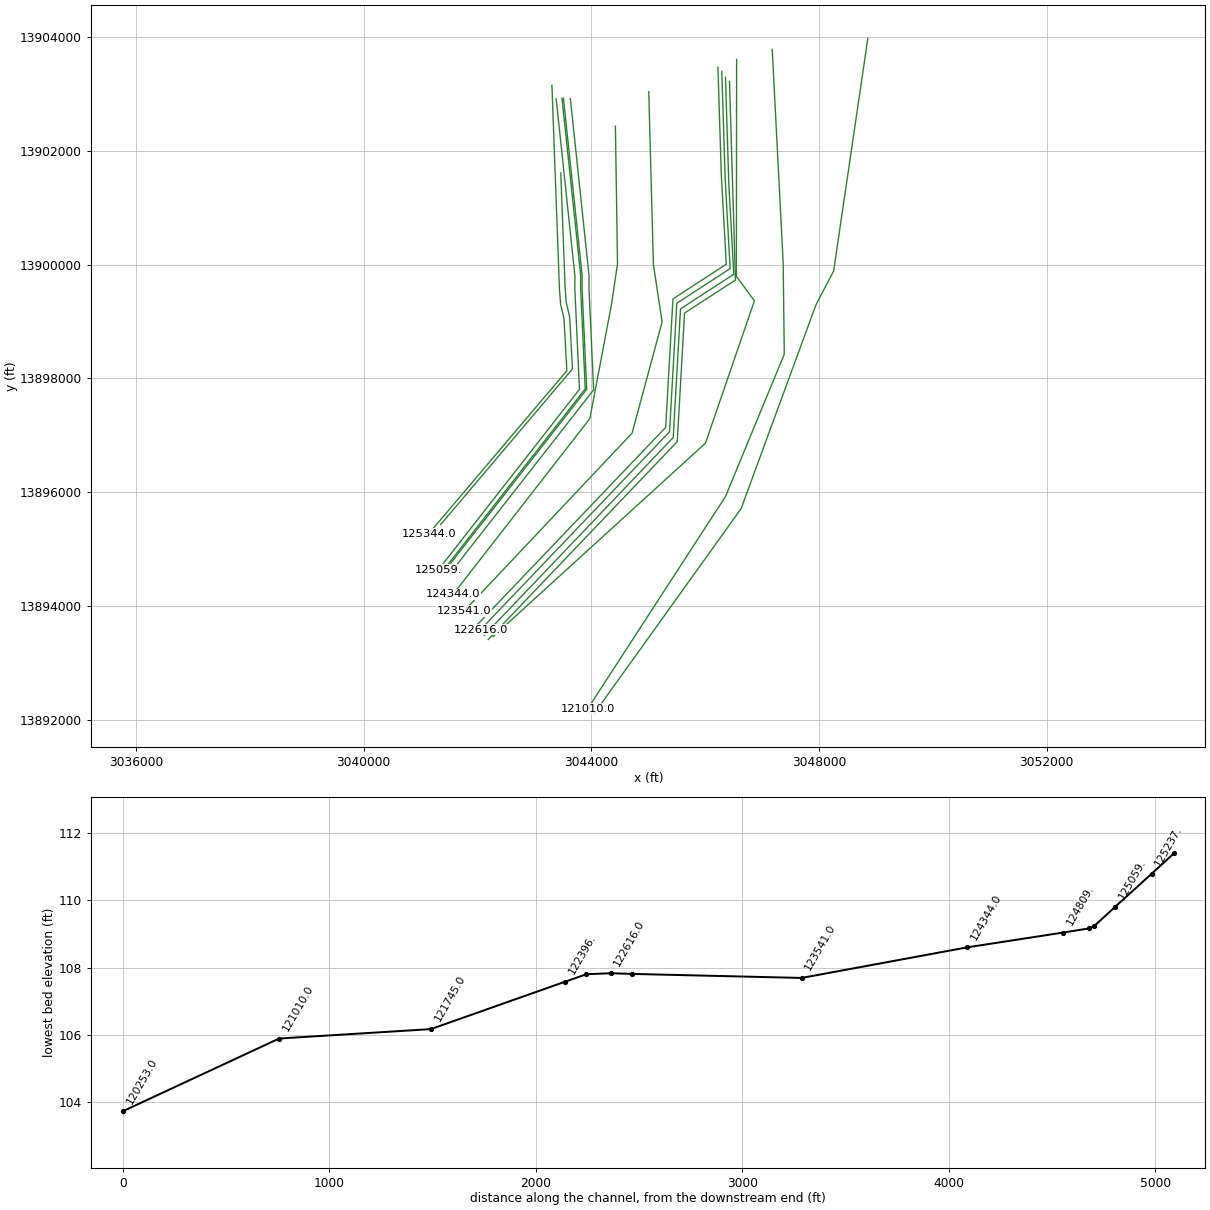
HEC-RAS study E100-00-00.prj: E100-00-00

--- E100-00-00.g02 (geometry) --- (continued)

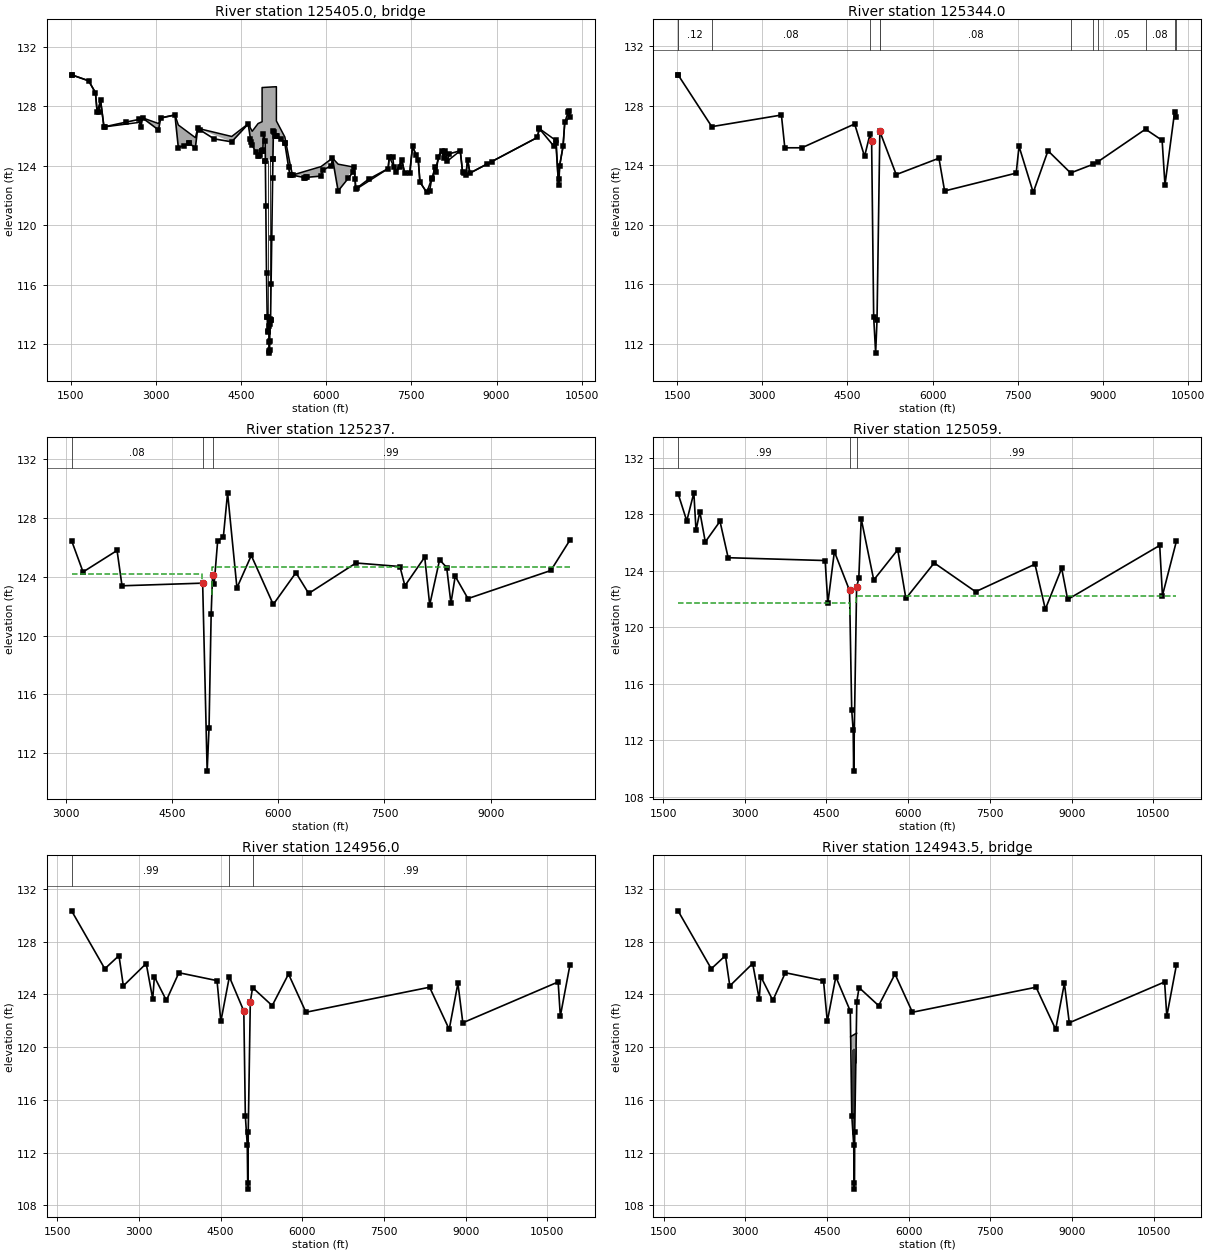
Type RM Length L Ch R = 3 ,125405.0,,,
BEGIN DESCRIPTION:
ADDICKS-FAIRBANKS(N ELDRIDGE)
Structure ID: E100-00-00-57
END DESCRIPTION:
Bridge Culvert--1,0,-1,-1, 0
Deck Dist Width WeirC Skew NumUp NumDn MinLoCord MaxHiCord MaxSubmerge Is_Ogee
10,92,2.6,0, 60, 60, , , 0.95, 0, ,,,
    1517  1817.1  1937.1  1967.1  2027.1  2087.1  2737.1  2767.1  3047.1  3087.1
  3337.1  3397.1  3697.1  3737.1  4337.1  4627.1  4697.4  4801.4 4871.89    4872
  4896.6  4925.7 4929.31  5062.1  5070.7  5123.6 5123.71  5272.9  5358.6    5408
  5911.1  6111.1  6211.1  6491.1  6521.1  7091.6  7111.6  7231.6  7331.6  7381.6
  7471.6  7521.6  7621.6  7651.6  7771.6  8031.6  8131.6  8361.6  8401.6  8461.6
  8491.6  8531.6  9721.6  9751.6 10041.6 10091.6 10111.6 10171.6 10201.6 10293.6
   130.1   129.7   128.9   127.6   128.4   126.6  126.92  127.21  126.83  127.21
  127.41  126.73  125.88  126.51  125.96  126.81  126.31  126.83  126.95  129.25
  129.25  129.26  129.26  129.29  129.29   129.3     127  125.92  124.23  123.37
  123.94  124.51   124.1   123.9   122.4   123.8   124.6   123.6   124.4   123.5
   123.5   125.3   124.4   122.9   122.2     125   124.3     125   123.6   123.4
   124.4   123.5   125.9   126.5   125.7   122.7     124   125.3   126.9   127.3
   130.1   129.7   128.9   127.6   128.4   126.6   126.6   127.2   126.4   127.2
   127.4   125.2   125.2   126.5   125.6   126.8  125.37  124.62  124.97  124.97
  126.11  125.67  124.33  124.47   126.3  125.99  125.99  125.49   123.4  123.36
   123.3   124.5   122.3   123.9   122.4   123.8   124.6   123.6   124.4   123.5
   123.5   125.3   124.4   122.9   122.2     125   124.3     125   123.6   123.4
   124.4   123.5   125.9   126.5   125.7   122.7     124   125.3   126.9   127.3
    1517  1817.1  1937.1  1967.1  2027.1  2087.1  2737.1  2767.1  3047.1  3087.1
  3337.1  3397.1  3697.1  3737.1  4337.1  4627.1  4697.4  4801.4 4871.89    4872
  4896.6  4925.7 4929.31  5062.1  5070.7  5123.6 5123.71  5272.9  5358.6    5408
  5911.1  6111.1  6211.1  6491.1  6521.1  7091.6  7111.6  7231.6  7331.6  7381.6
  7471.6  7521.6  7621.6  7651.6  7771.6  8031.6  8131.6  8361.6  8401.6  8461.6
  8491.6  8531.6  9721.6  9751.6 10041.6 10091.6 10111.6 10171.6 10201.6 10293.6
  130.11  129.71  128.91  127.61  128.41  126.61  126.92  127.21  126.83  127.21
  127.41  126.73  125.88  126.51  125.96  126.81  126.31  126.83  126.95  129.25
  129.25  129.26  129.26  129.29  129.29   129.3     127  125.92  124.23  123.37
  123.94  124.51   124.1  123.91  122.41  123.81  124.61  123.61  124.41  123.51
  123.51  125.31  124.41  122.91  122.21  125.01  124.31  125.01  123.61  123.41
  124.41  123.51  125.91  126.51  125.71  122.71  124.01  125.31  126.91  127.31
  130.11  129.71  128.91  127.61  128.41  126.61  126.61  127.21  126.41  127.21
  127.41  125.21  125.21  126.51  125.61  126.81  125.38  124.63  124.98  124.98
  126.12  125.68  124.34  124.48  126.31     126     126   125.5  123.41  123.37
  123.31  124.51  122.31  123.91  122.41  123.81  124.61  123.61  124.41  123.51
  123.51  125.31  124.41  122.91  122.21  125.01  124.31  125.01  123.61  123.41
  124.41  123.51  125.91  126.51  125.71  122.71  124.01  125.31  126.91  127.31
Pier Skew, UpSta & Num, DnSta & Num=  ,4970.3, 2 ,4970.3, 2 , 0 , 0 , 0 ,,
     1.5     1.5
  111.83  125.47
     1.5     1.5
  111.84  125.48
Pier Skew, UpSta & Num, DnSta & Num=  ,5014, 2 ,5014, 2 , 0 , 0 , 0 ,,
     1.5     1.5
  112.62  125.48
     1.5     1.5
  112.63  125.49
Abutment Skew #Up #Dn= , 2 , 2
  4929.2    4962
  124.46  113.82
  4929.2    4962
  124.47  113.83
Abutment Skew #Up #Dn= , 2 , 2
  5020.9 5062.19
  113.65  124.49
  5020.9 5062.19
  113.66   124.5
BR Coef= 1 , 1 , 0 ,1.25, 0 ,,,0.8,0,1.2,0,
WSPro=,,,, 1 ,,,, 0 ,,,, 0 ,,,,-1 ,-1 ,-1 , 0 , 0 , 0 , 0 , 0
BR U #Sta/Elev= 140
    1517   130.1  1517.1   130.1  1817.1   129.7  1937.1   128.9  1967.1   127.6
  1997.1   127.6  2027.1   128.4  2087.1   126.6  2110.9  126.62  2472.9  126.92
  2697.1   127.1  2737.1   126.6  2767.1   127.2  3047.1   126.4  3087.1   127.2
  3337.1   127.4  3397.1   125.2  3492.9  125.35  3582.9  125.49  3587.1   125.5
  3697.1   125.2  3737.1   126.5  3772.9  126.41  4027.1   125.8  4337.1   125.6
  4627.1   126.8  4667.1   125.8  4670.1  125.57  4697.4  125.37  4759.9  124.92
  4801.4  124.62  4821.7  124.66  4840.2  124.69 4871.89  124.97    4872  124.97
 4872.11  124.97  4884.7  125.08  4896.6  126.11  4925.7  125.67 4929.31  124.33
  4929.4  124.29  4937.4  121.32  4949.6  116.78  4961.9  113.84    4962  113.82
  4970.3  112.83  4981.7  112.87  4990.1  113.26  4994.1  112.15  4996.6  111.41
  5001.2  111.58  5004.4  111.63    5006  112.21    5010  113.36  5013.6   113.7
    5014  113.62  5020.8  113.65  5020.9  113.65  5029.6  116.04  5042.6  119.13
  5056.1  123.19 5061.99  124.44  5062.1  124.47  5070.7   126.3  5074.4  126.26
  5096.8  125.99 5123.49  125.99  5123.6  125.99 5123.71  125.99    5138  125.99
  5200.6  125.76    5269   125.5  5272.9  125.49    5338   123.9  5358.6   123.4
    5388  123.38    5408  123.36    5618   123.2  5621.1   123.2  5645.4  123.21
  5665.4  123.22  5911.1   123.3  5941.1   123.7  6091.1     124  6111.1   124.5
  6211.1   122.3  6387.4  123.15  6481.1   123.6  6491.1   123.9  6511.1   123.1
  6521.1   122.4  6541.6   122.5  6751.6   123.1  7091.6   123.8  7111.6   124.6
  7171.6   124.6  7191.6   123.9  7231.6   123.6  7301.6   123.9  7331.6   124.4
  7381.6   123.5  7471.6   123.5  7521.6   125.3  7581.6   124.7  7621.6   124.4
  7651.6   122.9  7771.6   122.2  7821.6   122.3  7861.6   123.2  7871.6   123.1
  7911.6   123.9  7941.6   123.6  7971.6   124.6  8031.6     125  8071.6   124.5
  8101.6     125  8131.6   124.3  8171.6   124.8  8361.6     125  8401.6   123.6
  8429.9  123.51  8461.6   123.4  8491.6   124.4  8531.6   123.5  8823.9  124.09
  8913.3  124.27  9721.6   125.9  9749.3  126.45  9751.6   126.5 10011.6   125.3
 10041.6   125.7 10051.6   125.5 10091.6   122.7 10101.6   123.1 10111.6     124
 10171.6   125.3 10201.6   126.9 10260.2  127.57 10271.6   127.7 10293.6   127.3
BR U #Mann= 12
    1517     .99  1517.1     .12  2110.9     .08  4896.6    .035  5070.7     .04
  5074.4     .08  8429.9     .05  8823.9     .08  8913.3     .05  9749.3     .08
 10260.2      .1 10293.6     .99
BR U Banks=4896.6,5070.7
BR D #Sta/Elev= 140
    1517  130.11  1517.1  130.11  1817.1  129.71  1937.1  128.91  1967.1  127.61
  1997.1  127.61  2027.1  128.41  2087.1  126.61  2110.9  126.63  2472.9  126.93
  2697.1  127.11  2737.1  126.61  2767.1  127.21  3047.1  126.41  3087.1  127.21
  3337.1  127.41  3397.1  125.21  3492.9  125.36  3582.9   125.5  3587.1  125.51
  3697.1  125.21  3737.1  126.51  3772.9  126.42  4027.1  125.81  4337.1  125.61
  4627.1  126.81  4667.1  125.81  4670.1  125.58  4697.4  125.38  4759.9  124.93
  4801.4  124.63  4821.7  124.67  4840.2   124.7 4871.89  124.98    4872  124.98
 4872.11  124.98  4884.7  125.09  4896.6  126.12  4925.7  125.68 4929.31  124.34
  4929.4   124.3  4937.4  121.33  4949.6  116.79  4961.9  113.85    4962  113.83
  4970.3  112.84  4981.7  112.88  4990.1  113.27  4994.1  112.16  4996.6  111.42
  5001.2  111.59  5004.4  111.64    5006  112.22    5010  113.37  5013.6  113.71
    5014  113.63  5020.8  113.66  5020.9  113.66  5029.6  116.05  5042.6  119.14
  5056.1   123.2 5061.99  124.45  5062.1  124.48  5070.7  126.31  5074.4  126.27
  5096.8     126 5123.49     126  5123.6     126 5123.71     126    5138     126
  5200.6  125.77    5269  125.51  5272.9   125.5    5338  123.91  5358.6  123.41
    5388  123.39    5408  123.37    5618  123.21  5621.1  123.21  5645.4  123.22
  5665.4  123.23  5911.1  123.31  5941.1  123.71  6091.1  124.01  6111.1  124.51
  6211.1  122.31  6387.4  123.16  6481.1  123.61  6491.1  123.91  6511.1  123.11
  6521.1  122.41  6541.6  122.51  6751.6  123.11  7091.6  123.81  7111.6  124.61
  7171.6  124.61  7191.6  123.91  7231.6  123.61  7301.6  123.91  7331.6  124.41
  7381.6  123.51  7471.6  123.51  7521.6  125.31  7581.6  124.71  7621.6  124.41
  7651.6  122.91  7771.6  122.21  7821.6  122.31  7861.6  123.21  7871.6  123.11
  7911.6  123.91  7941.6  123.61  7971.6  124.61  8031.6  125.01  8071.6  124.51
  8101.6  125.01  8131.6  124.31  8171.6  124.81  8361.6  125.01  8401.6  123.61
  8429.9  123.52  8461.6  123.41  8491.6  124.41  8531.6  123.51  8823.9   124.1
  8913.3  124.28  9721.6  125.91  9749.3  126.46  9751.6  126.51 10011.6  125.31
 10041.6  125.71 10051.6  125.51 10091.6  122.71 10101.6  123.11 10111.6  124.01
 10171.6  125.31 10201.6  126.91 10260.2  127.58 10271.6  127.71 10293.6  127.31
BR D #Mann= 12
    1517     .99  1517.1     .12  2110.9     .08  4896.6    .035  5070.7     .04
  5074.4     .08  8429.9     .05  8823.9     .08  8913.3     .05  9749.3     .08
 10260.2      .1 10293.6     .99
BR D Banks=4896.6,5070.7
BC Design=,, 0 ,, 0 ,,,,,,
BC HTab HWMax=130.09
BC Use User HTab Curves=0
BC User HTab FreeFlow(D)= 0

Type RM Length L Ch R = 1 ,125344.0,108,107,101
BEGIN DESCRIPTION:
Downstream Section of Bridge/Culvert/Weir
END DESCRIPTION:
XS GIS Cut Line= 6
      3043309.37      13903146.2      3043441.62     13899568.63
      3043461.36     13899307.31      3043521.17     13899051.75
      3043571.79     13898135.11      3041147.85     13895273.86
#Sta/Elev= 30
    1517  130.08  1517.1  130.08  2110.9   126.6  3337.1  127.38  3397.1  125.18
  3697.1  125.18  4627.1  126.78  4801.4   124.6  4896.6  126.09  4925.7  125.65
  4961.9  113.82  4996.6  111.39  5020.9  113.63  5070.7  126.28  5074.4  126.24
  5358.6  123.38  6111.1  124.48  6211.1  122.28  7471.6  123.48  7521.6  125.28
  7771.6  122.18  8031.6  124.98  8429.9  123.49  8823.9  124.07  8913.3  124.25
  9749.3  126.43 10041.6  125.68 10091.6  122.68 10260.2  127.55 10293.6  127.28
#Mann= 12 , 1 , 0
    1517     .99       0  1517.1     .12       0  2110.9     .08       0
  4896.6    .035       0  5070.7     .04       0  5074.4     .08       0
  8429.9     .05       0  8823.9     .08       0  8913.3     .05       0
  9749.3     .08       0 10260.2      .1       0 10293.6     .99       0
#XS Ineff= 2 , 0
       0 4923.42  125.68 5073.04       0  126.12
Permanent Ineff=
       F       F
Bank Sta=4925.7,5070.7
XS Rating Curve= 0 ,0
Exp/Cntr=0.5,0.3

Type RM Length L Ch R = 1 ,125237. ,182.3,178,172.7
BEGIN DESCRIPTION:
Addicks - Fairbanks ( Neldrid ) - D\S - XS 1
END DESCRIPTION:
XS GIS Cut Line= 6
      3043464.98      13901610.2      3043540.67     13899599.76
      3043560.41     13899338.44      3043620.22     13899082.88
      3043670.84     13898166.24 3041356.786308813895434.7012144
#Sta/Elev= 30
  3084.1  126.46  3245.9  124.33  3725.9  125.79  3795.9  123.39    4934  123.57
 4997.61  110.79    5024  113.72    5054  121.45    5074  124.11  5095.9  123.49
  5145.9  126.44  5225.9   126.7  5285.9  129.71    5418  123.25  5620.5  125.45
  5930.5  122.12  6250.5  124.28  6430.5  122.87  7098.5  124.94  7718.5   124.7
  7788.5  123.39  8068.5  125.34  8138.5  122.09  8278.5  125.16  8378.5  124.63
  8438.5   122.2  8498.5  124.04  8678.5  122.52  9848.5  124.43 10118.5   126.5
#Mann= 3 ,-1 , 0
  3084.1     .08       0    4934     .04       0    5074     .99       0
#XS Ineff= 2 , 0
        4926.594124.19635063.871        124.6584
Permanent Ineff=
       F       F
Bank Sta=4934,5074
XS Rating Curve= 0 ,0
Exp/Cntr=0.3,0.1

Type RM Length L Ch R = 1 ,125059. ,101.8,103,104
BEGIN DESCRIPTION:
E100-00-00-PL56A-U/S - XS 4
END DESCRIPTION:
XS GIS Cut Line= 5
      3043384.57     13902910.28      3043713.32     13899799.55
      3043710.87     13899604.93      3043792.85     13897806.78
      3041311.76     13894634.75
#Sta/Elev= 30
  1775.2  129.48  1935.2  127.54  2065.2  129.53  2105.2  126.86  2175.2  128.19
  2275.2  126.05  2545.2  127.51  2695.2  124.93  4475.2  124.73  4525.2   121.7
  4645.2  125.36  4923.3  122.61  4963.3  114.13 4990.25   112.7 4999.29   109.8
  5053.3  122.84  5093.3  123.47  5137.9  127.69  5367.9  123.35  5807.9  125.49
  5957.9  122.04  6477.9  124.56  7237.9  122.52  8327.9  124.47  8517.9  121.28
  8817.9  124.18  8927.9  121.97 10617.9   125.8 10667.9  122.25   10925  126.11
#Mann= 3 ,-1 , 0
  1775.2     .99       0  4923.3     .04       0  5053.3     .99       0
#XS Ineff= 2 , 0
        4931.875121.72825048.617         122.227
Permanent Ineff=
       F       F
Bank Sta=4923.3,5053.3
XS Rating Curve= 0 ,0
Exp/Cntr=0.5,0.3

Type RM Length L Ch R = 1 ,124956.0,26,25,24
BEGIN DESCRIPTION:
Upstream Section of Bridge/Culvert/Weir
END DESCRIPTION:
XS GIS Cut Line= 5
      3043486.45     13902918.77      3043815.19     13899808.04
      3043812.75     13899613.42      3043894.73     13897815.27
      3041413.64     13894643.24
#Sta/Elev= 30
  1765.8  130.35  2375.8  125.95  2635.9  126.95  2715.8  124.65  3135.9  126.35
  3255.8  123.65  3285.8  125.35  3505.8  123.55  3735.8  125.65  4435.9  125.05
  4505.9  121.95  4662.4  125.34 4927.87  122.74 4955.67  114.79 4991.17  112.55
 5000.27  109.22 5005.17  109.69 5009.07  113.59 5046.97  123.45  5089.2  124.52
  5448.6  123.15  5748.6  125.55  6068.6  122.65  8338.6  124.55  8698.6  121.35
  8858.5  124.85  8948.5  121.85 10698.5  124.95 10738.6  122.35 10915.7  126.25
#Mann= 3 ,-1 , 0
  1765.8     .99       0  4662.4     .04       0  5089.2     .99       0
#XS Ineff= 2 , 0
       0 4934.93   120.3 5039.79       0  120.82
Permanent Ineff=
       F       F
Bank Sta=4927.87,5046.97
XS Rating Curve= 0 ,0
Exp/Cntr=0.5,0.3

Type RM Length L Ch R = 3 ,124943.5,,,
BEGIN DESCRIPTION:
PL1_E100-00-00-PL56A
END DESCRIPTION:
Bridge Culvert--1,0,-1,-1, 0
Deck Dist Width WeirC Skew NumUp NumDn MinLoCord MaxHiCord MaxSubmerge Is_Ogee
10,5,2.6,0, 24, 24, , , 0.95, 0, ,,,
  4933.9 4941.77 4941.88 4941.97 4955.67 4958.17 4980.97 4991.17 4992.67 4993.77
 4994.67 5000.27 5003.47 5005.17 5006.17 5006.67 5009.07 5016.77 5029.07 5031.87
 5039.56 5039.67 5039.77    5044
  120.78  120.82  120.82  120.82  120.85  120.86  120.91  120.94  120.94  120.94
  120.94  120.96  120.96  120.97  120.97  120.97  120.98     121  121.03  121.03
  121.05  121.05  121.05  121.05
  119.78  119.82  119.82  119.82  119.85  119.86  119.91  119.94  119.94  119.94
  119.94  119.96  119.96  119.97  119.97  119.97  119.98     120  120.03  120.03
  120.05  120.05  120.05  120.05
  4933.9 4941.77 4941.88 4941.97 4955.67 4958.17 4980.97 4991.17 4992.67 4993.77
 4994.67 5000.27 5003.47 5005.17 5006.17 5006.67 5009.07 5016.77 5029.07 5031.87
 5039.56 5039.67 5039.77    5044
  120.78  120.82  120.82  120.82  120.85  120.86  120.91  120.94  120.94  120.94
  120.94  120.96  120.96  120.97  120.97  120.97  120.98     121  121.03  121.03
  121.05  121.05  121.05  121.05
  119.78  119.82  119.82  119.82  119.85  119.86  119.91  119.94  119.94  119.94
  119.94  119.96  119.96  119.97  119.97  119.97  119.98     120  120.03  120.03
  120.05  120.05  120.05  120.05
Pier Skew, UpSta & Num, DnSta & Num=  ,4958.2, 2 ,4958.2, 2 , 0 , 0 , 0 ,,
       1       1
  114.65  120.86
       1       1
  114.65  120.86
Pier Skew, UpSta & Num, DnSta & Num=  ,4981, 2 ,4981, 2 , 0 , 0 , 0 ,,
       1       1
  110.86  120.91
       1       1
  110.86  120.91
Pier Skew, UpSta & Num, DnSta & Num=  ,5003.5, 2 ,5003.5, 2 , 0 , 0 , 0 ,,
       1       1
   111.2  120.96
       1       1
   111.2  120.96
Pier Skew, UpSta & Num, DnSta & Num=  ,5029.1, 2 ,5029.1, 2 , 0 , 0 , 0 ,,
       1       1
  116.03  121.03
       1       1
  116.03  121.03
BR Coef= 1 , 1 , 0 ,1.25, 0 ,,,0.8,0,2,0,
WSPro=,,,, 1 ,,,, 0 ,,,, 0 ,,,,-1 ,-1 ,-1 , 0 , 0 , 0 , 0 , 0
BC Design=,, 0 ,, 0 ,,,,,,
BC HTab HWMax=130.35
BC Use User HTab Curves=0
BC User HTab FreeFlow(D)= 0

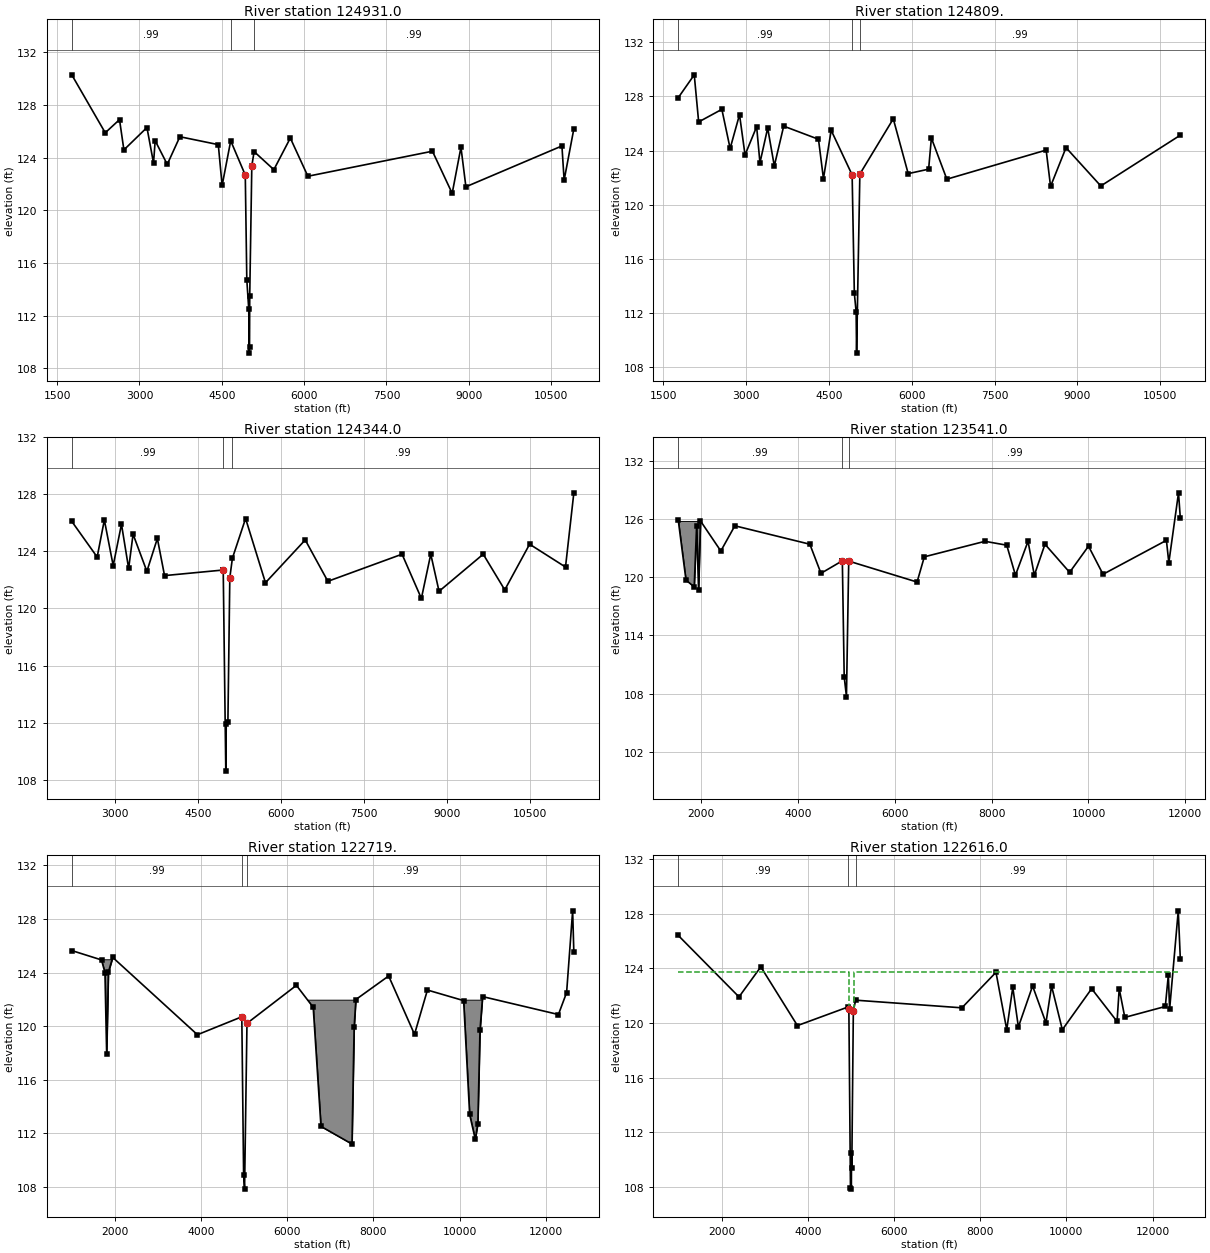
Type RM Length L Ch R = 1 ,124931.0,121.8,122,127.7
BEGIN DESCRIPTION:
Downstream Section of Bridge/Culvert/Weir
END DESCRIPTION:
XS GIS Cut Line= 5
      3043511.31      13902921.4      3043840.21      13899809.2
      3043837.75     13899613.83      3043920.12     13897807.16
      3041433.33     13894627.84
#Sta/Elev= 30
  1765.8  130.29  2375.8  125.89  2635.9  126.89  2715.8  124.59  3135.9  126.29
  3255.8  123.59  3285.8  125.29  3505.8  123.49  3735.8  125.59  4435.9  124.99
  4505.9  121.89  4662.4  125.28 4927.87  122.68 4955.67  114.73 4991.17  112.49
 5000.27  109.16 5005.17  109.63 5009.07  113.53 5046.97  123.39  5089.2  124.46
  5448.6  123.09  5748.6  125.49  6068.6  122.59  8338.6  124.49  8698.6  121.29
  8858.5  124.79  8948.5  121.79 10698.5  124.89 10738.6  122.29 10915.7  126.19
#Mann= 3 ,-1 , 0
  1765.8     .99       0  4662.4     .04       0  5089.2     .99       0
#XS Ineff= 2 , 0
       0 4937.23  119.91 5040.59       0  119.91
Permanent Ineff=
       F       F
Bank Sta=4927.87,5046.97
XS Rating Curve= 0 ,0
Exp/Cntr=0.5,0.3

Type RM Length L Ch R = 1 ,124809. ,467.3,465,435.7
BEGIN DESCRIPTION:
E100-00-00-PL56A-D/S - XS 1
END DESCRIPTION:
XS GIS Cut Line= 5
      3043632.99     13902912.91       3043961.9     13899800.71
      3043959.44     13899605.34      3044041.81     13897798.67
  3041602.02809713894679.4490767
#Sta/Elev= 30
  1769.9  127.91  2059.9   129.6  2139.9  126.12  2559.9  127.05  2709.9  124.16
  2879.9  126.66  2979.9  123.68  3189.9  125.77  3249.9   123.1  3389.9  125.67
  3509.9  122.87  3679.9  125.81  4309.9  124.84  4399.9  121.93  4539.9   125.5
  4919.4  122.21  4959.4  113.46 4991.75   112.1 5000.17  109.04  5059.4  122.27
  5664.8  126.35  5934.8   122.3  6304.8  122.63  6354.8  124.93  6634.8  121.89
  8433.4  124.04  8513.4  121.36  8793.4  124.22  9423.4  121.39 10863.4  125.14
#Mann= 3 ,-1 , 0
  1769.9     .99       0  4919.4     .04       0  5059.4     .99       0
Bank Sta=4919.4,5059.4
XS Rating Curve= 0 ,0
Exp/Cntr=0.3,0.1

Type RM Length L Ch R = 1 ,124344.0,731.9,803,804
BEGIN DESCRIPTION:
Cross Section E100-00-00-X95
END DESCRIPTION:
XS GIS Cut Line= 5
      3044424.42      13902429.8      3044461.48     13900013.01
      3044354.22     13899290.28      3043975.16     13897292.59
      3041572.59     13894206.36
#Sta/Elev= 30
  2210.6   126.1  2670.6   123.6  2800.6   126.2  2960.6     123  3110.6   125.9
  3240.6   122.8  3320.6   125.2  3570.6   122.6  3760.6   124.9  3890.6   122.3
  4947.1  122.69  4953.2  122.71  4999.8   108.6  5008.1  111.92    5038  112.05
  5072.6  122.16  5119.7  123.52  5358.3   126.3  5718.3   121.8  6438.3   124.8
  6848.3   121.9  8191.7   123.8  8541.7   120.7  8711.7   123.8  8861.7   121.2
  9661.7   123.8 10051.7   121.3 10501.7   124.5 11151.7   122.9 11302.8   128.1
#Mann= 3 ,-1 , 0
  2210.6     .99       0  4947.1     .04       0  5119.7     .99       0
Bank Sta=4953.2,5072.6
XS Rating Curve= 0 ,0
Exp/Cntr=0.3,0.1

Type RM Length L Ch R = 1 ,123541.0,988.5,822,682.9
BEGIN DESCRIPTION:
Cross Section E100-00-00-X94
END DESCRIPTION:
XS GIS Cut Line= 5
      3045010.41     13903035.32      3045091.26     13900001.96
      3045244.81     13898991.97      3044717.42     13897038.66
      3041767.92     13893913.36
#Sta/Elev= 30
    1521   125.9  1681.1   119.7  1851.1     119  1901.1   125.3  1941.1   118.7
  1981.1   125.8  2401.1   122.7  2691.1   125.3  4241.1   123.4  4471.1   120.4
  4912.4  121.69  4912.5   121.7  4951.2  109.72  4997.7  107.69  5044.7  121.66
  6457.1   119.5  6607.1   122.1  7860.4   123.7  8310.4   123.3  8490.4   120.2
  8750.4   123.7  8880.4   120.2  9100.4   123.4  9610.4   120.5 10000.4   123.2
 10300.4   120.3 11610.4   123.8 11660.4   121.5 11860.4   128.7 11897.7   126.1
#Mann= 3 ,-1 , 0
    1521     .99       0  4912.4     .04       0  5044.7     .99       0
#Block Obstruct= 2 ,-1
    1533  1981.1   125.8    1982  1982.5     100
Bank Sta=4912.5,5044.7
XS Rating Curve= 0 ,0
Exp/Cntr=0.3,0.1

Type RM Length L Ch R = 1 ,122719. ,134.4,103,102
BEGIN DESCRIPTION:
FM 1960 - U\S - XS 4
END DESCRIPTION:
XS GIS Cut Line= 6
      3046225.31     13903467.79      3046283.91     13901592.61
      3046371.78     13900005.17      3045435.46     13899396.28
      3045307.26     13897139.06      3041986.63     13893662.17
#Sta/Elev= 30
   999.9  125.64  1689.9  124.94  1769.9  123.99  1809.9  117.88  1849.9  124.03
  1949.9  125.13    3916  119.35  4945.9  120.69 4988.01  108.85 5009.79  107.81
  5065.9   120.2  6212.8  123.04  6602.8   121.4  6782.8   112.5  7502.8  111.18
  7552.8  119.89  7592.8  121.98  8353.6  123.74  8953.6  119.38  9253.6  122.69
 10093.6   121.9 10233.6  113.39 10363.6  111.54 10423.6  112.71 10473.6  119.67
 10533.6   122.2 12293.6  120.86 12483.6   122.5 12623.6  128.61 12651.5   125.5
#Mann= 3 ,-1 , 0
   999.9     .99       0  4945.9     .04       0  5065.9     .99       0
#Block Obstruct= 3 ,-1
 1375.57 1966.94  124.99 6325.07  7597.8  121.9710066.1210528.93  121.97
Bank Sta=4945.9,5065.9
XS Rating Curve= 0 ,0
Exp/Cntr=0.5,0.3

Type RM Length L Ch R = 1 ,122616.0,203.9,118,117
BEGIN DESCRIPTION:
Upstream Section of Bridge/Culvert/Weir
END DESCRIPTION:
XS GIS Cut Line= 6
      3046293.23     13903391.38      3046351.83      13901516.2
       3046439.7     13899928.77      3045503.38     13899319.87
      3045375.18     13897062.66      3042054.55     13893585.76
#Sta/Elev= 30
   993.4   126.4  2403.4   121.9  2909.5   124.1  3759.5   119.8  4941.1  121.17
  4953.2     121  4990.4  107.93  5011.3  107.83  5013.8  110.51  5020.9  109.34
    5057  120.89    5111  121.66  7576.3   121.1  8367.1   123.7  8617.1   119.5
  8757.1   122.6  8887.1   119.7  9217.1   122.7  9527.1     120  9657.1   122.7
  9907.1   119.5 10587.1   122.5 11177.1   120.1 11227.1   122.5 11357.1   120.4
 12297.1   121.2 12367.1   123.5 12397.1     121 12597.1   128.2   12645   124.7
#Mann= 3 ,-1 , 0
   993.4     .99       0  4941.1     .04       0    5111     .99       0
#XS Ineff= 2 , 0
       0  4950.4   123.7  5060.8       0   123.7
Permanent Ineff=
       F       F
Bank Sta=4953.2,5057
XS Rating Curve= 0 ,0
Exp/Cntr=0.5,0.3

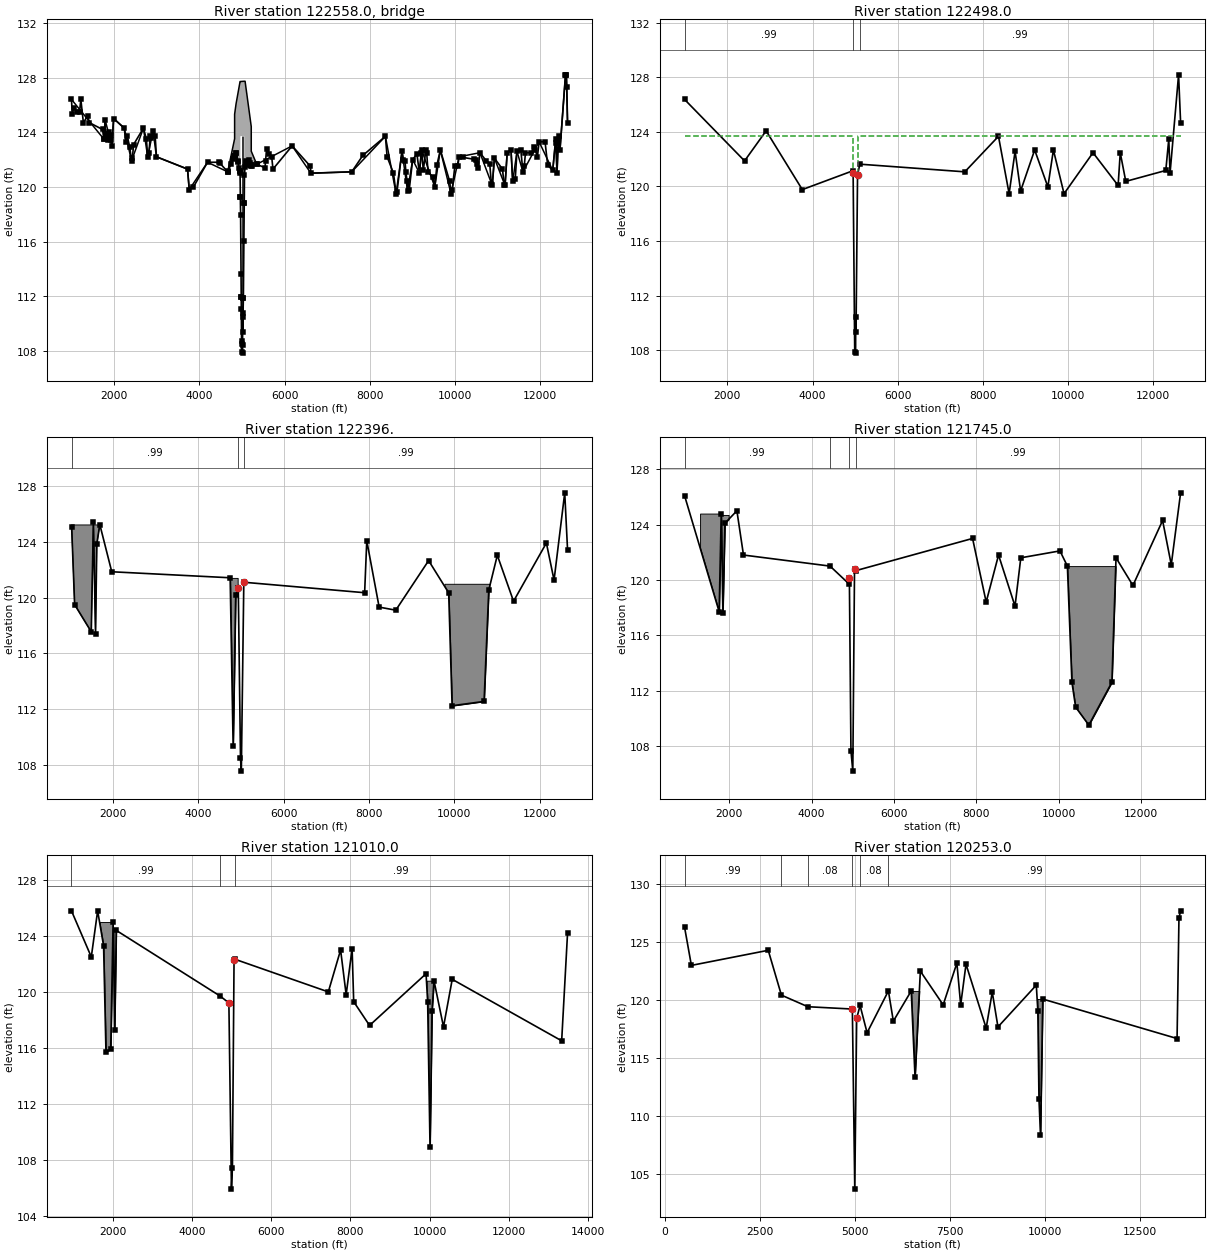
Type RM Length L Ch R = 3 ,122558.0,,,
BEGIN DESCRIPTION:
FM 1960 (JACK RABBIT ROAD)
Structure ID: E100-00-00-56
END DESCRIPTION:
Bridge Culvert--1,0,-1,-1, 0
Deck Dist Width WeirC Skew NumUp NumDn MinLoCord MaxHiCord MaxSubmerge Is_Ogee
10,96,2.6,0, 60, 60, , , 0.95, 0, ,,,
   993.4  1753.4  1783.4  1943.4  1983.4  2233.4  2403.4  2683.4  2783.4  2909.5
  2989.5  3719.5  3759.5  4189.5  4662.1 4825.29  4825.4  4859.3  4953.2 4960.31
  4960.4 5050.69  5050.8    5057  5071.2  5216.1 5216.21  5344.6  6176.3  6616.3
  7576.3  8367.1  8617.1  8757.1  8887.1  9007.1  9167.1  9217.1  9527.1  9657.1
  9907.1 10097.1 10587.1 10877.1 10927.1 11177.1 11227.1 11317.1 11357.1 11457.1
 11597.1 11977.1 12297.1 12367.1 12397.1 12427.1 12467.1 12597.1 12617.1   12645
   126.4   123.5   124.9     123     125   124.3   121.9   124.3   122.2   124.1
   122.2   121.3   119.8   121.8   121.1  123.52  125.32  126.08  127.71  127.71
  127.71  127.73  127.73  127.73  127.73  124.41  122.61  121.65     123     121
   121.1   123.7   119.5   122.6   119.7     122     121   122.7     120   122.7
   119.5   122.2   122.5   120.1   122.1   120.1   122.5   122.7   120.4   122.6
   121.1   123.3   121.2   123.5     121   123.4   122.7   128.2   128.2   124.7
   126.4   123.5   124.9     123     125   124.3   121.9   124.3   122.2   124.1
   122.2   121.3   119.8   121.8   121.1  122.25  122.25  122.49     121  119.27
  123.71  123.73  118.82  120.89  121.47  121.57  121.57  121.65     123     121
   121.1   123.7   119.5   122.6   119.7     122     121   122.7     120   122.7
   119.5   122.2   122.5   120.1   122.1   120.1   122.5   122.7   120.4   122.6
   121.1   123.3   121.2   123.5     121   123.4   122.7   128.2   128.2   124.7
   993.4  1753.4  1783.4  1943.4  1983.4  2233.4  2403.4  2683.4  2783.4  2909.5
  2989.5  3719.5  3759.5  4189.5  4662.1 4825.29  4825.4  4859.3  4953.2 4960.31
  4960.4 5050.69  5050.8    5057  5071.2  5216.1 5216.21  5344.6  6176.3  6616.3
  7576.3  8367.1  8617.1  8757.1  8887.1  9007.1  9167.1  9217.1  9527.1  9657.1
  9907.1 10097.1 10587.1 10877.1 10927.1 11177.1 11227.1 11317.1 11357.1 11457.1
 11597.1 11977.1 12297.1 12367.1 12397.1 12427.1 12467.1 12597.1 12617.1   12645
   126.4   123.5   124.9     123     125   124.3   121.9   124.3   122.2   124.1
   122.2   121.3   119.8   121.8   121.1  123.52  125.32  126.08  127.71  127.71
  127.71  127.73  127.73  127.73  127.73  124.41  122.61  121.65     123     121
   121.1   123.7   119.5   122.6   119.7     122     121   122.7     120   122.7
   119.5   122.2   122.5   120.1   122.1   120.1   122.5   122.7   120.4   122.6
   121.1   123.3   121.2   123.5     121   123.4   122.7   128.2   128.2   124.7
  126.39  123.49  124.89  122.99  124.99  124.29  121.89  124.29  122.19  124.09
  122.19  121.29  119.79  121.79  121.09  122.24  122.24  122.48  120.99  119.26
   123.7  123.72  118.81  120.88  121.46  121.56  121.56  121.64  122.99  120.99
  121.09  123.69  119.49  122.59  119.69  121.99  120.99  122.69  119.99  122.69
  119.49  122.19  122.49  120.09  122.09  120.09  122.49  122.69  120.39  122.59
  121.09  123.29  121.19  123.49  120.99  123.39  122.69  128.19  128.19  124.69
Pier Skew, UpSta & Num, DnSta & Num=  ,4990.6, 2 ,4990.6, 2 , 0 , 0 , 0 ,,
     1.3     1.3
  107.05  124.72
     1.3     1.3
  107.04  124.71
Pier Skew, UpSta & Num, DnSta & Num=  ,5020.9, 2 ,5020.9, 2 , 0 , 0 , 0 ,,
     1.3     1.3
  108.45  124.72
     1.3     1.3
  108.44  124.71
Abutment Skew #Up #Dn= , 2 , 2
  4960.2  4983.1
  123.71  111.93
  4960.2  4983.1
   123.7  111.92
Abutment Skew #Up #Dn= , 2 , 2
    5031 5050.89
  111.87  123.73
    5031 5050.89
  111.86  123.72
BR Coef= 1 , 1 , 0 ,1.25, 0 ,,,0.8,0,2,0,
WSPro=,,,, 1 ,,,, 0 ,,,, 0 ,,,,-1 ,-1 ,-1 , 0 , 0 , 0 , 0 , 0
BR U #Sta/Elev= 180
   993.4   126.4  1013.4   125.3  1043.4   125.8  1123.4   125.5  1183.4   125.5
  1213.4   126.4  1273.4   124.7  1373.4   125.2  1413.4   124.7  1723.4   124.2
  1753.4   123.5  1763.4   123.5  1783.4   124.9  1793.4   123.9  1798.6  123.86
  1853.4   123.4  1863.4     124  1913.4   123.8  1928.4   123.4  1943.4     123
  1983.4     125  2233.4   124.3  2273.4   123.3  2303.4   123.7  2363.4   122.9
  2403.4   121.9  2423.4   122.1  2453.4   123.1  2683.4   124.3  2753.4   123.5
  2783.4   122.2  2813.4   122.5  2843.4   123.7  2869.5   123.6  2909.5   124.1
  2959.5   123.7  2989.5   122.2  3719.5   121.3  3759.5   119.8  3859.5     120
  4189.5   121.8  4459.4   121.8  4471.9  121.76    4662   121.1  4662.1   121.1
  4671.3  121.17  4746.3  121.69  4796.3  122.05  4822.5  122.23 4825.29  122.25
  4825.4  122.25 4825.51  122.25  4855.3  122.46  4859.3  122.49    4894  121.91
  4899.9  121.81  4927.4  121.37  4940.2  121.19  4941.1  121.17  4953.2     121
 4960.31  119.27  4960.4  119.25  4965.8  117.94    4977   113.6    4983  111.96
  4983.1  111.93  4985.7  111.07  4988.2  108.52  4990.4  107.93  4990.6  108.73
  5011.3  107.83  5011.8  108.46  5013.8  110.51  5020.9  109.34  5022.8  110.78
  5030.9  111.83    5031  111.87  5042.5  116.06 5050.69  118.79  5050.8  118.82
    5057  120.89  5071.2  121.47  5081.8  121.91  5098.8  121.76    5111  121.66
  5115.1  121.62    5137  121.77  5163.7  121.95  5194.1  121.73 5215.99  121.57
  5216.1  121.57 5216.21  121.57  5217.4  121.56  5223.6  121.52  5344.6  121.65
  5344.7  121.65  5539.4   121.4  5553.1  121.92  5576.3   122.8  5636.3   122.4
  5696.3   122.2  5726.3   121.3  6176.3     123  6606.3   121.5  6616.3     121
  7576.3   121.1  7837.1   122.3  8367.1   123.7  8407.1   122.2  8557.1     121
  8617.1   119.5  8637.1   119.6  8757.1   122.6  8787.1     122  8827.1   121.9
  8847.1   121.1  8877.1   120.4  8887.1   119.7  8927.1   119.8  9007.1     122
  9107.1   122.4  9167.1     121  9207.1   122.5  9217.1   122.7  9257.1   121.2
  9317.1   122.7  9337.1   122.5  9367.1   121.1  9487.1   120.7  9527.1     120
  9577.1   121.6  9657.1   122.7  9877.1   120.4  9907.1   119.5  9937.1   119.8
  9997.1   121.5 10067.1   121.5 10097.1   122.2 10199.2  122.15 10443.4  122.02
 10487.1     122 10507.1   121.7 10547.1   121.4 10587.1   122.5 10737.1   121.9
 10817.1   121.7 10857.1   120.2 10877.1   120.1 10927.1   122.1 11117.1   121.3
 11157.1   120.1 11177.1   120.1 11227.1   122.5 11317.1   122.7 11357.1   120.4
 11417.1   120.6 11457.1   122.6 11547.1   122.7 11597.1   121.1 11627.1   121.5
 11657.1   122.5 11787.1   122.5 11867.1   122.9 11888.7  122.68 11937.1   122.2
 11977.1   123.3 12117.1   123.3 12177.1   121.6 12297.1   121.2 12367.1   123.5
 12377.1   123.2 12397.1     121 12427.1   123.4 12447.1   123.7 12467.1   122.7
 12596.9  128.19 12597.1   128.2 12617.1   128.2 12627.1   127.3   12645   124.7
BR U #Mann= 3
   993.4     .99  4941.1     .04    5111     .99
BR U Banks=4953.2,5057
BR D #Sta/Elev= 180
   993.4  126.39  1013.4  125.29  1043.4  125.79  1123.4  125.49  1183.4  125.49
  1213.4  126.39  1273.4  124.69  1373.4  125.19  1413.4  124.69  1723.4  124.19
  1753.4  123.49  1763.4  123.49  1783.4  124.89  1793.4  123.89  1798.6  123.85
  1853.4  123.39  1863.4  123.99  1913.4  123.79  1928.4  123.39  1943.4  122.99
  1983.4  124.99  2233.4  124.29  2273.4  123.29  2303.4  123.69  2363.4  122.89
  2403.4  121.89  2423.4  122.09  2453.4  123.09  2683.4  124.29  2753.4  123.49
  2783.4  122.19  2813.4  122.49  2843.4  123.69  2869.5  123.59  2909.5  124.09
  2959.5  123.69  2989.5  122.19  3719.5  121.29  3759.5  119.79  3859.5  119.99
  4189.5  121.79  4459.4  121.79  4471.9  121.75    4662  121.09  4662.1  121.09
  4671.3  121.16  4746.3  121.68  4796.3  122.04  4822.5  122.22 4825.29  122.24
  4825.4  122.24 4825.51  122.24  4855.3  122.45  4859.3  122.48    4894   121.9
  4899.9   121.8  4927.4  121.36  4940.2  121.18  4941.1  121.16  4953.2  120.99
 4960.31  119.26  4960.4  119.24  4965.8  117.93    4977  113.59    4983  111.95
  4983.1  111.92  4985.7  111.06  4988.2  108.51  4990.4  107.92  4990.6  108.72
  5011.3  107.82  5011.8  108.45  5013.8   110.5  5020.9  109.33  5022.8  110.77
  5030.9  111.82    5031  111.86  5042.5  116.05 5050.69  118.78  5050.8  118.81
    5057  120.88  5071.2  121.46  5081.8   121.9  5098.8  121.75    5111  121.65
  5115.1  121.61    5137  121.76  5163.7  121.94  5194.1  121.72 5215.99  121.56
  5216.1  121.56 5216.21  121.56  5217.4  121.55  5223.6  121.51  5344.6  121.64
  5344.7  121.64  5539.4  121.39  5553.1  121.91  5576.3  122.79  5636.3  122.39
  5696.3  122.19  5726.3  121.29  6176.3  122.99  6606.3  121.49  6616.3  120.99
  7576.3  121.09  7837.1  122.29  8367.1  123.69  8407.1  122.19  8557.1  120.99
  8617.1  119.49  8637.1  119.59  8757.1  122.59  8787.1  121.99  8827.1  121.89
  8847.1  121.09  8877.1  120.39  8887.1  119.69  8927.1  119.79  9007.1  121.99
  9107.1  122.39  9167.1  120.99  9207.1  122.49  9217.1  122.69  9257.1  121.19
  9317.1  122.69  9337.1  122.49  9367.1  121.09  9487.1  120.69  9527.1  119.99
  9577.1  121.59  9657.1  122.69  9877.1  120.39  9907.1  119.49  9937.1  119.79
  9997.1  121.49 10067.1  121.49 10097.1  122.19 10199.2  122.14 10443.4  122.01
 10487.1  121.99 10507.1  121.69 10547.1  121.39 10587.1  122.49 10737.1  121.89
 10817.1  121.69 10857.1  120.19 10877.1  120.09 10927.1  122.09 11117.1  121.29
 11157.1  120.09 11177.1  120.09 11227.1  122.49 11317.1  122.69 11357.1  120.39
 11417.1  120.59 11457.1  122.59 11547.1  122.69 11597.1  121.09 11627.1  121.49
 11657.1  122.49 11787.1  122.49 11867.1  122.89 11888.7  122.67 11937.1  122.19
 11977.1  123.29 12117.1  123.29 12177.1  121.59 12297.1  121.19 12367.1  123.49
 12377.1  123.19 12397.1  120.99 12427.1  123.39 12447.1  123.69 12467.1  122.69
 12596.9  128.18 12597.1  128.19 12617.1  128.19 12627.1  127.29   12645  124.69
BR D #Mann= 3
   993.4     .99  4941.1     .04    5111     .99
BR D Banks=4953.2,5057
BC Design=,, 0 ,, 0 ,,,,,,
BC HTab HWMax=128.2
BC Use User HTab Curves=0
BC User HTab FreeFlow(D)= 0

Type RM Length L Ch R = 1 ,122498.0,121.2,102,101
BEGIN DESCRIPTION:
Downstream Section of Bridge/Culvert/Weir
END DESCRIPTION:
XS GIS Cut Line= 6
      3046357.78     13903289.05      3046416.38     13901413.81
      3046504.09      13899829.2      3045568.07      13899220.5
      3045439.83      13896962.6      3042120.48     13893487.04
#Sta/Elev= 30
   993.4  126.37  2403.4  121.87  2909.5  124.07  3759.5  119.77  4941.1  121.14
  4953.2  120.97  4990.4   107.9  5011.3   107.8  5013.8  110.48  5020.9  109.31
    5057  120.86    5111  121.63  7576.3  121.07  8367.1  123.67  8617.1  119.47
  8757.1  122.57  8887.1  119.67  9217.1  122.67  9527.1  119.97  9657.1  122.67
  9907.1  119.47 10587.1  122.47 11177.1  120.07 11227.1  122.47 11357.1  120.37
 12297.1  121.17 12367.1  123.47 12397.1  120.97 12597.1  128.17   12645  124.67
#Mann= 3 ,-1 , 0
   993.4     .99       0  4941.1     .04       0    5111     .99       0
#XS Ineff= 2 , 0
       0  4950.4   123.7  5060.8       0   123.7
Permanent Ineff=
       F       F
Bank Sta=4953.2,5057
XS Rating Curve= 0 ,0
Exp/Cntr=0.5,0.3

Type RM Length L Ch R = 1 ,122396. ,26.6,651,768
BEGIN DESCRIPTION:
FM 1960 - D\S - XS 1
END DESCRIPTION:
XS GIS Cut Line= 6
      3046428.53     13903215.47      3046533.26     13899727.66
      3046460.69     13899681.39      3045638.82     13899146.92
      3045510.58     13896889.02      3042191.22     13893413.46
#Sta/Elev= 30
  1032.6  125.08  1102.6   119.5  1492.6  117.55  1542.6  125.42  1592.6  117.43
  1622.6  123.83  1692.6  125.23  1972.6  121.85    4748  121.42    4818  109.37
    4878  120.18    4938  120.69 4990.34   108.5 5009.74  107.58    5068   121.1
    7900  120.35    7950  124.07    8240  119.32    8630   119.1    9400  122.65
    9870  120.34    9950  112.26   10700  112.57   10810  120.54   11010  123.03
   11390  119.74   12160  123.91   12340  121.25   12590   127.5   12656  123.43
#Mann= 3 ,-1 , 0
  1032.6     .99       0    4938     .04       0    5068     .99       0
#Block Obstruct= 3 ,-1
 1028.47 1696.97   125.2  4743.8 4923.78  121.41 9770.4310824.61  120.99
Bank Sta=4938,5068
XS Rating Curve= 0 ,0
Exp/Cntr=0.3,0.1

Type RM Length L Ch R = 1 ,121745.0,854.9,735,648.4
BEGIN DESCRIPTION:
Cross Section E100-00-00-X93
END DESCRIPTION:
XS GIS Cut Line= 5
      3046553.53     13903601.78      3046549.24     13899789.85
      3046866.06      13899363.1       3046006.6     13896862.86
      3042275.78      13893464.1
#Sta/Elev= 30
   917.9   126.1  1757.9   117.7  1807.9   124.8  1847.9   117.6  1897.9   124.1
  2187.9     125  2347.9   121.8  4447.9     121    4908  119.71  4916.4  120.11
  4954.8  107.63  4999.8  106.17  5041.7   120.8  5070.9  120.67  7905.2     123
  8235.2   118.4  8535.2   121.8  8935.2   118.1  9075.2   121.6 10025.2   122.1
 10205.2     121 10315.2   112.6 10405.2   110.8 10725.2   109.5 11285.2   112.6
 11385.2   121.6 11795.2   119.6 12515.2   124.3 12725.2   121.1   12952   126.3
#Mann= 4 ,-1 , 0
   917.9     .99       0  4447.9     .08       0    4908     .04       0
  5070.9     .99       0
#Block Obstruct= 3 ,-1
    1295  1807.9   124.8    1808  1987.9   124.7 10205.2   11376     121
Bank Sta=4916.4,5041.7
XS Rating Curve= 0 ,0
Exp/Cntr=0.3,0.1

Type RM Length L Ch R = 1 ,121010.0,891.8,757,705.2
BEGIN DESCRIPTION:
Cross Section E100-00-00-X92
END DESCRIPTION:
XS GIS Cut Line= 5
      3047178.59     13903777.58      3047371.29     13900028.49
      3047390.63     13898425.47       3046358.2     13895925.27
      3043936.09     13892194.45
#Sta/Elev= 30
   964.7   125.8  1464.7   122.5  1624.7   125.8  1774.7   123.3  1834.7   115.7
  1954.7   115.9  2014.7     125  2054.7   117.3  2094.7   124.4  4714.7   119.7
  4934.5  119.21  4998.9  105.89  5023.5  107.41  5064.7  122.29  5082.9  122.34
  7441.9     120  7751.9     123  7891.9   119.8  8041.9   123.1  8081.9   119.3
  8481.9   117.6  9906.9   121.3  9946.9   119.3 10006.9   108.9 10056.9   118.6
 10106.9   120.8 10346.9   117.5 10566.9   120.9 13326.9   116.5   13475   124.2
#Mann= 3 ,-1 , 0
   964.7     .99       0  4714.7     .04       0  5082.9     .99       0
#Block Obstruct= 3 ,-1
    1680  2014.7     125    2024  2094.7   124.4    9925 10106.9   120.8
Bank Sta=4934.5,5064.7
XS Rating Curve= 0 ,0
Exp/Cntr=0.3,0.1

Type RM Length L Ch R = 1 ,120253.0,873.1,863,862
BEGIN DESCRIPTION:
Cross Section E100-00-00-X91
END DESCRIPTION:
XS GIS Cut Line= 5
      3048858.44     13903972.91      3048257.76     13899887.09
      3047947.77     13899294.29      3046631.66     13895710.41
      3044053.29     13892116.31
#Sta/Elev= 30
   523.7   126.3   703.7     123  2723.7   124.3  3069.7  120.44  3765.5  119.44
    4935  119.24  4998.5  103.73  5048.3  118.43  5137.4  119.55  5322.4   117.2
  5882.4   120.8  6012.4   118.2  6482.4   120.8  6582.4   113.4  6722.4   122.5
  7322.4   119.6  7682.4   123.2  7782.4   119.6  7922.4   123.1  8452.4   117.6
  8612.4   120.7  8762.4   117.7  9770.3   121.3  9810.3   119.1  9840.3   111.5
  9880.3   108.4  9940.3   120.1 13470.3   116.7 13520.3   127.1 13563.6   127.7
#Mann= 6 ,-1 , 0
   523.7     .99       0  3069.7     .05       0  3765.5     .08       0
    4935     .04       0  5137.4     .08       0  5882.4     .99       0
#Block Obstruct= 2 ,-1
  6482.4  6695.6   120.8    9800  9940.3   120.1
Bank Sta=4935,5048.3
XS Rating Curve= 0 ,0
Exp/Cntr=0.3,0.1