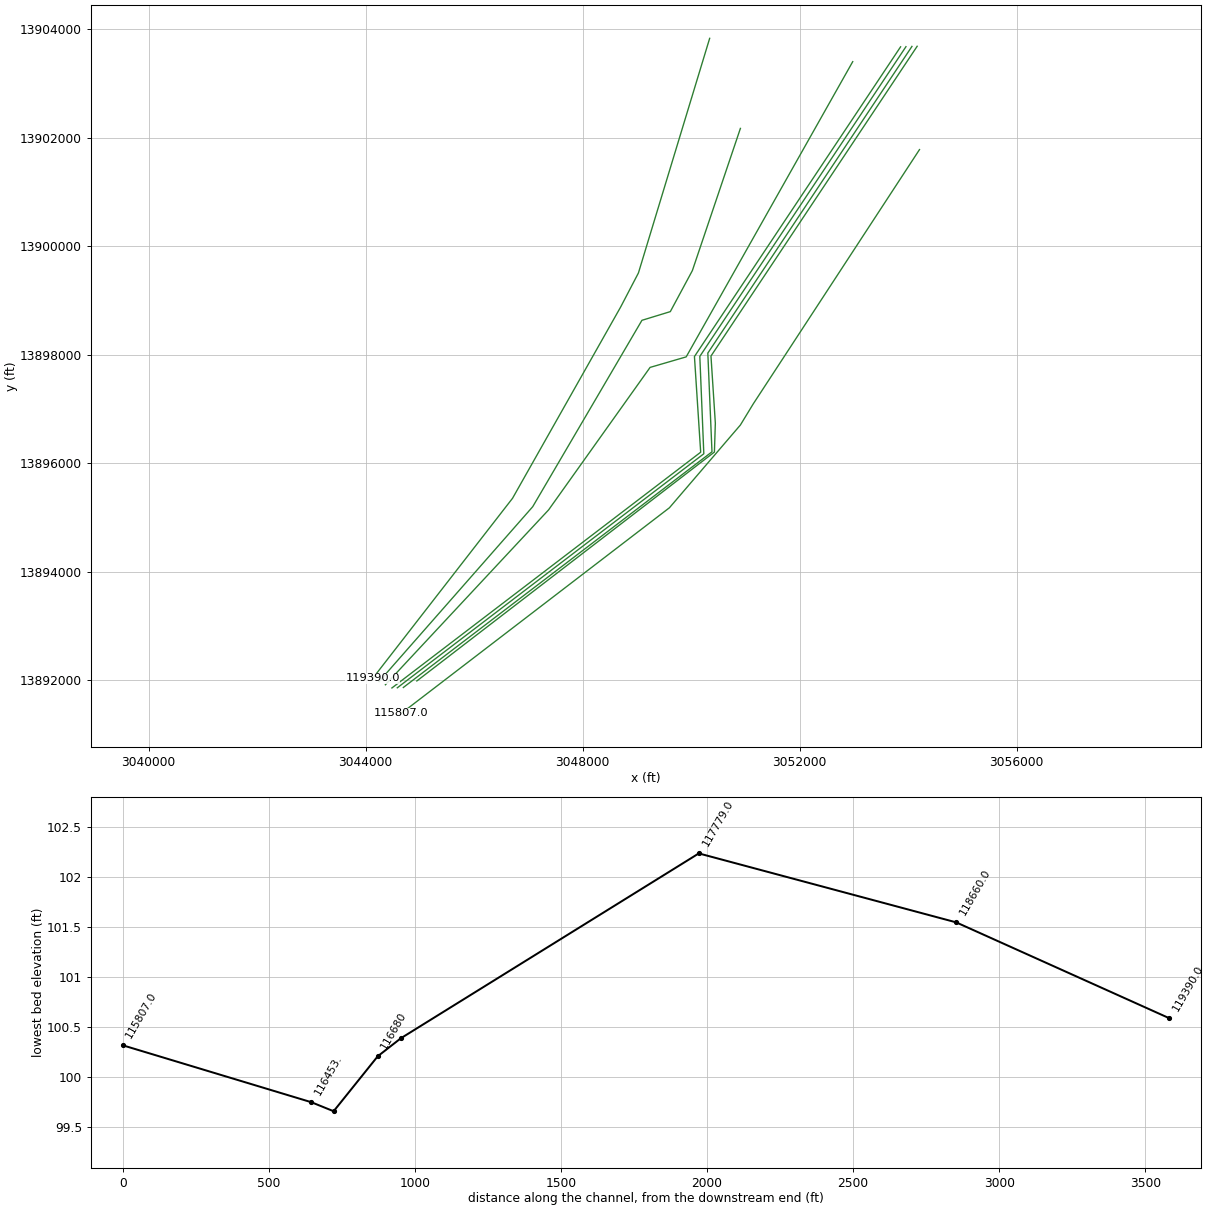
HEC-RAS study E100-00-00.prj: E100-00-00

--- E100-00-00.g02 (geometry) --- (continued)

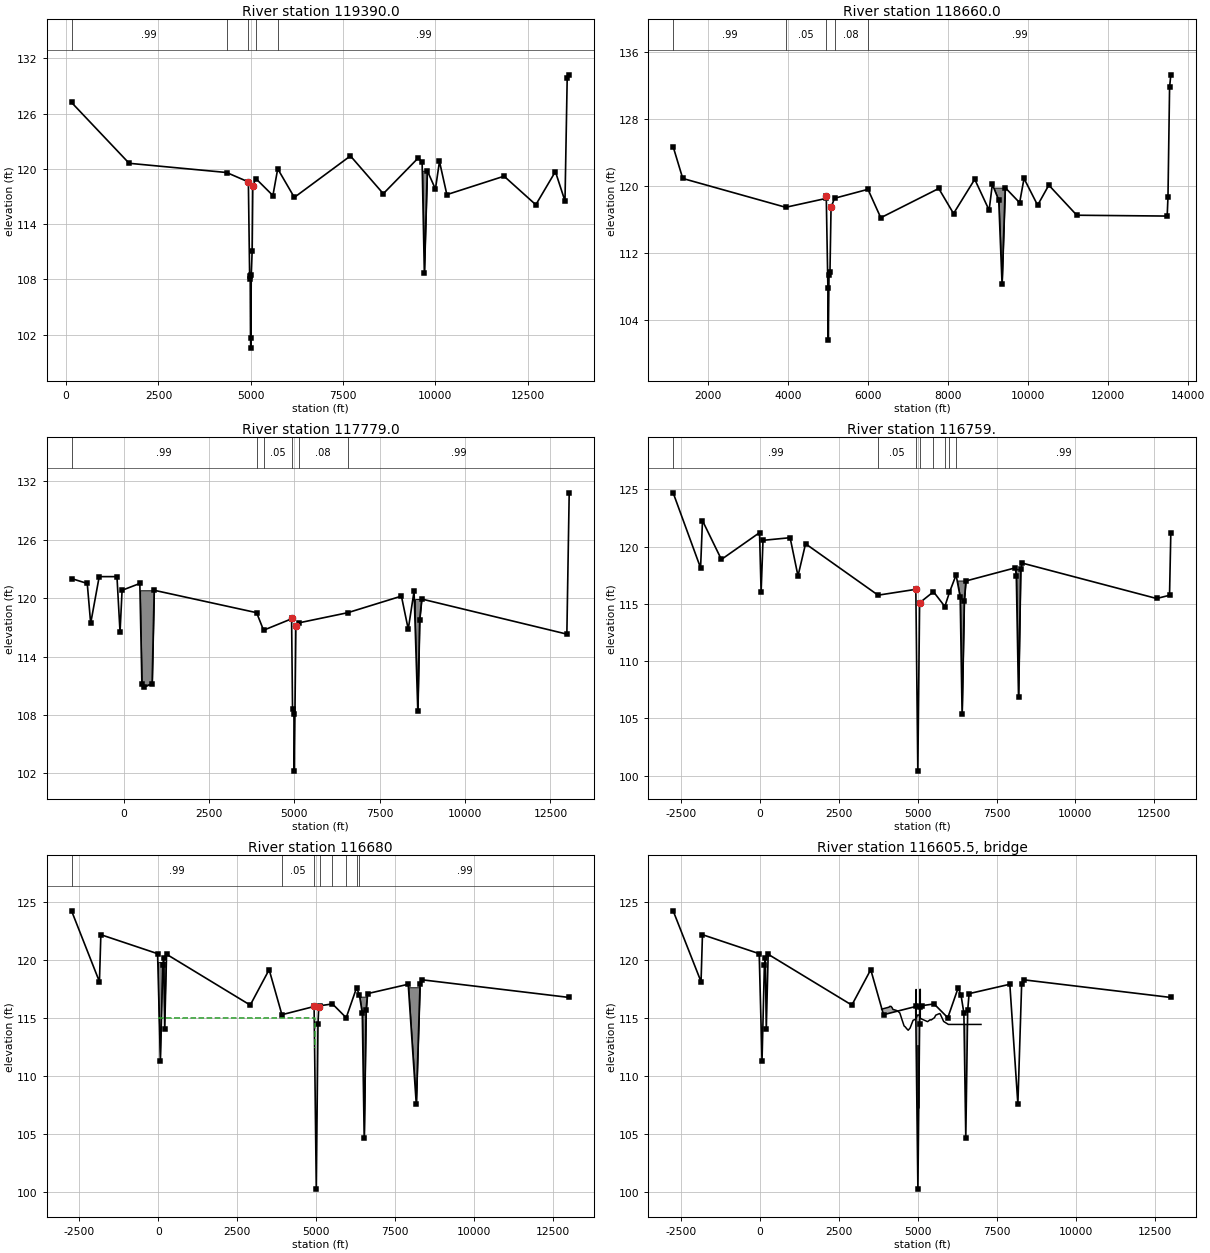
Type RM Length L Ch R = 1 ,119390.0,910.1,730,491.7
BEGIN DESCRIPTION:
Cross Section E100-00-00-X90
END DESCRIPTION:
XS GIS Cut Line= 5
      3050342.95     13903836.18      3049030.02     13899511.83
      3048703.72     13898886.41      3046709.79     13895358.81
      3044131.42     13892038.18
#Sta/Elev= 30
     146   127.2    1706   120.6    4346   119.6  4935.9  118.58  4970.5  108.32
  4985.9  108.01  4993.7  101.69  5001.6  100.59  5014.3  108.48    5039   111.1
  5055.9  118.15  5137.9  118.94  5600.7   117.1  5730.7     120  6180.7   116.9
  7700.7   121.4  8590.7   117.3  9542.8   121.2  9642.8   120.7  9702.8   108.7
  9782.8   119.8 10002.8   117.8 10112.8   120.8 10312.8   117.2 11862.8   119.2
 12722.8   116.1 13252.8   119.7 13512.8   116.5 13572.8   129.9 13626.9   130.2
#Mann= 5 ,-1 , 0
     146     .99       0    4346     .08       0  4935.9     .04       0
  5137.9     .08       0  5730.7     .99       0
#Block Obstruct= 2 ,-1
  9646.4  9782.8   119.8    9784  9784.2     100
Bank Sta=4935.9,5055.9
XS Rating Curve= 0 ,0
Exp/Cntr=0.3,0.1

Type RM Length L Ch R = 1 ,118660.0,969.3,881,839.7
BEGIN DESCRIPTION:
Cross Section E100-00-00-X89
END DESCRIPTION:
XS GIS Cut Line= 6
      3050909.41     13902175.87       3050023.9     13899554.66
      3049617.54     13898798.85      3049094.54     13898638.67
      3047080.92     13895202.55      3044248.62     13891979.58
#Sta/Elev= 30
  1119.5   124.7  1359.5   120.9  3933.8  117.45  4942.5  118.51  4948.1  118.83
  4989.2  107.76  4999.2  101.55  5016.9  109.32  5041.1  109.67  5068.1  117.45
  5155.2  118.53  5991.3   119.6  6311.3   116.2  7761.3   119.7  8131.3   116.7
  8661.3   120.8  9021.3   117.1  9101.3   120.2  9261.3   118.3    9344   108.3
    9424   119.8    9784     118    9894   120.9   10234   117.7   10514   120.1
   11214   116.5   13474   116.4   13494   118.7   13534   131.8 13564.6   133.3
#Mann= 5 ,-1 , 0
  1119.5     .99       0  3933.8     .05       0  4942.5     .04       0
  5155.2     .08       0  5991.3     .99       0
#Block Obstruct= 2 ,-1
  9143.8    9424   119.8  9424.1  9424.2     100
Bank Sta=4948.1,5068.1
XS Rating Curve= 0 ,0
Exp/Cntr=0.3,0.1

Type RM Length L Ch R = 1 ,117779.0,871.8,1020,1375.8
BEGIN DESCRIPTION:
Cross Section E100-00-00-X88
END DESCRIPTION:
XS GIS Cut Line= 5
      3052979.92     13903406.45       3049910.1     13897964.64
      3049244.93     13897770.73      3047373.92     13895143.95
      3044365.82     13891920.98
#Sta/Elev= 30
 -1523.7     122 -1063.7   121.5  -963.7   117.4  -713.7   122.2  -193.7   122.2
  -103.7   116.5   -43.7   120.8   476.3   121.5   536.3   111.2   586.3   110.9
   836.3   111.2   896.3   120.8  3896.3   118.5  4099.7   116.7  4919.6  117.87
  4920.5  117.91  4948.2  108.66  4988.5  108.14  5000.3  102.24  5046.5  117.15
  5125.4  117.45  6567.1   118.5  8137.1   120.2  8337.1   116.8  8507.1   120.7
  8617.1   108.4  8672.1   117.8  8732.1   119.9 12982.1   116.3 13050.8   130.8
#Mann= 6 ,-1 , 0
 -1523.7     .99       0  3896.3     .08       0  4099.7     .05       0
  4919.6     .04       0  5125.4     .08       0  6567.1     .99       0
#Block Obstruct= 2 ,-1
   484.4   896.3   120.8    8536    8732   119.9
Bank Sta=4920.5,5046.5
XS Rating Curve= 0 ,0
Exp/Cntr=0.3,0.1

Type RM Length L Ch R = 1 ,116759. ,78.2,79,83.3
BEGIN DESCRIPTION:
Jones - U\S - XS 4
END DESCRIPTION:
XS GIS Cut Line= 4
      3053862.09     13903679.66       3050062.4     13897970.99
      3050177.29     13896207.49       3044486.2     13891862.13
#Sta/Elev= 30
 -2759.7   124.7 -1889.7  118.14 -1829.7  122.27 -1229.7  118.88   -19.7  121.22
    30.3  116.02    90.3  120.55   950.3  120.78  1200.3  117.44  1440.3  120.25
  3740.3  115.76  4937.9  116.27 5001.12  100.39  5057.9  115.09  5497.9  116.06
  5857.9  114.77  6005.1  116.01  6215.1  117.53  6345.1  115.59  6405.1  105.41
  6475.1  115.29  6525.1     117  8095.1  118.15  8125.1  117.44  8195.1  106.84
  8265.1  118.04  8315.1  118.56 12575.1  115.47 12985.1  115.75 13025.5  121.15
#Mann= 8 ,-1 , 0
 -2759.7     .99       0  3740.3     .05       0  4937.9     .04       0
  5057.9      .1       0  5497.9     .05       0  5857.9     .08       0
  6005.1      .1       0  6215.1     .99       0
#Block Obstruct= 2 ,-1
 6211.54 6519.23  117.04 8076.92 8269.23  118.06
Bank Sta=4937.9,5057.9
XS Rating Curve= 0 ,0
Exp/Cntr=0.5,0.3

Type RM Length L Ch R = 1 ,116680  ,150.5,151,156.7
XS GIS Cut Line= 4
 3053961.139999413903682.48999983050161.4500008113897973.8199997
3050235.1387939313896178.86897383044585.2399997913891864.9599991
#Sta/Elev= 30
-2750.88  124.24-1867.48  118.12-1822.56  122.18  -25.81  120.54   64.03  111.28
  138.89  119.52  168.84  120.19  198.78     114  258.67  120.49  2908.9   116.1
 3507.83  119.16  3912.1  115.27 4931.87  115.98  5001.2  100.21    5055   114.5
 5079.85  115.94 5124.76  116.05    5514   116.2 5948.23  115.01 6278.16   117.6
 6368.15  116.95 6458.13   115.4 6518.12  104.65 6578.11  115.65  6623.1  117.09
 7912.85   117.9  8167.8  107.56 8287.77  117.95 8362.76  118.2813011.85  116.76
#Mann= 8 ,-1 , 0
-2750.88     .99       0  3912.1     .05       0 4931.87     .04       0
 5124.76      .1       0    5514     .05       0 5948.23     .08       0
 6278.16      .1       0 6368.15     .99       0
#XS Ineff= 2 , 0
       0 4947.55     115 5067.55       0  115.08
Permanent Ineff=
       F       F
#Block Obstruct= 3 ,-1
       4  258.67  119.77    6353    6623  116.83    7897  8287.8  117.64
Bank Sta=4931.87,5079.85
XS Rating Curve= 0 ,0
Exp/Cntr=0.5,0.3

Type RM Length L Ch R = 3 ,116605.5,,,
BEGIN DESCRIPTION:
JONES
Structure ID: E100-00-00-55
-Bridge updated by PBS&J (July 2010) using survey provided by Benchmark Engineering (survey date 03-08-07).  Deck does not include dual 0.3' rails.  Both rails are above the 100-year flood stage.
END DESCRIPTION:
Bridge Culvert--1,0,-1,-1, 0
Deck Dist Width WeirC Skew NumUp NumDn MinLoCord MaxHiCord MaxSubmerge Is_Ogee
32,87,2.6,0, 40, 40, , , 0.95, 0, ,,,
 3852.15 4083.95 4108.95 4133.94 4148.93 4183.92 4208.92 4308.89 4353.88 4428.86
 4503.84 4563.82 4603.81  4643.8 4693.78 4753.77 4848.74 4927.55 4938.23 4938.24
 4947.54 4947.55 4987.55 5027.55 5067.55 5067.56 5076.86 5076.87 5087.55 5093.55
 5307.55 5389.55 5418.55 5525.55 5565.55 5685.55 5706.55 5816.55 5966.81    7000
  115.75  115.92  115.99  115.99  115.99  115.88  115.73  115.65   115.6  115.42
  114.79   114.3  114.21  114.07  113.93  114.12  114.79  114.88  114.94  117.44
  117.44     115  115.24  115.25  115.08  117.46  117.46  115.01  114.93  114.93
  114.67  114.84  114.81  115.01  115.23  115.37  115.34  114.69  114.43  114.43
     100     100     100     100     100     100     100     100     100     100
     100     100     100     100     100     100     100     100     100     100
     100  112.47  112.63  112.57  112.49     100     100     100     100     100
     100     100     100     100     100     100     100     100     100     100
 3853.66 4085.46 4110.46 4135.45 4150.44 4185.43 4210.43  4310.4 4355.39 4430.37
 4505.35 4565.33 4605.32 4645.31 4695.29 4755.28 4850.25 4929.06 4939.74 4939.75
 4949.05 4949.06 4989.06 5029.06 5069.06 5069.07 5078.37 5078.38 5089.06 5095.06
 5309.06 5391.06 5420.06 5527.06 5567.06 5687.06 5708.06 5818.06 5968.32 7001.51
  115.75  115.92  115.99  115.99  115.99  115.88  115.73  115.65   115.6  115.42
  114.79   114.3  114.21  114.07  113.93  114.12  114.79  114.88  114.94  117.44
  117.44     115  115.24  115.25  115.08  117.46  117.46  115.01  114.93  114.93
  114.67  114.84  114.81  115.01  115.23  115.37  115.34  114.69  114.43  114.43
     100     100     100     100     100     100     100     100     100     100
     100     100     100     100     100     100     100     100     100     100
     100  112.47  112.63  112.57  112.49     100     100     100     100     100
     100     100     100     100     100     100     100     100     100     100
Pier Skew, UpSta & Num, DnSta & Num=  ,4987.55, 4 ,4983.3, 4 , 3 , 3 , 0 ,,
    1.15    1.15    2.55    2.55
      90  110.07  110.08  112.63
    1.15    1.15    2.55    2.55
      90  110.07  110.08  112.63
Pier Skew, UpSta & Num, DnSta & Num=  ,5027.55, 4 ,5023.2, 4 , 3 , 3 , 0 ,,
    1.15    1.15    2.55    2.55
      90  110.01  110.02  112.57
    1.15    1.15    2.55    2.55
      90  110.01  110.02  112.57
BR Coef= 1 , 1 , 0 ,1.25, 0 ,,,0.8,0,2,0,
WSPro=,,,, 1 ,,,, 0 ,,,, 0 ,,,,-1 ,-1 ,-1 , 0 , 0 , 0 , 0 , 0
BC Design=,, 0 ,, 0 ,,,,,,
BC HTab HWMax=124.72
BC Use User HTab Curves=0
BC User HTab FreeFlow(D)= 0

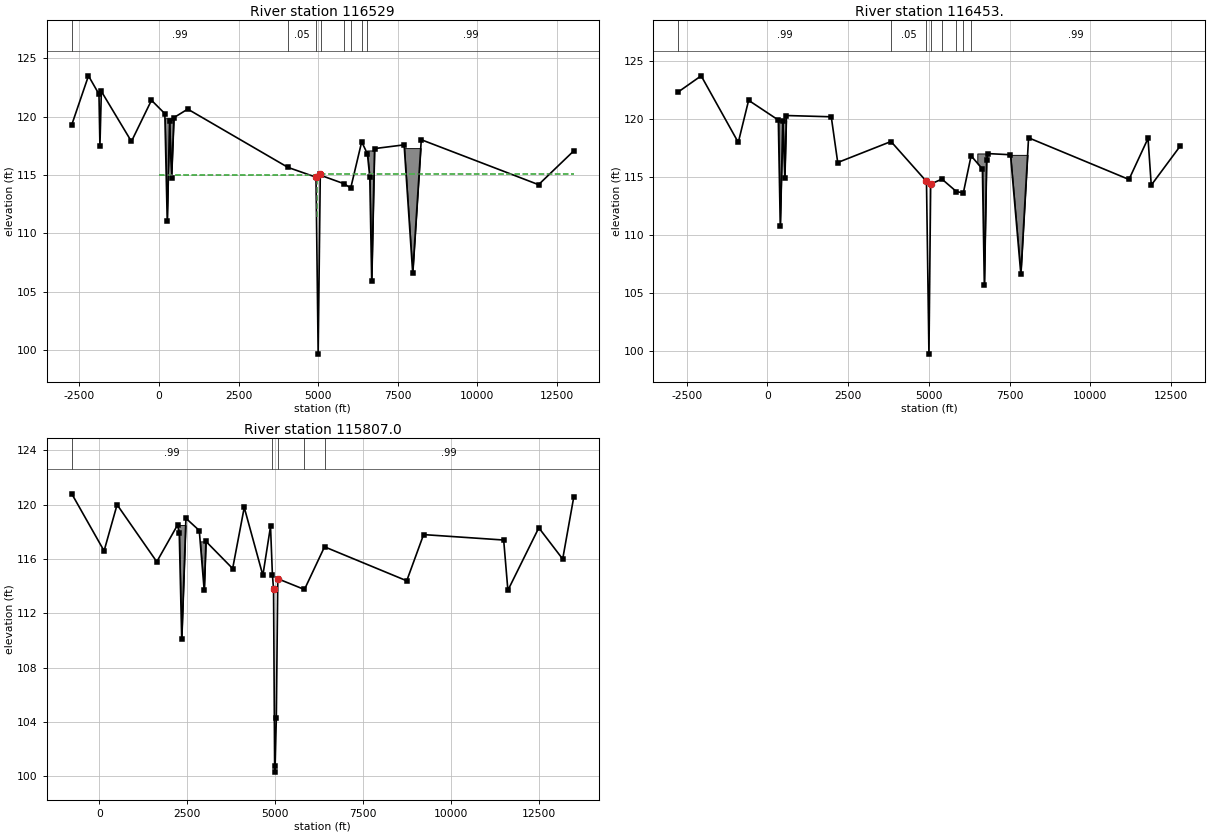
Type RM Length L Ch R = 1 ,116529  ,78.9,76,71.7
XS GIS Cut Line= 4
3054071.4200001213903687.19000063050309.0650519913898034.6145732
3050385.6100006313896214.60000043044696.6499996213891870.8600006
#Sta/Elev= 30
-2737.78   119.3-2213.15  123.49-1883.38  121.92 -1853.4  117.48-1808.44  122.16
  -864.1  117.87 -234.55   121.4  185.16  120.25  260.11  111.09  335.05  119.59
  395.01  114.72  469.96  119.91  904.66  120.64 4052.41  115.65 4933.34  114.81
  5001.2   99.66 5067.73  115.09 5082.66  114.97  5814.3  114.25 6023.77  113.88
 6368.18  117.84 6547.88  116.81 6622.75  114.81 6682.65  105.92  6772.5  117.26
 7700.92  117.58 7970.47   106.6 8240.01  118.0211923.76  114.1713031.89  117.07
#Mann= 8 ,-1 , 0
-2737.78     .99       0 4052.41     .05       0 4933.34     .04       0
 5082.66      .1       0  5814.3     .05       0 6023.77     .08       0
 6368.18      .1       0 6547.88     .99       0
#XS Ineff= 2 , 0
       0 4949.06     115 5069.06       0  115.08
Permanent Ineff=
       F       F
#Block Obstruct= 3 ,-1
     185     484  119.86  6532.9  6772.5   117.1 7685.95    8254   117.3
Bank Sta=4933.34,5067.73
XS Rating Curve= 0 ,0
Exp/Cntr=0.5,0.3

Type RM Length L Ch R = 1 ,116453. ,696.4,646,375.4
BEGIN DESCRIPTION:
Jones - D\S - XS 1
END DESCRIPTION:
XS GIS Cut Line= 5
      3054167.63     13903690.02      3050367.01     13897979.94
      3050447.59     13896743.07      3050430.53     13896210.74
 3044945.7616117 13891991.309467
#Sta/Elev= 30
 -2764.7  122.34 -2054.7  123.73  -904.7  117.99  -584.7  121.62   335.3  119.92
   395.3  110.82   475.3  119.86   535.3  114.89   585.3  120.31  1975.3   120.2
  2175.3  116.26  3825.3  118.07  4924.6  114.63 5000.76   99.75  5054.6  114.41
  5404.1  114.83  5854.1  113.75  6066.7  113.65  6306.7  116.84  6656.7   115.7
  6716.7  105.67  6786.7   116.5  6826.7  117.03  7526.7  116.93  7846.7  106.65
  8086.7  118.39 11196.7   114.8 11786.7  118.34 11886.7  114.31 12786.7  117.69
#Mann= 8 ,-1 , 0
 -2764.7     .99       0  3825.3     .05       0  4924.6     .04       0
  5054.6      .1       0  5404.1     .05       0  5854.1     .08       0
  6066.7      .1       0  6306.7     .99       0
#Block Obstruct= 3 ,-1
  345.37  725.99   119.9 6498.68 6815.86  117.04 7529.52 8227.31  116.92
Bank Sta=4924.6,5054.6
XS Rating Curve= 0 ,0
Exp/Cntr=0.3,0.1

Type RM Length L Ch R = 1 ,115807.0,937.1,859,718.7
BEGIN DESCRIPTION:
Cross Section E100-00-00-X87
END DESCRIPTION:
XS GIS Cut Line= 5
      3054210.51      13901785.2      3051147.28      13897099.7
      3050909.35     13896708.81      3049600.69     13895183.01
      3044658.82     13891393.59
#Sta/Elev= 30
  -787.2   120.8   132.8   116.6   502.8     120  1632.8   115.8  2222.8   118.5
  2272.8   117.9  2342.8   110.1  2462.8     119  2842.8   118.1  2982.8   113.7
  3032.8   117.3  3792.8   115.3  4122.8   119.8  4652.8   114.8  4870.8   118.4
  4924.5  114.85  4957.6  113.78    4988  100.77  4997.8  100.32    5036   104.3
  5078.1  114.55  5836.9  113.76  6408.4   116.9  8748.5   114.4  9228.5   117.8
 11508.5   117.4 11628.5   113.7 12508.5   118.3 13188.5     116   13506   120.6
#Mann= 5 ,-1 , 0
  -787.2     .99       0  4924.5     .04       0  5078.1      .1       0
  5836.9     .08       0  6408.4     .99       0
#Block Obstruct= 2 ,-1
  2222.8  2453.5   118.5  2863.3  3032.8   117.3
Bank Sta=4957.6,5078.1
XS Rating Curve= 0 ,0
Exp/Cntr=0.3,0.1