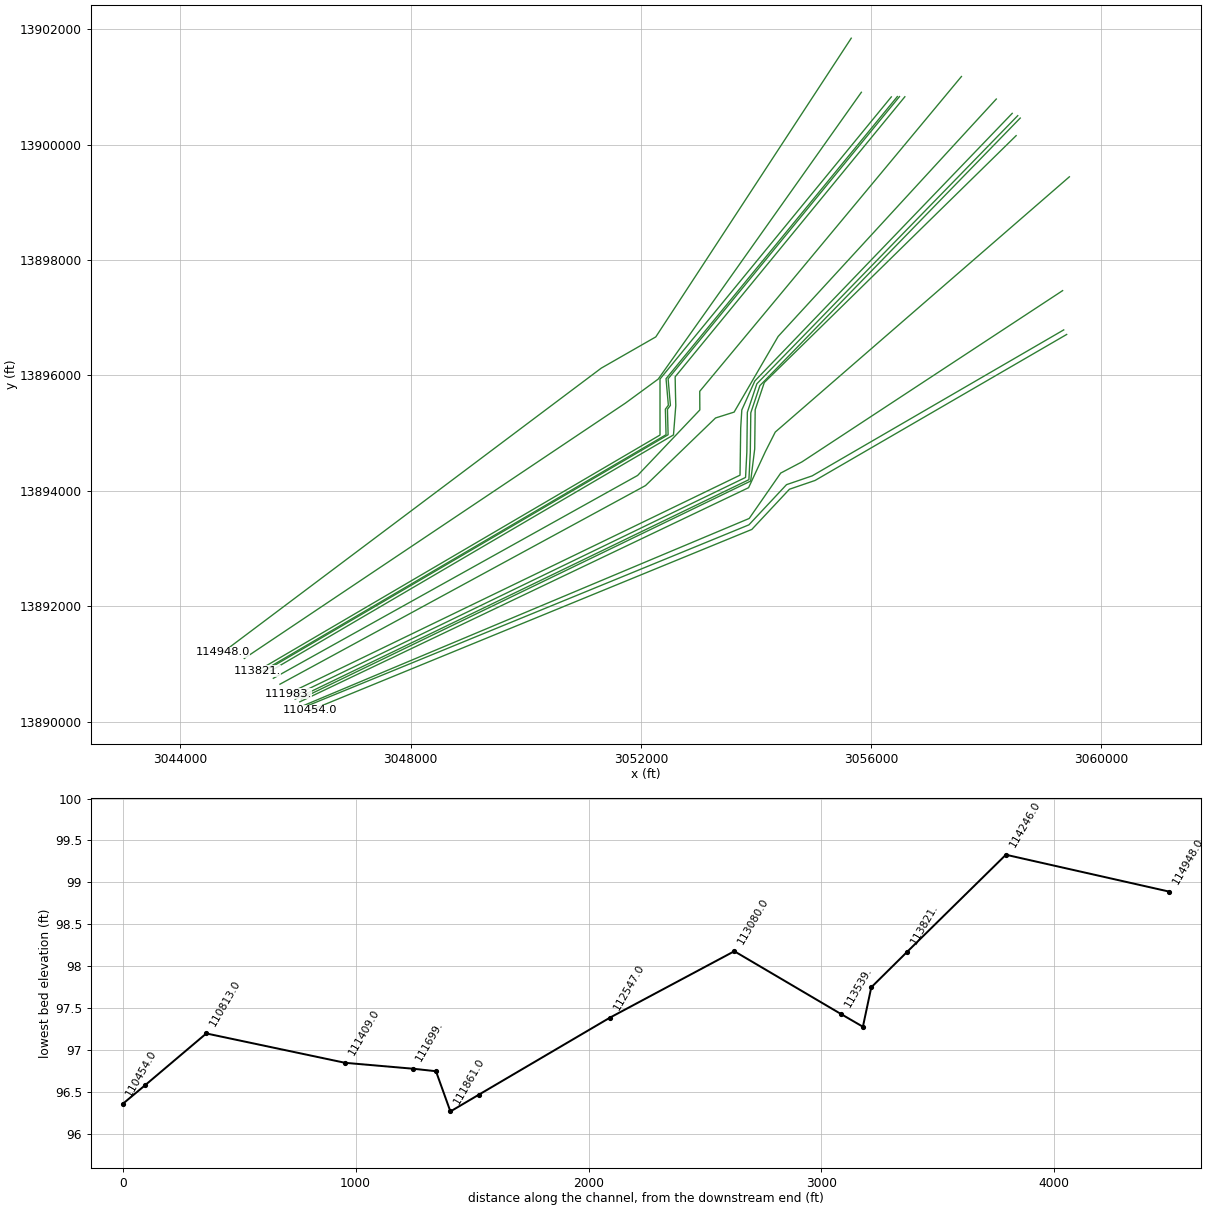
HEC-RAS study E100-00-00.prj: E100-00-00

--- E100-00-00.g02 (geometry) --- (continued)

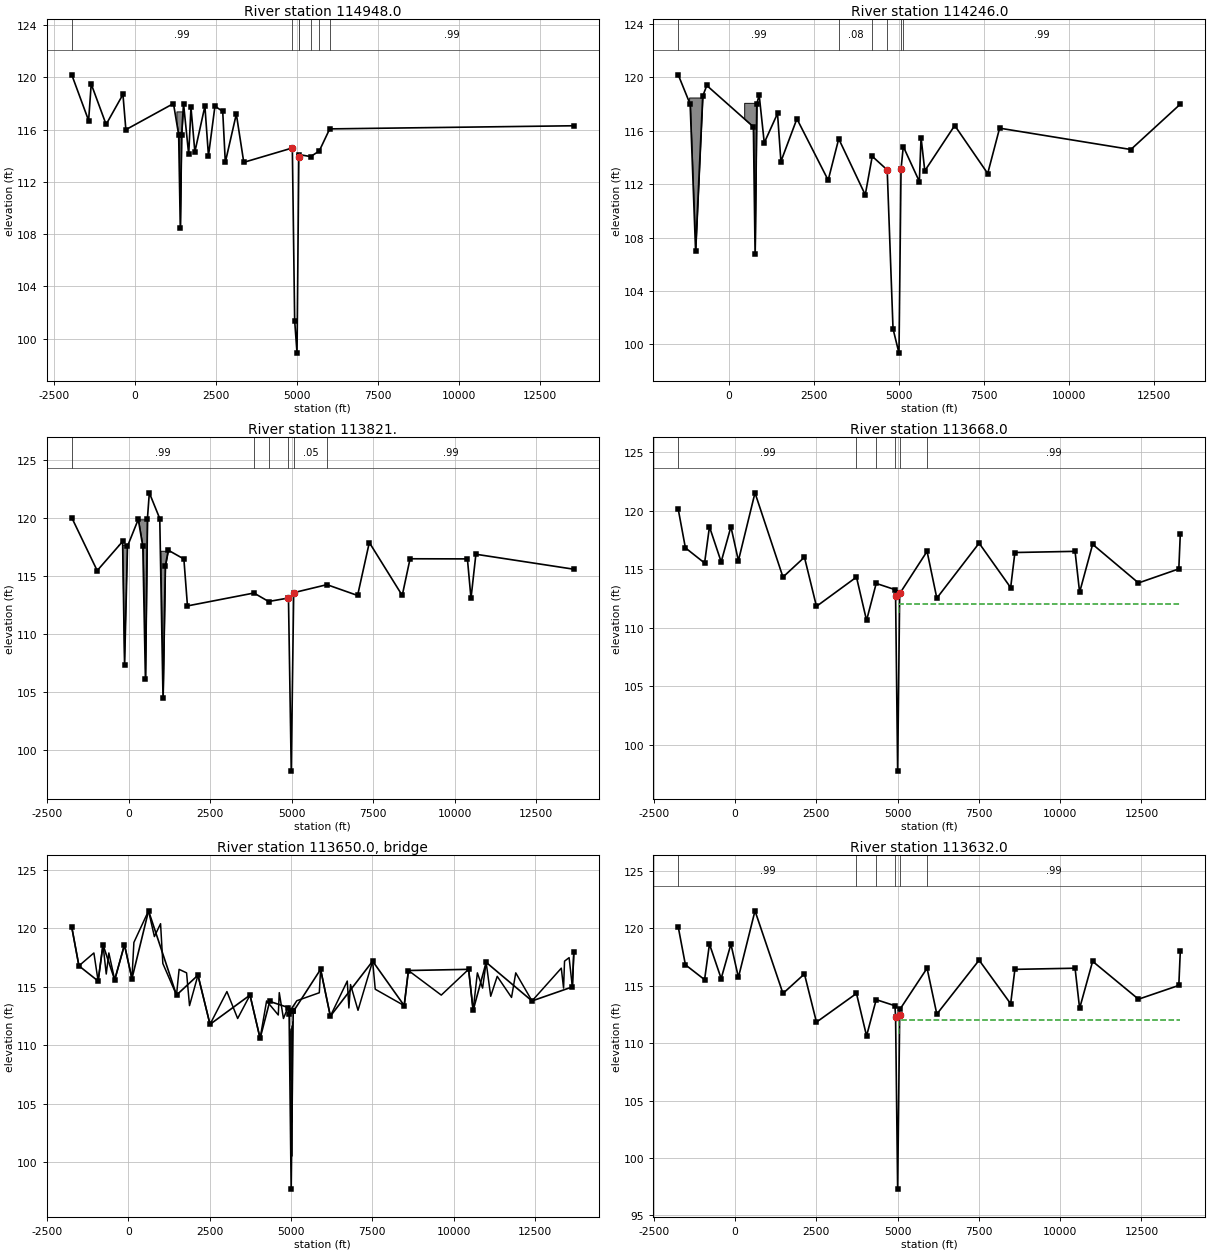
Type RM Length L Ch R = 1 ,114948.0,690.4,702,749.3
BEGIN DESCRIPTION:
Cross Section E100-00-00-X86
END DESCRIPTION:
XS GIS Cut Line= 4
      3055655.96      13901843.8      3052260.47     13896666.33
      3051312.47     13896124.47      3044736.95     13891198.26
#Sta/Elev= 30
 -1950.4   120.2 -1430.4   116.7 -1350.4   119.5  -890.4   116.4  -370.4   118.7
  -280.4     116  1189.6     118  1349.6   115.6  1399.6   108.5  1439.6   115.6
  1499.6     118  1659.6   114.1  1729.6   117.7  1849.6   114.3  2159.6   117.8
  2269.6     114  2469.6   117.8  2709.6   117.4  2789.6   113.5  3129.6   117.2
  3359.6   113.5  4858.9   114.6  4930.6  101.38  5003.7   98.89  5059.2  113.94
  5072.3  114.09  5424.1  113.94  5690.3  114.37  6012.7  116.06 13549.3   116.3
#Mann= 7 ,-1 , 0
 -1950.4     .99       0  4858.9     .04       0  5059.2     .04       0
  5072.3     .05       0  5424.1      .1       0  5690.3     .05       0
  6012.7     .99       0
#Block Obstruct= 2 ,-1
  1279.6  1490.7   117.4    1491  1491.5     100
Bank Sta=4858.9,5059.2
XS Rating Curve= 0 ,0
Exp/Cntr=0.3,0.1

Type RM Length L Ch R = 1 ,114246.0,43.1,425,493.3
BEGIN DESCRIPTION:
Cross Section E100-00-00-X85
END DESCRIPTION:
XS GIS Cut Line= 4
      3055831.76     13900906.21      3052302.96     13895935.53
      3051733.62     13895519.15      3045111.78     13891093.34
#Sta/Elev= 30
 -1491.4   120.2 -1141.4     118  -981.4     107  -771.4   118.6  -651.4   119.4
   718.6   116.3   768.6   106.8   818.6     118   888.6   118.7  1038.6   115.1
  1428.6   117.3  1528.6   113.7  1998.6   116.9  2918.6   112.3  3228.6   115.4
  4008.6   111.2  4214.2  114.09    4654  113.07  4825.6  101.16  5000.7   99.33
  5061.1  113.14  5127.6  114.82  5599.9   112.2  5649.9   115.5  5759.9     113
  6639.9   116.4  7609.9   112.8  7959.9   116.2 11819.9   114.6 13274.6     118
#Mann= 6 ,-1 , 0
 -1491.4     .99       0  3228.6     .08       0  4214.2     .05       0
    4654     .04       0  5061.1     .05       0  5127.6     .99       0
#Block Obstruct= 2 ,-1
 -1171.4  -771.8   118.5   448.6   873.2   118.1
Bank Sta=4654,5061.1
XS Rating Curve= 0 ,0
Exp/Cntr=0.3,0.1

Type RM Length L Ch R = 1 ,113821. ,80.7,153,110.9
BEGIN DESCRIPTION:
HL&P Bridge - U\S - XS 4
END DESCRIPTION:
XS GIS Cut Line= 4
      3056352.01      13900826.3      3052333.72     13895935.98
      3052333.72     13894965.19      3045335.87     13890874.25
#Sta/Elev= 30
 -1745.4     120  -965.4  115.44  -185.4  117.95  -125.4  107.31   -35.4  117.54
   294.6  119.85   434.6  117.52   514.6  106.09   574.6  119.87   634.6  122.14
   954.6  119.92  1054.6  104.46  1124.6  115.84  1214.6   117.2  1694.6  116.44
  1804.6   112.4  3844.6  113.51  4294.6  112.78    4904  113.08  4989.4   98.17
    5064  113.54  6084.8  114.23  7024.8   113.3  7384.8  117.86  8394.8   113.3
  8634.8  116.46 10394.8  116.45 10504.8  113.05 10654.8  116.85 13660.7  115.56
#Mann= 6 ,-1 , 0
 -1745.4     .99       0  3844.6     .08       0  4294.6     .05       0
    4904     .04       0    5064     .05       0  6084.8     .99       0
#Block Obstruct= 3 ,-1
 -308.37  -40.53  117.62   297.8  678.41  119.86  861.67    1200  117.15
Bank Sta=4904,5064
XS Rating Curve= 0 ,0
Exp/Cntr=0.5,0.3

Type RM Length L Ch R = 1 ,113668.0,30.2,36,43
BEGIN DESCRIPTION:
Upstream Section of Bridge/Culvert/Weir
END DESCRIPTION:
XS GIS Cut Line= 6
      3056456.72     13900831.96      3052438.43     13895941.64
      3052478.64     13895482.09      3052426.94     13895413.16
      3052438.43     13894970.85      3045440.57     13890879.91
#Sta/Elev= 30
 -1742.6  120.13 -1522.6  116.83  -932.6  115.53  -782.6  118.63  -422.6  115.63
  -122.6  118.63   107.4  115.73   617.4  121.53  1477.4  114.33  2137.4  116.03
  2507.4  111.83  3737.4  114.33  4047.4  110.63    4344  113.79    4920  113.26
  4939.8  112.75  5003.4   97.75  5065.8  112.93  5071.9  112.94  5907.8  116.53
  6207.8  112.53  7507.8  117.23  8477.8  113.43  8607.8  116.43 10457.8  116.53
 10597.8  113.03 10997.8  117.13 12407.8  113.83 13647.8  115.03 13693.8  118.03
#Mann= 6 ,-1 , 0
 -1742.6     .99       0  3737.4     .08       0    4344     .05       0
    4920     .04       0  5071.9     .05       0  5907.8     .99       0
#XS Ineff= 2 , 0
       0  4936.1   112.1    5059       0     112
Permanent Ineff=
       F       F
Bank Sta=4939.8,5065.8
XS Rating Curve= 0 ,0
Exp/Cntr=0.5,0.3

Type RM Length L Ch R = 3 ,113650.0,,,
BEGIN DESCRIPTION:
HL&P BRIDGE
Structure ID: E100-00-00-54
END DESCRIPTION:
Bridge Culvert--1,0,-1,-1, 0
Deck Dist Width WeirC Skew NumUp NumDn MinLoCord MaxHiCord MaxSubmerge Is_Ogee
10,16,2.6,0, 60, 60, , , 0.95, 0, ,,,
 -1742.6 -1522.6 -1062.6  -932.6  -782.6  -682.6  -602.6  -422.6  -122.6   107.4
   167.4   617.4   797.4   987.4  1057.4  1477.4  1557.4  1787.4  1877.4  2137.4
  2507.4  3027.4  3357.4  3737.4  4047.4  4247.4  4606.8  4636.8  4765.4  4916.4
 4946.01  5177.5  5867.8  5907.8  6207.8  6727.8  6777.8  6827.8  7057.8  7507.8
  7587.8  8477.8  8607.8  9617.8 10457.8 10597.8 10727.8 10887.8 10997.8 11137.8
 11337.8 11777.8 11907.8 12407.8 13307.8 13377.8 13407.8 13547.8 13647.8 13693.8
   120.1   116.8   117.9   115.5   118.6   116.1   117.9   115.6   118.6   115.7
   118.8   121.5   119.3   120.4     117   114.3   116.5   116.2   113.4     116
   111.8   114.6   112.3   114.3   110.6   113.8   112.6  114.51   112.3  113.34
  112.87  113.82   114.5   116.5   112.5   115.5   113.2   115.2     113   117.2
   114.8   113.4   116.4   114.3   116.5     113   116.2   114.9   117.1   114.2
   115.9   114.1   116.2   113.8   116.6   114.9   117.2   117.5     115     118
   120.1   116.8   117.9   115.5   118.6   116.1   117.9   115.6   118.6   115.7
   118.8   121.5   119.3   120.4     117   114.3   116.5   116.2   113.4     116
   111.8   114.6   112.3   114.3   110.6   113.8   112.6   114.5  112.24  113.32
  111.12  113.81   114.5   116.5   112.5   115.5   113.2   115.2     113   117.2
   114.8   113.4   116.4   114.3   116.5     113   116.2   114.9   117.1   114.2
   115.9   114.1   116.2   113.8   116.6   114.9   117.2   117.5     115     118
 -1742.6 -1522.6 -1062.6  -932.6  -782.6  -682.6  -602.6  -422.6  -122.6   107.4
   167.4   617.4   797.4   987.4  1057.4  1477.4  1557.4  1787.4  1877.4  2137.4
  2507.4  3027.4  3357.4  3737.4  4047.4  4247.4  4606.8  4636.8  4765.4  4916.4
 4946.01  5177.5  5867.8  5907.8  6207.8  6727.8  6777.8  6827.8  7057.8  7507.8
  7587.8  8477.8  8607.8  9617.8 10457.8 10597.8 10727.8 10887.8 10997.8 11137.8
 11337.8 11777.8 11907.8 12407.8 13307.8 13377.8 13407.8 13547.8 13647.8 13693.8
   120.1   116.8   117.9   115.5   118.6   116.1   117.9   115.6   118.6   115.7
   118.8   121.5   119.3   120.4     117   114.3   116.5   116.2   113.4     116
   111.8   114.6   112.3   114.3   110.6   113.8   112.6  114.51   112.3  113.34
  112.87  113.82   114.5   116.5   112.5   115.5   113.2   115.2     113   117.2
   114.8   113.4   116.4   114.3   116.5     113   116.2   114.9   117.1   114.2
   115.9   114.1   116.2   113.8   116.6   114.9   117.2   117.5     115     118
   120.1   116.8   117.9   115.5   118.6   116.1   117.9   115.6   118.6   115.7
   118.8   121.5   119.3   120.4     117   114.3   116.5   116.2   113.4     116
   111.8   114.6   112.3   114.3   110.6   113.8   112.6   114.5  112.24  113.32
  111.12  113.81   114.5   116.5   112.5   115.5   113.2   115.2     113   117.2
   114.8   113.4   116.4   114.3   116.5     113   116.2   114.9   117.1   114.2
   115.9   114.1   116.2   113.8   116.6   114.9   117.2   117.5     115     118
Pier Skew, UpSta & Num, DnSta & Num=  ,4963.9, 2 ,4963.9, 2 , 0 , 0 , 0 ,,
       1       1
  104.38  112.35
       1       1
  103.92  111.89
Pier Skew, UpSta & Num, DnSta & Num=  ,4981.1, 2 ,4981.1, 2 , 0 , 0 , 0 ,,
       1       1
  101.26  112.34
       1       1
   100.8  111.88
Pier Skew, UpSta & Num, DnSta & Num=  ,4987.5, 2 ,4987.5, 2 , 0 , 0 , 0 ,,
       1       1
   98.14  112.34
       1       1
   97.68  111.88
Pier Skew, UpSta & Num, DnSta & Num=  ,4998.2, 2 ,4998.2, 2 , 0 , 0 , 0 ,,
       1       1
   97.11  112.33
       1       1
   96.65  111.87
Pier Skew, UpSta & Num, DnSta & Num=  ,5014.9, 2 ,5014.9, 2 , 0 , 0 , 0 ,,
       1       1
  100.35  112.32
       1       1
   99.89  111.86
Pier Skew, UpSta & Num, DnSta & Num=  ,5026.9, 2 ,5026.9, 2 , 0 , 0 , 0 ,,
       1       1
  102.19  112.31
       1       1
  101.73  111.85
Pier Skew, UpSta & Num, DnSta & Num=  ,5031.7, 2 ,5031.7, 2 , 0 , 0 , 0 ,,
       1       1
  103.58  112.31
       1       1
  103.12  111.85
Abutment Skew #Up #Dn= , 2 , 2
  4945.9  4971.9
  111.37  102.95
  4945.9  4971.9
  110.91  102.49
Abutment Skew #Up #Dn= , 2 , 2
  5025.9 5055.19
  103.05  111.37
  5025.9 5055.19
  102.59  110.91
BR Coef= 1 , 1 , 0 ,1.25, 0 ,,,0.8,0,2,0,
WSPro=,,,, 1 ,,,, 0 ,,,, 0 ,,,,-1 ,-1 ,-1 , 0 , 0 , 0 , 0 , 0
BR U #Sta/Elev= 30
 -1742.6   120.1 -1522.6   116.8  -932.6   115.5  -782.6   118.6  -422.6   115.6
  -122.6   118.6   107.4   115.7   617.4   121.5  1477.4   114.3  2137.4     116
  2507.4   111.8  3737.4   114.3  4047.4   110.6    4344  113.76    4920  113.23
  4939.8  112.72  5003.4   97.72  5065.8   112.9  5071.9  112.91  5907.8   116.5
  6207.8   112.5  7507.8   117.2  8477.8   113.4  8607.8   116.4 10457.8   116.5
 10597.8     113 10997.8   117.1 12407.8   113.8 13647.8     115 13693.8     118
BR U #Mann= 6
 -1742.6     .99  3737.4     .08    4344     .05    4920     .04  5071.9     .05
  5907.8     .99
BR U Banks=4939.8,5065.8
BR D #Sta/Elev= 30
 -1742.6   120.1 -1522.6   116.8  -932.6   115.5  -782.6   118.6  -422.6   115.6
  -122.6   118.6   107.4   115.7   617.4   121.5  1477.4   114.3  2137.4     116
  2507.4   111.8  3737.4   114.3  4047.4   110.6    4344  113.76    4920  113.23
  4939.8  112.72  5003.4   97.26  5065.8   112.9  5071.9  112.91  5907.8   116.5
  6207.8   112.5  7507.8   117.2  8477.8   113.4  8607.8   116.4 10457.8   116.5
 10597.8     113 10997.8   117.1 12407.8   113.8 13647.8     115 13693.8     118
BR D #Mann= 6
 -1742.6     .99  3737.4     .08    4344     .05    4920     .04  5071.9     .05
  5907.8     .99
BR D Banks=4939.8,5065.8
BC Design=,, 0 ,, 0 ,,,,,,
BC HTab HWMax=121.53
BC Use User HTab Curves=0
BC User HTab FreeFlow(D)= 0

Type RM Length L Ch R = 1 ,113632.0,75.8,93,122.3
BEGIN DESCRIPTION:
Downstream Section of Bridge/Culvert/Weir
END DESCRIPTION:
XS GIS Cut Line= 6
      3056493.93     13900831.64       3052474.5     13895939.94
      3052514.66     13895480.21      3052462.97     13895411.28
      3052474.43     13894970.19      3045479.12     13890880.74
#Sta/Elev= 30
 -1742.6  120.13 -1522.6  116.83  -932.6  115.53  -782.6  118.63  -422.6  115.63
  -122.6  118.63   107.4  115.73   617.4  121.53  1477.4  114.33  2137.4  116.03
  2507.4  111.83  3737.4  114.33  4047.4  110.63    4344  113.79    4920  113.26
  4939.8  112.28  5003.4   97.28  5065.8  112.46  5071.9  112.94  5907.8  116.53
  6207.8  112.53  7507.8  117.23  8477.8  113.43  8607.8  116.43 10457.8  116.53
 10597.8  113.03 10997.8  117.13 12407.8  113.83 13647.8  115.03 13693.8  118.03
#Mann= 6 ,-1 , 0
 -1742.6     .99       0  3737.4     .08       0    4344     .05       0
    4920     .04       0  5071.9     .05       0  5907.8     .99       0
#XS Ineff= 2 , 0
       0  4936.1   112.1    5059       0     112
Permanent Ineff=
       F       F
Bank Sta=4939.8,5065.8
XS Rating Curve= 0 ,0
Exp/Cntr=0.5,0.3

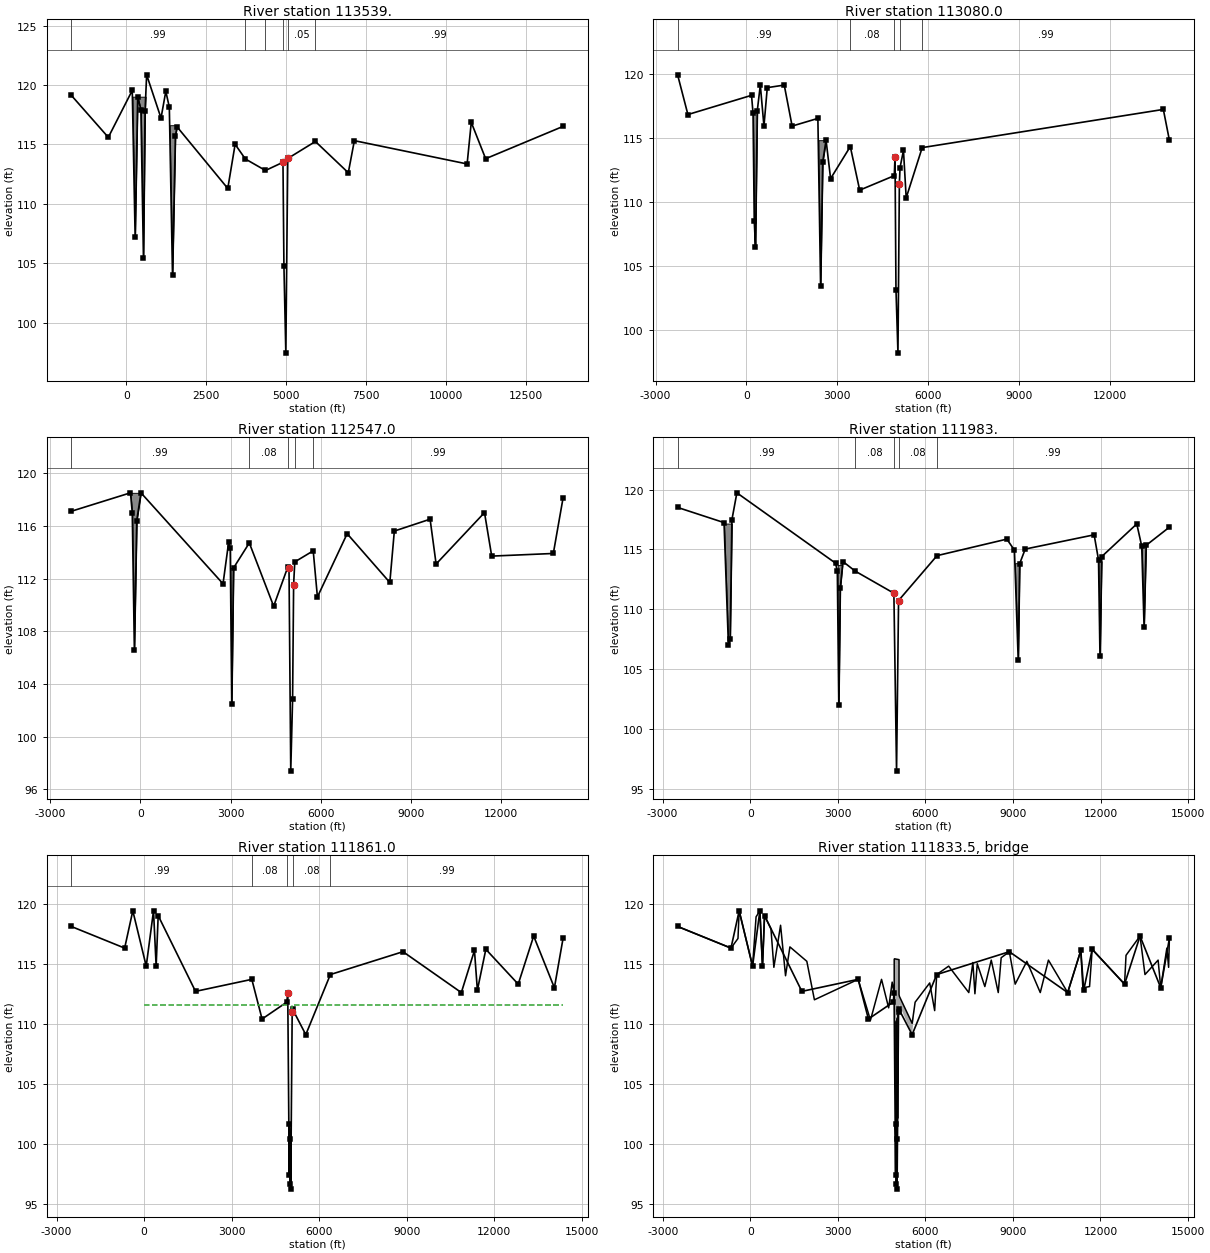
Type RM Length L Ch R = 1 ,113539. ,515.7,459,419.5
BEGIN DESCRIPTION:
HL&P Bridge - D\S - XS 1
END DESCRIPTION:
XS GIS Cut Line= 6
      3056587.32     13900828.81      3052596.58     13895974.31
      3052602.41     13895680.66      3052608.05     13895477.38
      3052567.81     13894967.36      3045572.51     13890877.91
#Sta/Elev= 30
 -1724.5  119.13  -564.5  115.59   185.5  119.54   275.5  107.21   355.5  118.99
   455.5  117.91   535.5  105.47   585.5  117.77   635.5  120.85  1085.5  117.21
  1235.5  119.46  1345.5  118.13  1445.5  103.98  1535.5  115.67  1585.5  116.48
  3175.5  111.29  3405.5     115  3725.5  113.77  4355.5   112.8  4903.5  113.49
  4933.5  104.77 4992.86   97.43  5053.5  113.81  5918.5  115.24  6948.5  112.61
  7138.5  115.31 10668.5  113.35 10798.5  116.85 11248.5  113.79 13671.4  116.51
#Mann= 6 ,-1 , 0
 -1724.5     .99       0  3725.5     .08       0  4355.5     .05       0
  4903.5     .04       0  5053.5     .05       0  5918.5     .99       0
#Block Obstruct= 2 ,-1
  170.93  777.09  119.01 1228.19 1580.62  116.61
Bank Sta=4903.5,5053.5
XS Rating Curve= 0 ,0
Exp/Cntr=0.3,0.1

Type RM Length L Ch R = 1 ,113080.0,698.6,533,384.7
BEGIN DESCRIPTION:
Cross Section E100-00-00-X84
END DESCRIPTION:
XS GIS Cut Line= 5
       3057570.2     13901179.68      3053023.89     13895723.04
      3053025.47     13895400.18      3051944.67     13894264.96
      3045615.94       13890749.
#Sta/Elev= 30
   -2273   119.9   -1933   116.8     167   118.3     217   116.9     257   108.5
     297   106.5     357   117.1     457   119.1     577   115.9     687   118.9
    1247   119.1    1507   115.9    2357   116.5    2447   103.4    2517   113.1
    2627   114.8    2777   111.8    3427   114.3    3737   110.9  4878.9  112.03
  4902.9   113.5  4934.6  103.14  5000.2   98.18  5046.8  111.39    5069  112.66
  5182.2     114  5272.2   110.3  5800.2  114.22 13759.7   117.2 13959.5   114.8
#Mann= 5 ,-1 , 0
   -2273     .99       0    3427     .08       0  4878.9     .04       0
    5069     .08       0  5800.2     .99       0
#Block Obstruct= 2 ,-1
     213     357   117.1  2375.3    2627   114.8
Bank Sta=4902.9,5046.8
XS Rating Curve= 0 ,0
Exp/Cntr=0.3,0.1

Type RM Length L Ch R = 1 ,112547.0,358.3,564,895.7
BEGIN DESCRIPTION:
Cross Section E100-00-00-X83
END DESCRIPTION:
XS GIS Cut Line= 6
      3058175.73     13900789.01      3054385.65     13896673.95
      3053621.13     13895362.88      3053298.18     13895261.05
       3052081.4     13894089.16       3045730.9     13890646.67
#Sta/Elev= 30
   -2304   117.1    -334   118.5    -274     117    -204   106.6    -124   116.4
      16   118.5    2746   111.6    2936   114.8    2986   114.3    3036   102.5
    3096   112.8  3620.5   114.7  4430.5   109.9  4904.3  112.89  4941.3  112.81
  4999.4   97.39  5060.8  102.84    5095  111.54  5133.3  113.26  5746.8   114.1
  5886.8   110.6  6876.2   115.4  8296.2   111.7  8446.2   115.6  9636.2   116.5
  9836.2   113.1 11446.2     117 11686.2   113.7 13736.2   113.9 14059.7   118.1
#Mann= 5 ,-1 , 0
   -2304     .99       0  3620.5     .08       0  4904.3     .04       0
  5133.3     .08       0  5746.8     .99       0
#Block Obstruct= 2 ,-1
    -334      16   118.5  2991.5    3096   112.8
Bank Sta=4941.3,5095
XS Rating Curve= 0 ,0
Exp/Cntr=0.3,0.1

Type RM Length L Ch R = 1 ,111983. ,120,122,178.7
BEGIN DESCRIPTION:
Rio Grande - U\S - XS 4
END DESCRIPTION:
XS GIS Cut Line= 6
      3058452.44     13900540.95      3053980.98     13895902.68
       3053754.7     13895399.91      3053735.52     13895087.74
      3053723.65     13894269.91      3045873.12      13890481.4
#Sta/Elev= 30
 -2486.2  118.51  -896.2  117.24  -746.2  107.02  -686.2  107.52  -626.2  117.48
  -456.2  119.73  2923.8  113.85  2983.8  113.16  3033.8  101.97  3083.8  111.77
  3173.8  113.99  3593.8  113.19  4920.5  111.34 5011.68   96.47  5080.5  110.73
  6398.4  114.48  8788.4  115.86  9048.4  114.94  9178.4  105.75  9228.4  113.81
  9418.4  115.03 11778.4  116.22 11928.4  114.12 11978.4  106.06 12038.4   114.4
 13238.4  117.13 13408.4  115.27 13488.4  108.52 13558.4  115.34 14355.3  116.86
#Mann= 5 ,-1 , 0
 -2486.2     .99       0  3593.8     .08       0  4920.5     .04       0
  5080.5     .08       0  6398.4     .99       0
#Block Obstruct= 5 ,-1
 -933.92 -422.91  117.16 2995.59 3224.67  113.69 8845.82  9251.1  113.85
 11665.212052.86  114.0113145.3713568.28   115.3
Bank Sta=4920.5,5080.5
XS Rating Curve= 0 ,0
Exp/Cntr=0.5,0.3

Type RM Length L Ch R = 1 ,111861.0,60.4,62,101.2
BEGIN DESCRIPTION:
Upstream Section of Bridge/Culvert/Weir
END DESCRIPTION:
XS GIS Cut Line= 6
      3058548.66     13900501.33      3054016.52     13895854.02
      3053850.92      13895360.3      3053842.42     13894672.09
      3053819.87     13894230.29      3045969.33     13890441.78
#Sta/Elev= 30
 -2496.9  118.12  -666.8  116.32  -386.8  119.42    73.2  114.82   323.2  119.42
   413.2  114.82   483.2  119.02  1763.2  112.72  3693.2  113.72  4044.6  110.42
  4895.6  111.83  4925.1  112.58  4976.7   97.47  4978.2  101.65  5002.9    96.7
  5018.7  100.45  5026.5   96.27    5077  110.98  5089.9  111.24  5543.6  109.12
    6386  114.12    8876  116.02   10876  112.62   11326  116.12   11426  112.82
   11716  116.22   12826  113.32   13356  117.32   14066  113.02 14362.8  117.12
#Mann= 5 ,-1 , 0
 -2496.9     .99       0  3693.2     .08       0  4895.6     .04       0
  5089.9     .08       0    6386     .99       0
#XS Ineff= 2 , 0
       0  4928.8   111.6  5082.6       0   111.6
Permanent Ineff=
       F       F
Bank Sta=4925.1,5077
XS Rating Curve= 0 ,0
Exp/Cntr=0.5,0.3

Type RM Length L Ch R = 3 ,111833.5,,,
BEGIN DESCRIPTION:
RIO GRANDE
Structure ID: E100-00-00-53
END DESCRIPTION:
Bridge Culvert--1,0,-1,-1, 0
Deck Dist Width WeirC Skew NumUp NumDn MinLoCord MaxHiCord MaxSubmerge Is_Ogee
10,35,2.6,0, 60, 60, , , 0.95, 0, ,,,
 -2496.9  -666.8  -426.8  -386.8    73.2   193.2   323.2   413.2   483.2   703.2
   803.2  1033.2  1203.2  1353.2  1933.2  2193.2  3693.2  4114.6  4494.6    4738
  4859.3 4928.99  4929.1 4939.11  5093.9 5094.01  5107.3  5543.6    5646    6146
    6316    6386    6796    7486    7626    7696    7776    8036    8256    8496
    8596    8876    9076    9476    9936   10216   10876   11326   11396   11626
   11716   12826   12876   13356   13526   13976   14066   14276   14336 14362.8
  118.11  116.31  117.11  119.41  114.81  118.91  119.41  114.81  119.01  117.91
  114.71  118.21  114.01  116.41  115.21  112.01  113.71  110.31  113.71  111.34
  113.48  112.48  115.38  115.42  115.35  112.45  112.29  110.05  111.81  113.41
  111.11  114.11  114.81  112.61  115.11  112.51  115.01  113.11  115.31  112.61
  115.51  116.01  113.31  115.21  112.61  115.31  112.61  116.11  113.01  113.11
  116.21  113.31  115.71  117.31  114.11  115.31  113.01  116.31  114.71  117.11
  118.11  116.31  117.11  119.41  114.81  118.91  119.41  114.81  119.01  117.91
  114.71  118.21  114.01  116.41  115.21  112.01  113.71  110.31  113.71  111.34
  113.48  111.99  111.97   110.1  111.32  111.32  111.59  109.11  111.81  113.41
  111.11  114.11  114.81  112.61  115.11  112.51  115.01  113.11  115.31  112.61
  115.51  116.01  113.31  115.21  112.61  115.31  112.61  116.11  113.01  113.11
  116.21  113.31  115.71  117.31  114.11  115.31  113.01  116.31  114.71  117.11
 -2496.9  -666.8  -426.8  -386.8    73.2   193.2   323.2   413.2   483.2   703.2
   803.2  1033.2  1203.2  1353.2  1933.2  2193.2  3693.2  4114.6  4494.6    4738
  4859.3 4928.99  4929.1 4939.11  5093.9 5094.01  5107.3  5543.6    5646    6146
    6316    6386    6796    7486    7626    7696    7776    8036    8256    8496
    8596    8876    9076    9476    9936   10216   10876   11326   11396   11626
   11716   12826   12876   13356   13526   13976   14066   14276   14336 14362.8
  118.11  116.31  117.11  119.41  114.81  118.91  119.41  114.81  119.01  117.91
  114.71  118.21  114.01  116.41  115.21  112.01  113.71  110.31  113.71  111.34
  113.48  112.48  115.38  115.42  115.35  112.45  112.29  110.05  111.81  113.41
  111.11  114.11  114.81  112.61  115.11  112.51  115.01  113.11  115.31  112.61
  115.51  116.01  113.31  115.21  112.61  115.31  112.61  116.11  113.01  113.11
  116.21  113.31  115.71  117.31  114.11  115.31  113.01  116.31  114.71  117.11
  118.11  116.31  117.11  119.41  114.81  118.91  119.41  114.81  119.01  117.91
  114.71  118.21  114.01  116.41  115.21  112.01  113.71  110.31  113.71  111.34
  113.48  111.99  111.97   110.1  111.32  111.32  111.59  109.11  111.81  113.41
  111.11  114.11  114.81  112.61  115.11  112.51  115.01  113.11  115.31  112.61
  115.51  116.01  113.31  115.21  112.61  115.31  112.61  116.11  113.01  113.11
  116.21  113.31  115.71  117.31  114.11  115.31  113.01  116.31  114.71  117.11
Pier Skew, UpSta & Num, DnSta & Num=  ,4958.1, 2 ,4958.1, 2 , 0 , 0 , 0 ,,
     1.3     1.3
  102.64  111.52
     1.3     1.3
  103.13  112.01
Pier Skew, UpSta & Num, DnSta & Num=  ,4966.7, 2 ,4966.7, 2 , 0 , 0 , 0 ,,
     1.3     1.3
  100.63  111.52
     1.3     1.3
  101.12  112.01
Pier Skew, UpSta & Num, DnSta & Num=  ,4976.7, 2 ,4976.7, 2 , 0 , 0 , 0 ,,
     1.3     1.3
   96.75  111.52
     1.3     1.3
   97.24  112.01
Pier Skew, UpSta & Num, DnSta & Num=  ,4993.8, 2 ,4993.8, 2 , 0 , 0 , 0 ,,
     1.3     1.3
   96.12  111.52
     1.3     1.3
   96.61  112.01
Pier Skew, UpSta & Num, DnSta & Num=  ,4997, 2 ,4997, 2 , 0 , 0 , 0 ,,
     2.1     2.1
   96.05  111.51
     2.1     2.1
   96.54     112
Pier Skew, UpSta & Num, DnSta & Num=  ,5026.7, 2 ,5026.7, 2 , 0 , 0 , 0 ,,
     1.6     1.6
   95.61  111.49
     1.6     1.6
    96.1  111.98
Pier Skew, UpSta & Num, DnSta & Num=  ,5029.9, 2 ,5029.9, 2 , 0 , 0 , 0 ,,
     1.3     1.3
   96.72  111.49
     1.3     1.3
   97.21  111.98
Pier Skew, UpSta & Num, DnSta & Num=  ,5046.8, 2 ,5046.8, 2 , 0 , 0 , 0 ,,
     1.3     1.3
  101.46  111.47
     1.3     1.3
  101.95  111.96
Pier Skew, UpSta & Num, DnSta & Num=  ,5056.7, 2 ,5056.7, 2 , 0 , 0 , 0 ,,
     1.3     1.3
   104.6  111.46
     1.3     1.3
  105.09  111.95
Pier Skew, UpSta & Num, DnSta & Num=  ,5065.7, 2 ,5065.7, 2 , 0 , 0 , 0 ,,
     1.3     1.3
   104.7  111.45
     1.3     1.3
  105.19  111.94
Abutment Skew #Up #Dn= , 2 , 2
    4939  4958.4
  110.53  103.69
    4939  4958.4
  111.02  104.18
Abutment Skew #Up #Dn= , 2 , 2
  5037.6 5072.59
  100.43  110.45
  5037.6 5072.59
  100.92  110.94
BR Coef= 1 , 1 , 0 ,1.25, 0 ,,,0.8,0,2,0,
WSPro=,,,, 1 ,,,, 0 ,,,, 0 ,,,,-1 ,-1 ,-1 , 0 , 0 , 0 , 0 , 0
BR U #Sta/Elev= 30
 -2496.9  118.11  -666.8  116.31  -386.8  119.41    73.2  114.81   323.2  119.41
   413.2  114.81   483.2  119.01  1763.2  112.71  3693.2  113.71  4044.6  110.41
  4895.6  111.82  4925.1  112.57  4976.7   97.46  4978.2  101.64  5002.9   96.69
  5018.7  100.44  5026.5   96.26    5077  110.97  5089.9  111.23  5543.6  109.11
    6386  114.11    8876  116.01   10876  112.61   11326  116.11   11426  112.81
   11716  116.21   12826  113.31   13356  117.31   14066  113.01 14362.8  117.11
BR U #Mann= 5
 -2496.9     .99  3693.2     .08  4895.6     .04  5089.9     .08    6386     .99
BR U Banks=4925.1,5077
BR D #Sta/Elev= 30
 -2496.9  118.11  -666.8  116.31  -386.8  119.41    73.2  114.81   323.2  119.41
   413.2  114.81   483.2  119.01  1763.2  112.71  3693.2  113.71  4044.6  110.41
  4895.6  111.82  4925.1  113.06  4976.7   97.95  4978.2  102.13  5002.9   97.18
  5018.7  100.93  5026.5   96.75    5077  111.46  5089.9  111.23  5543.6  109.11
    6386  114.11    8876  116.01   10876  112.61   11326  116.11   11426  112.81
   11716  116.21   12826  113.31   13356  117.31   14066  113.01 14362.8  117.11
BR D #Mann= 5
 -2496.9     .99  3693.2     .08  4895.6     .04  5089.9     .08    6386     .99
BR D Banks=4925.1,5077
BC Design=,, 0 ,, 0 ,,,,,,
BC HTab HWMax=119.42
BC Use User HTab Curves=0
BC User HTab FreeFlow(D)= 0

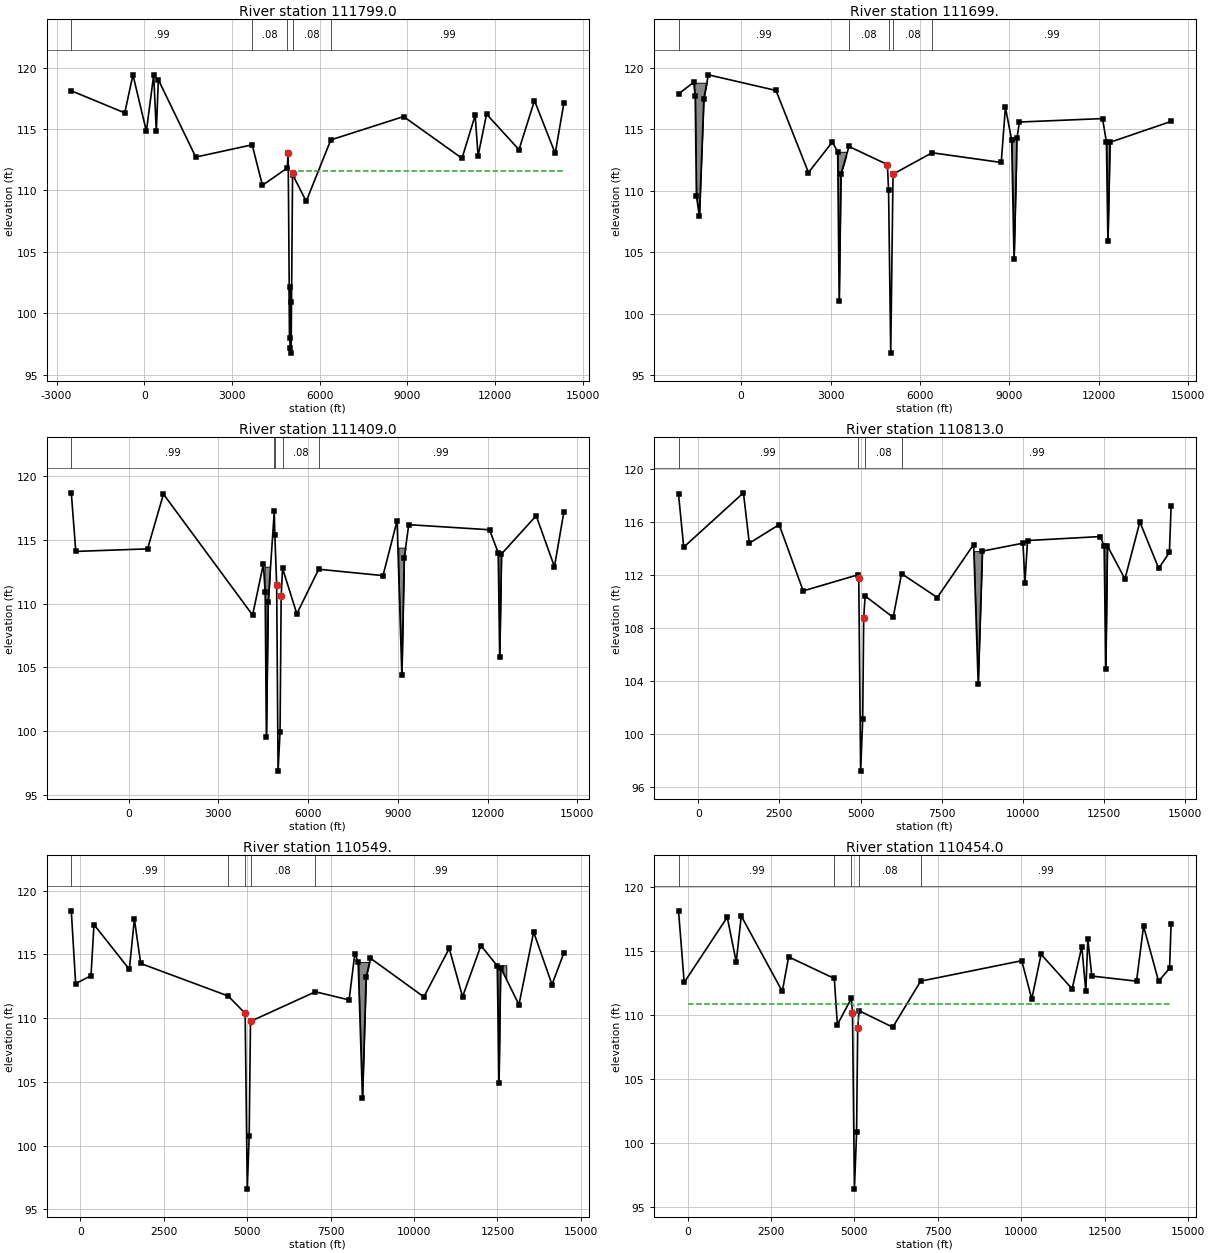
Type RM Length L Ch R = 1 ,111799.0,101,100,56.2
BEGIN DESCRIPTION:
Downstream Section of Bridge/Culvert/Weir
END DESCRIPTION:
XS GIS Cut Line= 6
      3058591.61     13900459.44      3054069.04     13895821.94
       3053910.8     13895350.14       3053902.4     13894670.19
      3053877.98     13894191.71      3045995.41     13890387.74
#Sta/Elev= 30
 -2496.9  118.12  -666.8  116.32  -386.8  119.42    73.2  114.82   323.2  119.42
   413.2  114.82   483.2  119.02  1763.2  112.72  3693.2  113.72  4044.6  110.42
  4895.6  111.83  4925.1  113.06  4976.7   97.95  4978.2  102.13  5002.9   97.18
  5018.7  100.93  5026.5   96.75    5077  111.46  5089.9  111.24  5543.6  109.12
    6386  114.12    8876  116.02   10876  112.62   11326  116.12   11426  112.82
   11716  116.22   12826  113.32   13356  117.32   14066  113.02 14362.8  117.12
#Mann= 5 ,-1 , 0
 -2496.9     .99       0  3693.2     .08       0  4895.6     .04       0
  5089.9     .08       0    6386     .99       0
#XS Ineff= 2 , 0
       0  4928.8   111.6  5082.6       0   111.6
Permanent Ineff=
       F       F
Bank Sta=4925.1,5077
XS Rating Curve= 0 ,0
Exp/Cntr=0.5,0.3

Type RM Length L Ch R = 1 ,111699. ,360,290,30.9
BEGIN DESCRIPTION:
Rio Grande - D\S - XS 1
END DESCRIPTION:
XS GIS Cut Line= 6
       3058520.6      13900154.5      3054145.45     13895875.71
      3053987.21     13895403.91      3053978.81     13894723.96
      3053908.98     13894168.08      3046101.36     13890397.63
#Sta/Elev= 30
 -2101.5  117.86 -1591.5  118.82 -1541.5  117.67 -1501.5  109.59 -1401.5  107.91
 -1251.5  117.48 -1101.5  119.42  1168.5  118.15  2258.5  111.47  3058.5  113.95
  3238.5  113.17  3288.5  101.06  3348.5  111.35  3618.5  113.59  4905.8  112.12
  4945.8  110.08 5019.04   96.78  5095.8  111.34    6406  113.08    8726  112.29
    8866  116.77    9076  114.13    9156  104.44    9256  114.28    9336  115.58
   12126  115.86   12256  113.94   12306  105.88   12376  113.93 14426.4  115.63
#Mann= 5 ,-1 , 0
 -2101.5     .99       0  3618.5     .08       0  4945.8     .04       0
  5095.8     .08       0    6406     .99       0
#Block Obstruct= 4 ,-1
-1568.28-1039.65  118.78 3239.73 3523.61  113.16 8810.57 9233.48  114.33
12070.4812387.67  114.01
Bank Sta=4905.8,5095.8
XS Rating Curve= 0 ,0
Exp/Cntr=0.3,0.1

Type RM Length L Ch R = 1 ,111409.0,746.1,596,356.9
BEGIN DESCRIPTION:
Cross Section E100-00-00-X82
END DESCRIPTION:
XS GIS Cut Line= 5
      3059445.38     13899441.23      3054335.85     13895016.77
      3054163.93     13894677.89      3053872.59     13894052.82
      3046075.29     13890340.68
#Sta/Elev= 30
 -1913.5   118.7 -1763.5   114.1   636.5   114.3  1166.5   118.6  4146.5   109.1
  4506.5   113.1  4566.5   110.9  4606.5    99.5  4666.5   110.1  4870.7  117.24
  4889.3   115.4  4951.1  111.46  4997.4   96.85  5063.9   99.95  5100.9  110.57
  5147.7  112.77  5625.4   109.2  6355.1   112.7  8505.1   112.2  8975.1   116.5
  9135.1   104.4  9215.1   113.6  9365.1   116.2 12065.1   115.8 12355.1     114
 12405.1   105.8 12465.1   113.9 13625.1   116.9 14235.1   112.9 14550.9   117.2
#Mann= 5 ,-1 , 0
 -1913.5     .99       0  4870.7     .08       0  4889.3     .04       0
  5147.7     .08       0  6355.1     .99       0
#Block Obstruct= 3 ,-1
  4546.5    4730   112.9    9020  9268.3   114.4 12353.8   12465   113.9
Bank Sta=4951.1,5100.9
XS Rating Curve= 0 ,0
Exp/Cntr=0.3,0.1

Type RM Length L Ch R = 1 ,110813.0,289.1,264,139.2
BEGIN DESCRIPTION:
Cross Section E100-00-00-X81
END DESCRIPTION:
XS GIS Cut Line= 5
      3059328.18     13897468.39      3054800.98     13894500.79
      3054430.67     13894306.19      3053883.19      13893519.4
      3046151.51     13890280.69
#Sta/Elev= 30
  -608.2   118.1  -448.2   114.1  1391.8   118.2  1571.8   114.4  2491.8   115.8
  3231.8   110.8    4914  112.01    4943  111.76  5001.1    97.2  5065.1  101.11
  5095.4  108.72  5138.7  110.42  6003.3   108.8  6261.8   112.1  7361.8   110.3
  8481.8   114.3  8621.8   103.8  8751.8   113.8 10001.8   114.4 10061.8   111.4
 10141.8   114.6 12381.8   114.9 12501.8   114.2 12551.8   104.9 12601.8   114.2
 13141.8   111.7 13601.8     116 14181.8   112.5 14511.8   113.7 14564.4   117.2
#Mann= 4 ,-1 , 0
  -608.2     .99       0    4914     .04       0  5138.7     .08       0
  6261.8     .99       0
#Block Obstruct= 2 ,-1
    8480  8751.8   113.8 12498.5 12601.8   114.2
Bank Sta=4943,5095.4
XS Rating Curve= 0 ,0
Exp/Cntr=0.3,0.1

Type RM Length L Ch R = 1 ,110549. ,96,95,91.4
BEGIN DESCRIPTION:
West - U\S - XS 4
END DESCRIPTION:
XS GIS Cut Line= 5
      3059347.25     13896787.77      3054976.34     13894257.29
      3054531.26     13894105.24      3053877.98     13893408.54
      3046208.05     13890272.44
#Sta/Elev= 30
  -271.9  118.41  -141.9   112.7   318.1  113.32   408.1  117.33  1468.1  113.82
  1618.1  117.76  1808.1  114.28  4428.1  111.73  4938.7  110.37 5001.54   96.58
  5058.7  100.71  5098.7  109.74  7044.1  112.06  8054.1  111.42  8224.1  115.04
  8324.1  114.41  8454.1  103.69  8564.1   113.2  8694.1  114.69 10294.1  111.66
 11054.1  115.46 11454.1  111.67 12004.1  115.69 12494.1  114.09 12544.1  104.91
 12594.1  113.96 13144.1  111.05 13584.1  116.75 14134.1  112.63 14490.4   115.1
#Mann= 5 ,-1 , 0
  -271.9     .99       0  4428.1     .08       0  4938.7     .04       0
  5098.7     .08       0  7044.1     .99       0
#Block Obstruct= 2 ,-1
 8340.09 8768.28  114.3912495.1512764.76  114.14
Bank Sta=4938.7,5098.7
XS Rating Curve= 0 ,0
Exp/Cntr=0.5,0.3

Type RM Length L Ch R = 1 ,110454.0,109,108,97.4
BEGIN DESCRIPTION:
Upstream Section of Bridge/Culvert/Weir
END DESCRIPTION:
XS GIS Cut Line= 5
      3059398.19     13896708.53      3055027.28     13894178.05
       3054582.2       13894026.      3053928.92     13893329.31
      3046258.99      13890193.2
#Sta/Elev= 30
  -269.6  118.12   -99.6  112.52  1190.4  117.62  1460.4  114.12  1610.4  117.72
  2840.4  111.82  3030.4  114.52  4399.4  112.83  4490.4  109.22  4911.6  111.28
  4944.2  110.17  5001.7   96.36  5066.7   100.8  5100.2  108.96  5141.2  110.31
  6151.3  109.02  6986.4  112.62 10016.4  114.22 10316.4  111.22 10596.4  114.72
 11526.4  112.02 11816.4  115.32 11936.4  111.82 11996.4  115.92 12116.4  113.02
 13456.4  112.62 13666.4  116.92 14116.4  112.62 14446.4  113.62 14492.7  117.12
#Mann= 5 ,-1 , 0
  -269.6     .99       0  4399.4     .08       0  4911.6     .04       0
  5141.2     .08       0  6986.4     .99       0
#XS Ineff= 2 , 0
       0  4944.4   110.8  5114.4       0   110.8
Permanent Ineff=
       F       F
Bank Sta=4944.2,5100.2
XS Rating Curve= 0 ,0
Exp/Cntr=0.5,0.3