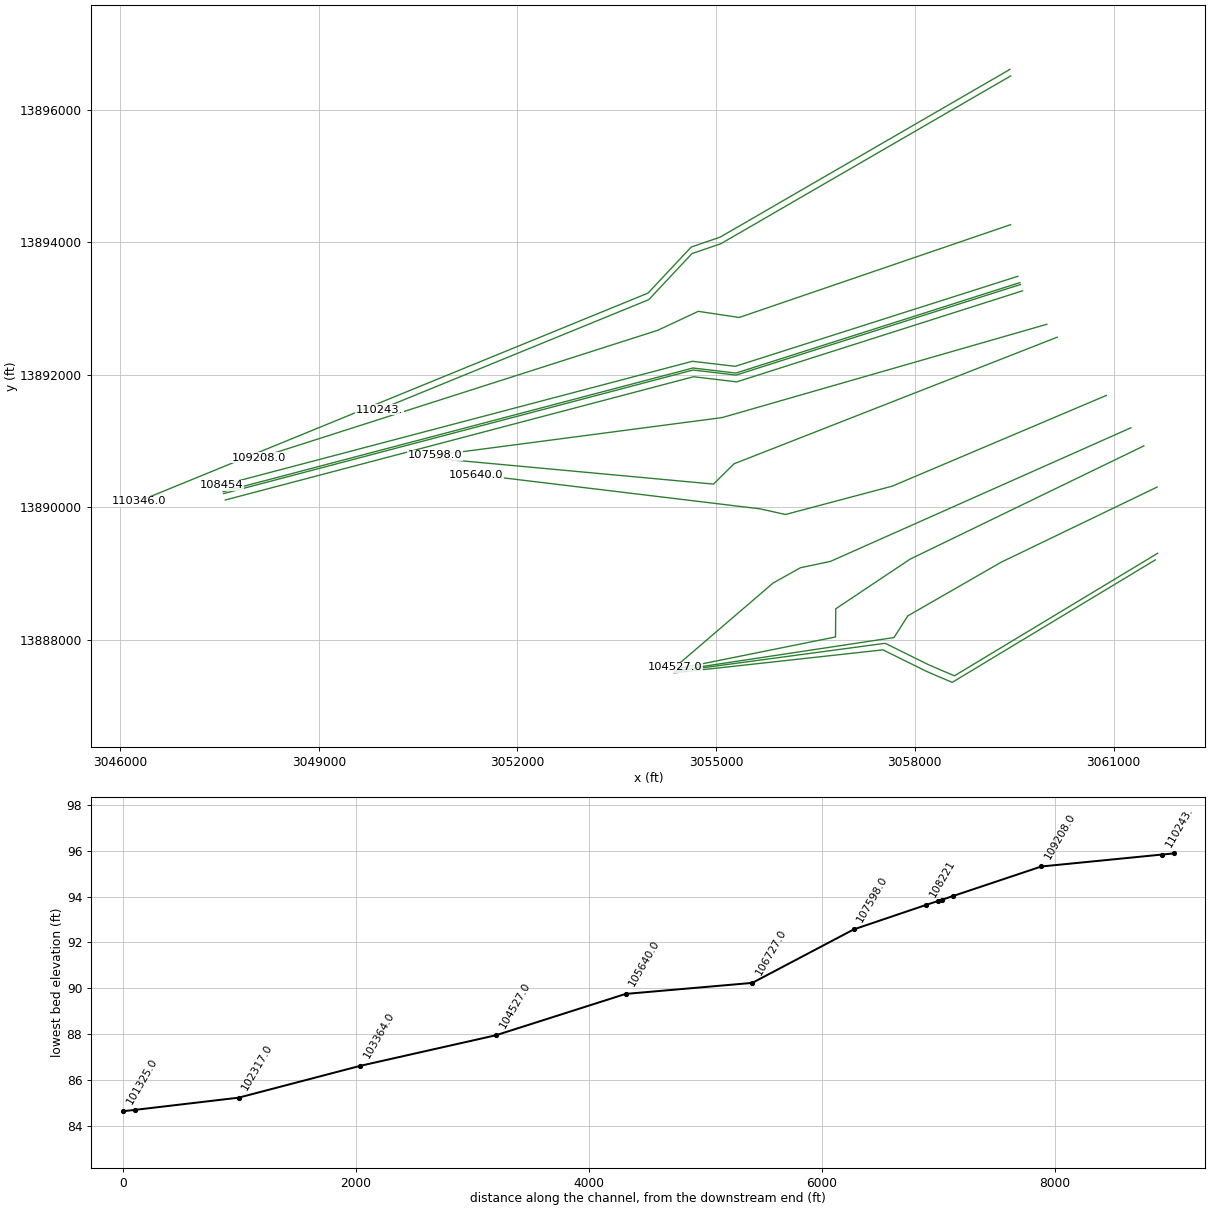
HEC-RAS study E100-00-00.prj: E100-00-00

--- E100-00-00.g02 (geometry) --- (continued)

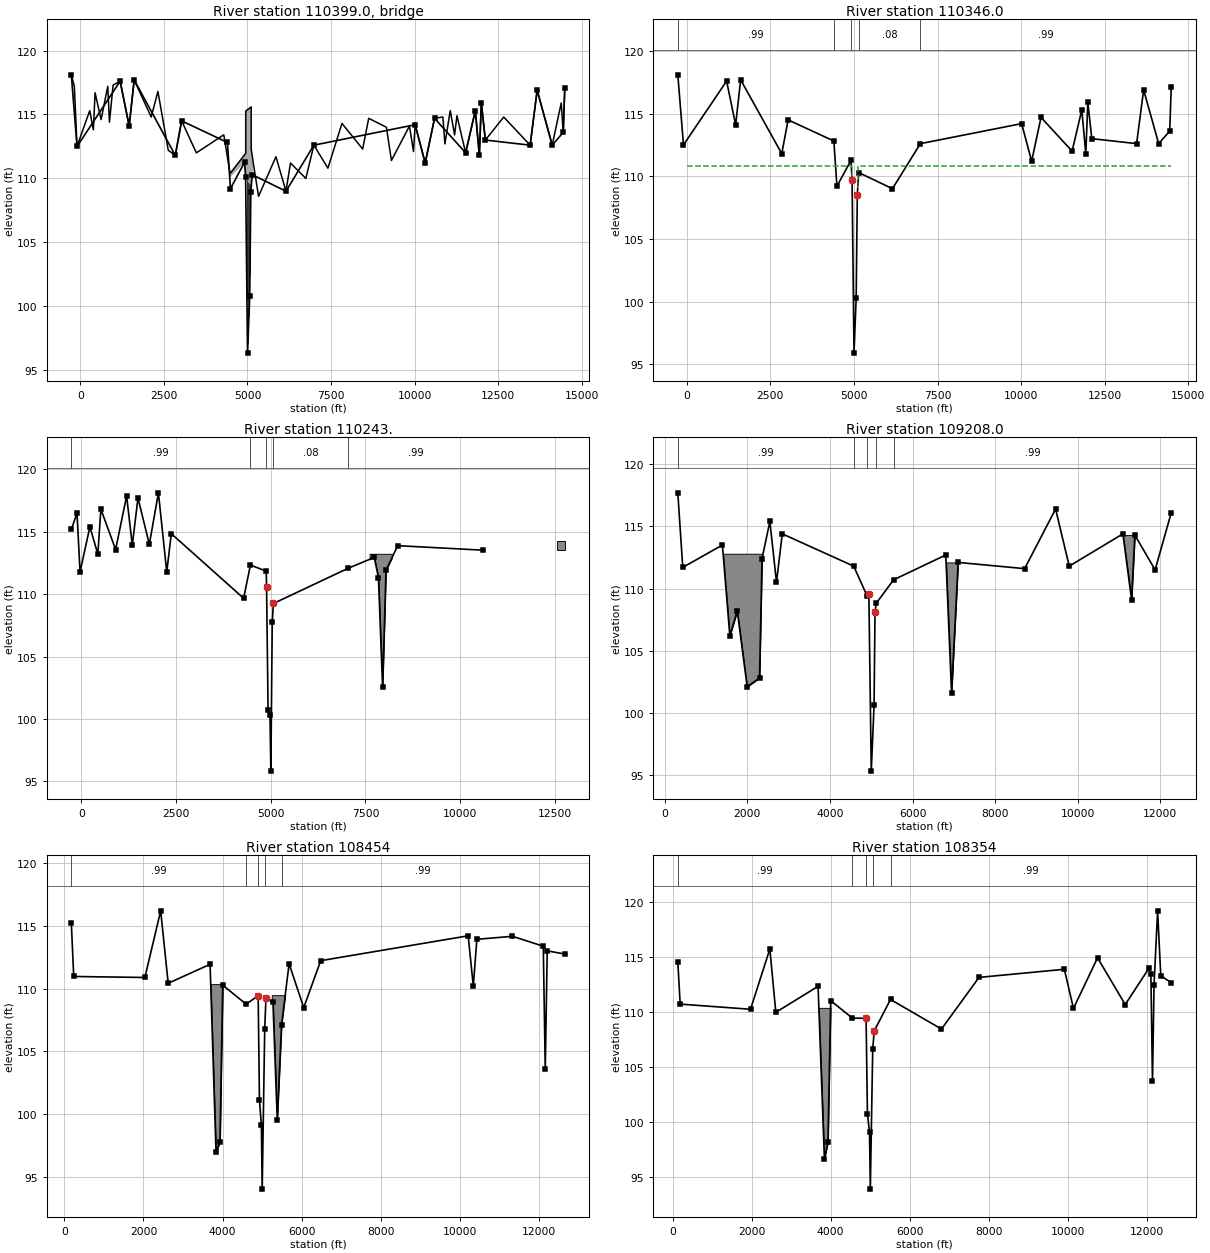
Type RM Length L Ch R = 3 ,110399.0,,,
BEGIN DESCRIPTION:
WEST
Structure ID: E100-00-00-52
END DESCRIPTION:
Bridge Culvert--1,0,-1,-1, 0
Deck Dist Width WeirC Skew NumUp NumDn MinLoCord MaxHiCord MaxSubmerge Is_Ogee
10,90,2.6,0, 60, 60, , , 0.95, 0, ,,,
  -269.6  -179.6   -99.6   280.4   390.4   440.4   620.4   820.4   870.4   980.4
  1190.4  1460.4  1610.4  2120.4  2320.4  2630.4  2840.4  3030.4  3470.4  4290.4
  4480.4 4947.49  4947.6  5111.5 5111.61  5180.8  5331.3  5851.3  6151.3  6286.4
  6746.4  6986.4  7406.4  7826.4  8446.4  8626.4  9156.4  9306.4  9846.4  9966.4
 10016.4 10316.4 10596.4 10846.4 10906.4 11066.4 11196.4 11266.4 11526.4 11816.4
 11936.4 11996.4 12116.4 12666.4 13456.4 13666.4 14116.4 14386.4 14446.4 14492.7
   118.1   117.2   112.5   115.3   113.8   116.7   114.6   117.2   114.4   117.3
   117.6   114.1   117.7   114.8   116.8   112.2   111.8   114.5     112  113.41
  110.38  111.97  115.27  115.59  112.29  111.09   108.6   111.7     109   111.2
     110   112.6   110.8   114.3   112.3   114.7     114   111.4   114.1   112.1
   114.2   111.2   114.7   114.8   112.7   115.3   113.4   114.9     112   115.3
   111.8   115.9     113   114.8   112.6   116.9   112.6   115.9   113.6   117.1
   118.1   117.2   112.5   115.3   113.8   116.7   114.6   117.2   114.4   117.3
   117.6   114.1   117.7   114.8   116.8   112.2   111.8   114.5     112   113.4
   110.1  109.97  109.97  109.41  109.41  110.96   108.6   111.7     109   111.2
     110   112.6   110.8   114.3   112.3   114.7     114   111.4   114.1   112.1
   114.2   111.2   114.7   114.8   112.7   115.3   113.4   114.9     112   115.3
   111.8   115.9     113   114.8   112.6   116.9   112.6   115.9   113.6   117.1
  -269.6  -179.6   -99.6   280.4   390.4   440.4   620.4   820.4   870.4   980.4
  1190.4  1460.4  1610.4  2120.4  2320.4  2630.4  2840.4  3030.4  3470.4  4290.4
  4480.4 4947.49  4947.6  5111.5 5111.61  5180.8  5331.3  5851.3  6151.3  6286.4
  6746.4  6986.4  7406.4  7826.4  8446.4  8626.4  9156.4  9306.4  9846.4  9966.4
 10016.4 10316.4 10596.4 10846.4 10906.4 11066.4 11196.4 11266.4 11526.4 11816.4
 11936.4 11996.4 12116.4 12666.4 13456.4 13666.4 14116.4 14386.4 14446.4 14492.7
   118.1   117.2   112.5   115.3   113.8   116.7   114.6   117.2   114.4   117.3
   117.6   114.1   117.7   114.8   116.8   112.2   111.8   114.5     112  113.41
  110.38  111.97  115.27  115.59  112.29  111.09   108.6   111.7     109   111.2
     110   112.6   110.8   114.3   112.3   114.7     114   111.4   114.1   112.1
   114.2   111.2   114.7   114.8   112.7   115.3   113.4   114.9     112   115.3
   111.8   115.9     113   114.8   112.6   116.9   112.6   115.9   113.6   117.1
  117.65  116.75  112.05  114.85  113.35  116.25  114.15  116.75  113.95  116.85
  117.15  113.65  117.25  114.35  116.35  111.75  111.35  114.05  111.55  112.95
  109.65  109.52  109.52  108.96  108.96  110.51  108.15  111.25  108.55  110.75
  109.55  112.15  110.35  113.85  111.85  114.25  113.55  110.95  113.65  111.65
  113.75  110.75  114.25  114.35  112.25  114.85  112.95  114.45  111.55  114.85
  111.35  115.45  112.55  114.35  112.15  116.45  112.15  115.45  113.15  116.65
Pier Skew, UpSta & Num, DnSta & Num=  ,4984, 2 ,4984, 2 , 0 , 0 , 0 ,,
     1.3     1.3
    99.7  110.94
     1.3     1.3
   99.25  110.49
Pier Skew, UpSta & Num, DnSta & Num=  ,5013.8, 2 ,5013.8, 2 , 0 , 0 , 0 ,,
     1.3     1.3
   97.89  110.93
     1.3     1.3
   97.44  110.48
Pier Skew, UpSta & Num, DnSta & Num=  ,5044.1, 2 ,5044.1, 2 , 0 , 0 , 0 ,,
     1.3     1.3
   98.36  111.04
     1.3     1.3
   97.91  110.59
Pier Skew, UpSta & Num, DnSta & Num=  ,5073.7, 2 ,5073.7, 2 , 0 , 0 , 0 ,,
     1.3     1.3
  101.19  111.15
     1.3     1.3
  100.74   110.7
Abutment Skew #Up #Dn= , 2 , 2
  4944.2  4975.7
  110.11  101.21
  4944.2  4975.7
  109.66  100.76
Abutment Skew #Up #Dn= , 2 , 2
  5066.8 5104.59
   100.8  110.26
  5066.8 5104.59
  100.35  109.81
BR Coef= 1 , 1 , 0 ,1.25, 0 ,,,0.8,0,2,0,
WSPro=,,,, 1 ,,,, 0 ,,,, 0 ,,,,-1 ,-1 ,-1 , 0 , 0 , 0 , 0 , 0
BR U #Sta/Elev= 30
  -269.6   118.1   -99.6   112.5  1190.4   117.6  1460.4   114.1  1610.4   117.7
  2840.4   111.8  3030.4   114.5  4399.4  112.81  4490.4   109.2  4911.6  111.26
  4944.2  110.15  5001.7   96.34  5066.7  100.78  5100.2  108.94  5141.2  110.29
  6151.3     109  6986.4   112.6 10016.4   114.2 10316.4   111.2 10596.4   114.7
 11526.4     112 11816.4   115.3 11936.4   111.8 11996.4   115.9 12116.4     113
 13456.4   112.6 13666.4   116.9 14116.4   112.6 14446.4   113.6 14492.7   117.1
BR U #Mann= 5
  -269.6     .99  4399.4     .08  4911.6     .04  5141.2     .08  6986.4     .99
BR U Banks=4944.2,5100.2
BR D #Sta/Elev= 30
  -269.6   118.1   -99.6   112.5  1190.4   117.6  1460.4   114.1  1610.4   117.7
  2840.4   111.8  3030.4   114.5  4399.4  112.81  4490.4   109.2  4911.6  111.26
  4944.2   109.7  5001.7   95.89  5066.7  100.33  5100.2  108.49  5141.2  110.29
  6151.3     109  6986.4   112.6 10016.4   114.2 10316.4   111.2 10596.4   114.7
 11526.4     112 11816.4   115.3 11936.4   111.8 11996.4   115.9 12116.4     113
 13456.4   112.6 13666.4   116.9 14116.4   112.6 14446.4   113.6 14492.7   117.1
BR D #Mann= 5
  -269.6     .99  4399.4     .08  4911.6     .04  5141.2     .08  6986.4     .99
BR D Banks=4944.2,5100.2
BC Design=,, 0 ,, 0 ,,,,,,
BC HTab HWMax=118.12
BC Use User HTab Curves=0
BC User HTab FreeFlow(D)= 0

Type RM Length L Ch R = 1 ,110346.0,104,103,76
BEGIN DESCRIPTION:
Downstream Section of Bridge/Culvert/Weir
END DESCRIPTION:
XS GIS Cut Line= 5
      3059435.86     13896610.01      3055059.86     13894076.57
      3054623.35     13893927.45      3053971.35     13893232.12
      3046289.31     13890091.06
#Sta/Elev= 30
  -269.6  118.12   -99.6  112.52  1190.4  117.62  1460.4  114.12  1610.4  117.72
  2840.4  111.82  3030.4  114.52  4399.4  112.83  4490.4  109.22  4911.6  111.28
  4944.2  109.69  5001.7   95.88  5066.7  100.32  5100.2  108.48  5141.2  110.31
  6151.3  109.02  6986.4  112.62 10016.4  114.22 10316.4  111.22 10596.4  114.72
 11526.4  112.02 11816.4  115.32 11936.4  111.82 11996.4  115.92 12116.4  113.02
 13456.4  112.62 13666.4  116.92 14116.4  112.62 14446.4  113.62 14492.7  117.12
#Mann= 5 ,-1 , 0
  -269.6     .99       0  4399.4     .08       0  4911.6     .04       0
  5141.2     .08       0  6986.4     .99       0
#XS Ineff= 2 , 0
       0  4944.4   110.8  5114.4       0   110.8
Permanent Ineff=
       F       F
Bank Sta=4944.2,5100.2
XS Rating Curve= 0 ,0
Exp/Cntr=0.5,0.3

Type RM Length L Ch R = 1 ,110243. ,1109.1,1035,722.6
BEGIN DESCRIPTION:
West - D\S - XS 1
END DESCRIPTION:
XS GIS Cut Line= 5
      3059447.18     13896510.96      3055071.18     13893977.52
      3054634.67      13893828.4      3053982.67     13893133.07
      3049919.23      13891471.6
#Sta/Elev= 30
  -268.2  115.19  -118.2  116.47   -38.2  111.78   221.8  115.39   431.8   113.2
   511.8   116.8   901.8  113.57  1191.8  117.86  1341.8  113.91  1491.8   117.7
  1791.8  113.99  2031.8  118.11  2251.8  111.77  2371.8  114.84  4281.8  109.67
  4461.8  112.33  4878.3  111.84  4888.3  110.56  4928.3  100.69  4978.3  100.34
 5001.46   95.83  5038.3  107.74  5068.3  109.25  7042.7  112.07  7732.7  112.94
  7842.7  111.33  7952.7  102.54  8042.7  111.91  8352.7  113.88 10592.7  113.52
#Mann= 5 ,-1 , 0
  -268.2     .99       0  4461.8     .08       0  4878.3     .04       0
  5068.3     .08       0  7042.7     .99       0
#Block Obstruct= 2 ,-1
 7610.57 8197.36  113.2312558.5912764.76  114.23
Bank Sta=4888.3,5068.3
XS Rating Curve= 0 ,0
Exp/Cntr=0.3,0.1

Type RM Length L Ch R = 1 ,109208.0,723,754,763
BEGIN DESCRIPTION:
Cross Section E100-00-00-X80
END DESCRIPTION:
XS GIS Cut Line= 5
      3059445.38     13894264.96      3055346.86     13892863.64
      3054730.41     13892956.73      3054118.65     13892670.36
      3048098.18     13890744.52
#Sta/Elev= 30
   313.5   117.7   433.5   111.7  1393.5   113.5  1573.5   106.2  1753.5   108.2
  1993.5   102.1  2293.5   102.8  2353.5   112.4  2543.5   115.4  2703.5   110.5
  2843.5   114.4  4573.5   111.8  4904.3  109.37    4941  109.56  4999.1   95.31
  5066.8  100.61  5090.2  108.13  5119.5  108.81  5538.4   110.7  6803.9   112.7
  6943.9   101.6  7103.9   112.1  8713.9   111.6  9463.9   116.4  9793.9   111.8
 11093.9   114.4 11303.9   109.1 11383.9   114.3 11873.9   111.5 12264.9   116.1
#Mann= 5 ,-1 , 0
   313.5     .99       0  4573.5     .08       0  4904.3     .04       0
  5119.5     .08       0  5538.4     .99       0
#Block Obstruct= 3 ,-1
  1390.2  2363.5   112.8    6796  7103.9   112.1 11093.6 11383.9   114.3
Bank Sta=4941,5090.2
XS Rating Curve= 0 ,0
Exp/Cntr=0.3,0.1

Type RM Length L Ch R = 1 ,108454  ,100.2,100,98
BEGIN DESCRIPTION:
PIPELINE - XS4
-Right overbank geometry revised.  The effective cross section cut through E111-00-00 and over-estimated conveyance. (PBS&J October 2009)
-Right bank location modified (PBS&J October 2009)
END DESCRIPTION:
XS GIS Cut Line= 4
        3059555.      13893485.5      3055288.17     13892126.01
      3054642.29     13892202.55      3047530.44     13890330.64
#Sta/Elev= 30
   175.2  115.21   235.2  110.97  2035.2  110.89  2435.2   116.2  2625.2  110.43
  3685.2  111.94  3835.2   96.99  3935.2   97.77  4005.2  110.28  4595.2  108.77
 4901.57  109.43 4933.81  101.11 4983.41   99.12 5003.13   94.03 5067.16  106.77
 5098.02  109.23  5275.4  108.92  5383.9   99.56  5493.9  107.14  5683.9  111.98
  6053.9  108.49  6483.9  112.23 10213.9  114.21 10343.9  110.21 10433.9  113.93
 11333.9  114.17 12113.9  113.38 12163.9  103.57 12213.9  113.01   12658  112.76
#Mann= 5 ,-1 , 0
   175.2     .99       0  4595.2     .08       0 4901.57     .04       0
 5067.16     .08       0  5493.9     .99       0
#Block Obstruct= 2 ,-1
    3600  4015.2  110.36 5245.84    5646  109.48
Bank Sta=4901.57,5098.02
XS Rating Curve= 0 ,0
Exp/Cntr=0.3,0.1

Type RM Length L Ch R = 1 ,108354  ,30.3,31,27
BEGIN DESCRIPTION:
PIPELINE - XS3
-Modified right bank location (PBS&J October 2009)
END DESCRIPTION:
XS GIS Cut Line= 4
       3059585.5      13893390.2       3055297.9     13892024.16
      3054649.38     13892101.01      3047555.89     13890233.93
#Sta/Elev= 30
   131.3  114.57   191.3   110.7  1971.3  110.23  2461.3  115.72  2611.3  109.95
  3681.3  112.32  3841.3   96.63  3931.3   98.15  4001.3  111.01  4551.3  109.42
 4896.34  109.41 4930.41  100.71 4982.82   99.05 5003.66   93.86  5064.1  106.59
  5101.3  108.25  5514.3  111.12  6804.3  108.43  7754.3  113.13  9914.3  113.87
 10144.3  110.31 10754.3  114.91 11454.3  110.66 12054.3  113.96 12104.3  113.43
 12144.3  103.66 12184.3  112.47 12274.3  119.19 12354.3  113.28 12619.4  112.65
#Mann= 5 ,-1 , 0
   131.3     .99       0  4551.3     .08       0 4896.34     .04       0
  5064.1     .08       0  5514.3     .99       0
#XS Ineff= 2 , 0
       0  4900.5  108.25  5101.4       0  108.25
Permanent Ineff=
       F       F
#Block Obstruct= 1 ,-1
    3600  4001.3  110.36
Bank Sta=4896.34,5101.3
XS Rating Curve= 0 ,0
Exp/Cntr=0.3,0.1

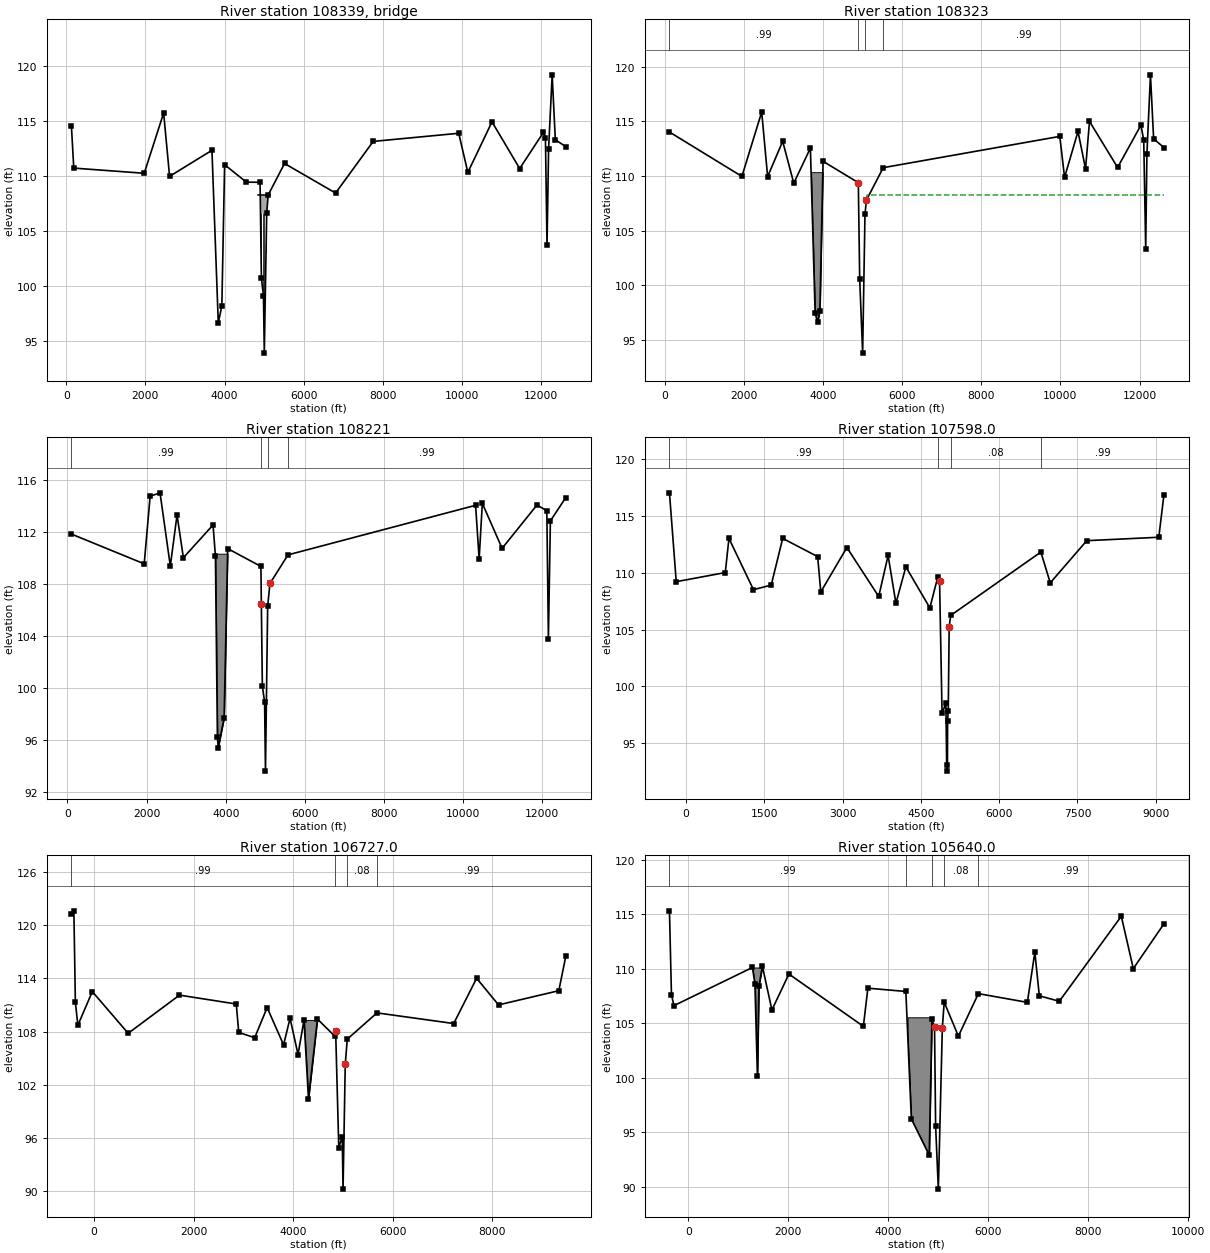
Type RM Length L Ch R = 3 ,108339  ,,,
BEGIN DESCRIPTION:
PIPELINE
END DESCRIPTION:
Bridge Culvert--1,0,-1,-1, 0
Deck Dist Width WeirC Skew NumUp NumDn MinLoCord MaxHiCord MaxSubmerge Is_Ogee
10.5,10,2.6,0, 2, 2, , , 0.95, 0, 0,0,,
    4850    5150
  108.25  108.25
  106.58  106.58
    4850    5150
  108.25  108.25
  106.58  106.58
Pier Skew, UpSta & Num, DnSta & Num=  ,4927, 2 ,4927, 2 , 0 , 0 , 0 ,,
     .75     .75
       0  106.58
     .75     .75
       0  106.58
Pier Skew, UpSta & Num, DnSta & Num=  ,4967, 2 ,4967, 2 , 0 , 0 , 0 ,,
     .75     .75
       0  106.58
     .75     .75
       0  106.58
Pier Skew, UpSta & Num, DnSta & Num=  ,5007, 2 ,5007, 2 , 0 , 0 , 0 ,,
     .75     .75
       0  106.58
     .75     .75
       0  106.58
Pier Skew, UpSta & Num, DnSta & Num=  ,5047, 2 ,5047, 2 , 0 , 0 , 0 ,,
     .75     .75
       0  106.58
     .75     .75
       0  106.58
BR Coef=-1 , 1 , 0 ,1.25, 0 ,,,0.8,0,2,0,
WSPro=,,,, 1 ,,,, 0 ,,,, 0 ,,,,-1 ,-1 ,-1 , 0 , 0 , 0 , 0 , 0
BC Design=,, 0 ,, 0 ,,,,,,
BC HTab HWMax=119.39
BC Use User HTab Curves=0
BC User HTab FreeFlow(D)= 0

Type RM Length L Ch R = 1 ,108323  ,99,102,103
BEGIN DESCRIPTION:
PIPELINE - XS2
-Modified right bank location (PBS&J October 2009)
END DESCRIPTION:
XS GIS Cut Line= 4
      3059594.61      13893361.6      3055300.82      13891993.6
      3054651.51     13892070.55      3047563.53     13890204.92
#Sta/Elev= 30
     124  114.03    1954  109.97    2454  115.86    2604  109.95    2984  113.18
    3264  109.35    3684  112.56    3804   97.47    3864   96.63    3924   97.67
    4004  111.35 4894.72   109.4 4929.35  100.58 5003.83   93.81 5063.15  106.53
  5100.5  107.81  5524.3  110.77  9984.3  113.63 10104.3  109.88 10444.3  114.08
 10634.3  110.66 10734.3     115 11444.3  110.79 12034.3  114.66 12104.3  113.28
 12154.3  103.32 12184.3  111.98 12274.3  119.26 12354.3  113.41 12613.7  112.61
#Mann= 4 ,-1 , 0
     124     .99       0 4894.72     .04       0 5063.15     .08       0
  5524.3     .99       0
#XS Ineff= 2 , 0
       0    4899  108.25    5114       0  108.25
Permanent Ineff=
       F       F
#Block Obstruct= 1 ,-1
    3600    4004  110.36
Bank Sta=4894.72,5100.5
XS Rating Curve= 0 ,0
Exp/Cntr=0.3,0.1

Type RM Length L Ch R = 1 ,108221  ,608.79,623,644.42
BEGIN DESCRIPTION:
PIPELINE - XS1
-Modified left & right bank location (PBS&J October 2009)
END DESCRIPTION:
XS GIS Cut Line= 4
       3059624.9       13893266.      3055310.55     13891891.75
       3054658.6     13891969.01      3047588.98     13890108.21
#Sta/Elev= 30
    99.7  111.87  1939.7  109.58  2089.7  114.78  2339.7  115.04  2599.7  109.41
  2769.7  113.34  2929.7  110.05  3679.7  112.57  3739.7  110.17  3789.7   96.27
  3809.7   95.44  3959.7   97.74  4049.7  110.75 4889.39  109.38    4900 106.454
 4925.88  100.17 4982.04   98.96 5004.37   93.64 5060.03  106.35  5117.8  108.07
  5574.3  110.27 10314.3  114.08 10404.3  109.96 10484.3  114.23 10984.3  110.77
 11864.3   114.1 12114.3  113.67 12154.3  103.83 12204.3  112.88 12594.7  114.68
#Mann= 4 ,-1 , 0
    99.7     .99       0 4889.39     .04       0 5060.03     .08       0
  5574.3     .99       0
#Block Obstruct= 1 ,-1
    3600  4049.7  110.36
Bank Sta=4900,5117.8
XS Rating Curve= 0 ,0
Exp/Cntr=0.3,0.1

Type RM Length L Ch R = 1 ,107598.0,772.6,871,1009.1
BEGIN DESCRIPTION:
Cross Section E100-00-00-X79
END DESCRIPTION:
XS GIS Cut Line= 4
      3059992.31     13892760.91      3055090.42     13891352.36
      3054686.78     13891299.29      3050752.72     13890782.48
#Sta/Elev= 30
  -319.3     117  -189.3   109.2   750.7     110   820.7     113  1290.7   108.5
  1630.7   108.9  1850.7     113  2520.7   111.4  2580.7   108.3  3080.7   112.2
  3690.7   107.9  3870.7   111.5  4020.7   107.3  4210.7   110.5  4670.7   106.9
  4821.9  109.59  4856.8  109.28  4904.7   97.64  4978.4   98.54  4992.8   93.14
  5007.7   92.57    5011   96.94  5023.4   97.88    5041  105.23  5070.5  106.24
  6798.1   111.8  6978.1   109.1  7678.1   112.8  9058.1   113.1  9155.9   116.8
#Mann= 4 ,-1 , 0
  -319.3     .99       0  4821.9     .04       0  5070.5     .08       0
  6798.1     .99       0
Bank Sta=4856.8,5041
XS Rating Curve= 0 ,0
Exp/Cntr=0.3,0.1

Type RM Length L Ch R = 1 ,106727.0,1159.1,1087,615.4
BEGIN DESCRIPTION:
Cross Section E100-00-00-X78
END DESCRIPTION:
XS GIS Cut Line= 4
      3060148.57     13892565.58      3055269.48     13890654.37
       3054959.8     13890348.11      3050726.81      13890739.4
#Sta/Elev= 30
  -453.3   121.2  -403.3   121.6  -373.3   111.3  -323.3   108.7   -33.3   112.5
   686.7   107.8  1716.7   112.1  2856.7   111.1  2906.7   107.9  3226.7   107.3
  3476.7   110.7  3806.7   106.5  3936.7   109.5  4096.7   105.4  4216.7   109.3
  4306.7   100.4  4486.7   109.4  4836.5  107.47  4852.1  108.03    4915   94.92
  4984.7   96.16  5000.7   90.24  5044.9  104.31  5085.5  107.14  5682.3   110.1
  7222.3   108.9  7682.3     114  8122.3     111  9332.3   112.6  9473.3   116.5
#Mann= 4 ,-1 , 0
  -453.3     .99       0  4836.5     .04       0  5085.5     .08       0
  5682.3     .99       0
#Block Obstruct= 2 ,-1
  4216.7    4484   109.3  4484.2  4484.3     100
Bank Sta=4852.1,5044.9
XS Rating Curve= 0 ,0
Exp/Cntr=0.3,0.1

Type RM Length L Ch R = 1 ,105640.0,912.9,1113,1251.5
BEGIN DESCRIPTION:
Cross Section E100-00-00-X77
END DESCRIPTION:
XS GIS Cut Line= 5
      3060890.83     13891686.59      3057659.22     13890317.35
      3056046.24     13889888.82      3055663.97     13889974.34
      3051372.98     13890492.02
#Sta/Elev= 30
  -379.3   115.3  -339.3   107.6  -289.3   106.6  1280.7   110.1  1330.7   108.6
  1380.7   100.1  1410.7   108.4  1480.7   110.2  1670.7   106.2  2010.7   109.5
  3500.4   104.7  3590.4   108.2  4350.4   107.9  4460.4    96.2  4818.3   92.88
  4872.2  105.37  4924.1  104.62  4946.1   95.54  5000.4   89.76  5080.2  104.55
  5117.5  106.92  5401.1   103.8  5801.1   107.7  6781.1   106.9  6931.1   111.5
  7021.1   107.5  7421.1     107  8661.1   114.8  8901.1     110  9513.2   114.1
#Mann= 5 ,-1 , 0
  -379.3     .99       0  4350.4     .08       0  4872.2     .04       0
  5117.5     .08       0  5801.1     .99       0
#Block Obstruct= 2 ,-1
  1280.7    1480   110.1  4385.3  4864.7  105.53
Bank Sta=4924.1,5080.2
XS Rating Curve= 0 ,0
Exp/Cntr=0.3,0.1

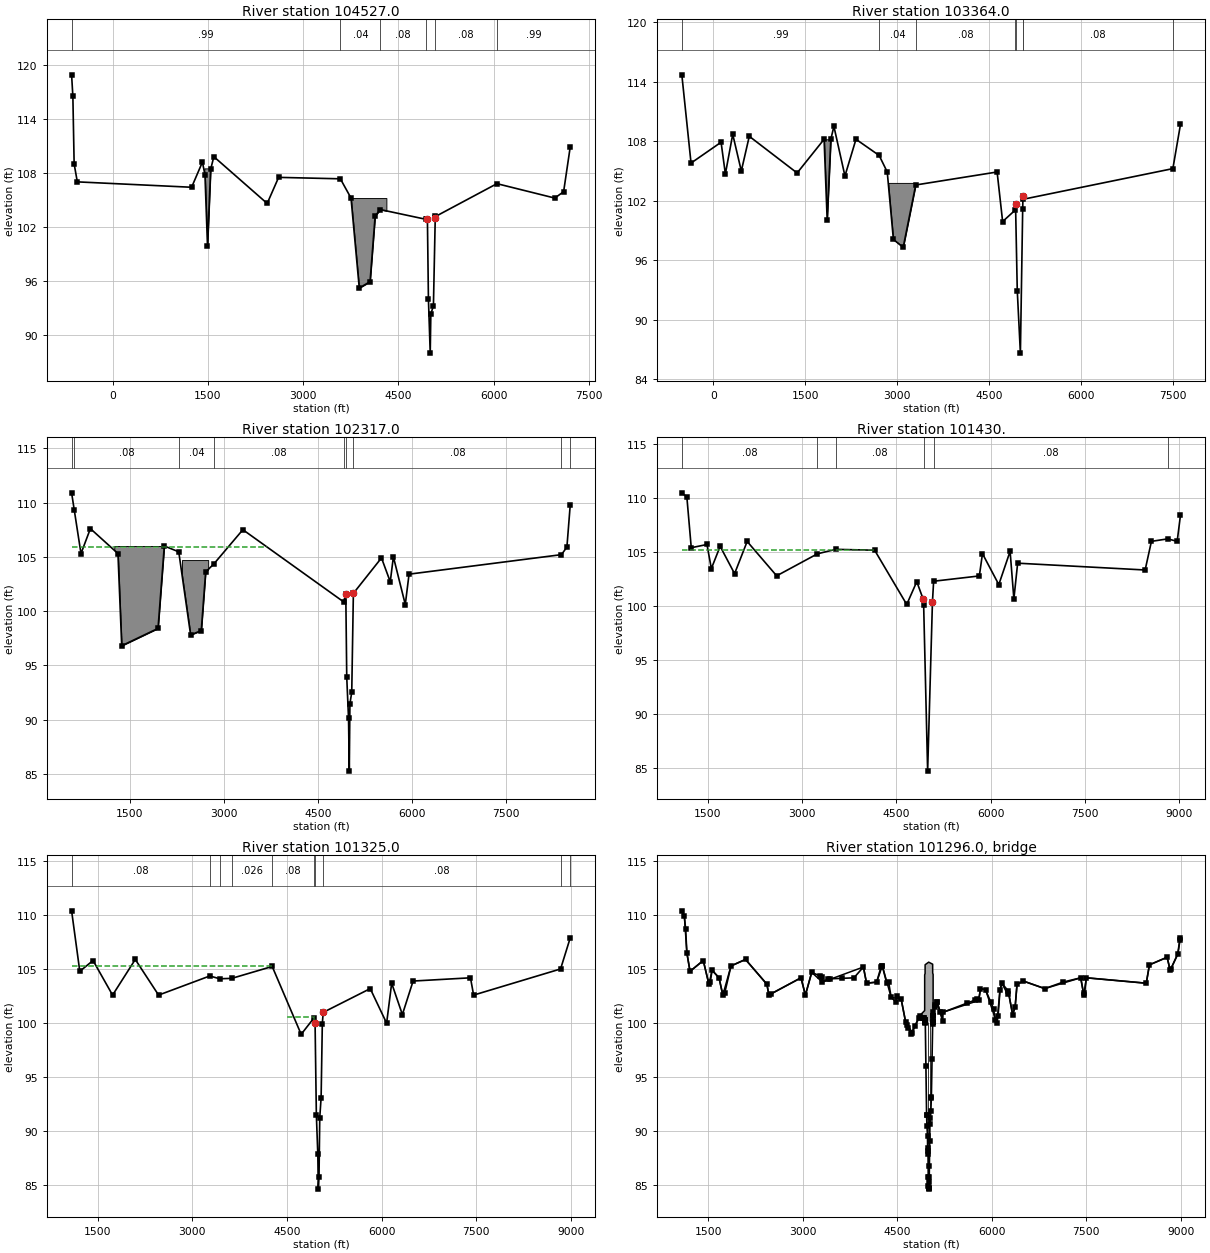
Type RM Length L Ch R = 1 ,104527.0,1164,1163,1048.3
BEGIN DESCRIPTION:
Cross Section E100-00-00-X76
END DESCRIPTION:
XS GIS Cut Line= 5
      3061261.96     13891198.26      3056726.95     13889181.48
      3056272.86     13889085.24      3055862.07     13888855.96
       3054378.5     13887583.45
#Sta/Elev= 30
  -647.1   118.9  -627.1   116.5  -607.1     109  -557.1     107  1242.9   106.4
  1412.9   109.2  1452.9   107.8  1492.9    99.9  1542.9   108.4  1592.9   109.8
  2432.9   104.6  2612.9   107.5  3585.2  107.34  3752.9   105.2  3882.9    95.2
  4052.9    95.9  4132.9   103.2  4214.4  103.92  4930.6  102.84  4956.1  102.87
    4972   93.98  5000.3   87.96  5010.1   92.33  5050.7   93.21  5079.4  103.03
  5083.1  103.15  6050.8   106.8  6960.8   105.2  7100.8   105.9  7205.3   110.9
#Mann= 6 ,-1 , 0
  -647.1     .99       0  3585.2     .04       0  4214.4     .08       0
  4930.6     .04       0  5083.1     .08       0  6050.8     .99       0
#Block Obstruct= 2 ,-1
  1442.9    1546   108.5    3698    4310   105.2
Bank Sta=4956.1,5079.4
XS Rating Curve= 0 ,0
Exp/Cntr=0.3,0.1

Type RM Length L Ch R = 1 ,103364.0,1048,1047,178.2
BEGIN DESCRIPTION:
Cross Section E100-00-00-X75
END DESCRIPTION:
XS GIS Cut Line= 5
      3061457.29     13890924.79      3057927.96     13889214.84
      3056805.65     13888465.12      3056802.28      13888040.1
      3054414.55     13887558.82
#Sta/Elev= 30
  -514.6   114.7  -364.6   105.8   125.4   107.9   195.4   104.7   315.4   108.7
   455.4     105   585.4   108.5  1365.4   104.8  1805.4   108.2  1855.4   100.1
  1915.4   108.2  1965.4   109.5  2145.4   104.5  2325.4   108.2  2703.3  106.57
  2835.4   104.9  2935.4    98.1  3095.4    97.3  3299.6  103.59  4627.1   104.9
  4717.1    99.9  4919.3  101.04  4927.2  101.72  4955.8   92.93  5006.8   86.63
  5044.2  101.16  5048.9  102.46  5052.9  102.15  7493.4  105.24  7617.6   109.7
#Mann= 8 ,-1 , 0
  -514.6     .99       0  2703.3     .04       0  3299.6     .08       0
  4919.3     .04       0  4927.2     .04       0  5044.2     .04       0
  5052.9     .08       0  7493.4    .045       0
#XS Ineff= 2 ,-1
  5048.9  7617.6  102.46  -514.6  4927.2  101.72
Permanent Ineff=
       F       F
#Block Obstruct= 2 ,-1
  1805.4  1916.5   108.2    2848    3314   103.8
Bank Sta=4927.2,5048.9
XS Rating Curve= 0 ,0
Exp/Cntr=0.3,0.1

Type RM Length L Ch R = 1 ,102317.0,1219.8,887,97.2
BEGIN DESCRIPTION:
Cross Section E100-00-00-X74
END DESCRIPTION:
XS GIS Cut Line= 5
       3061657.3     13890303.01      3059302.45     13889168.14
      3057894.29     13888358.92      3057685.53     13888031.15
      3054389.55     13887533.39
#Sta/Elev= 30
     568   110.9   610.9   109.3     718   105.3     868   107.6    1308   105.3
    1368    96.8    1948    98.4    2048     106  2278.5  105.46    2468    97.8
    2638    98.2    2708   103.6  2841.1  104.36  3302.1   107.5  4909.6  100.85
  4945.1  101.56  4960.3   93.89  4988.9    90.1  5000.8   85.24  5010.9   91.45
    5040   92.51  5066.1  101.63  5514.8   104.9  5654.8   102.7  5704.8     105
  5894.8   100.6  5954.8   103.4  8387.9   105.2  8474.8   105.9  8528.1   109.8
#Mann= 9 ,-1 , 0
     568     .05       0   610.9     .08       0  2278.5     .04       0
  2841.1     .08       0  4909.6     .04       0  4945.1     .04       0
  5066.1     .08       0  8387.9    .045       0  8528.1     .99       0
#XS Ineff= 3 ,-1
     568 3691.58   105.9  5066.1  8528.1  101.63    4000  4945.1  101.56
Permanent Ineff=
       F       F       F
#Block Obstruct= 2 ,-1
  1249.2    2048     106  2329.6    2748   104.7
Bank Sta=4945.1,5066.1
XS Rating Curve= 0 ,0
Exp/Cntr=0.3,0.1

Type RM Length L Ch R = 1 ,101430. ,78.3,105,149.7
BEGIN DESCRIPTION:
Tahoe - U\S - XS 4
END DESCRIPTION:
XS GIS Cut Line= 6
      3061664.92     13889302.76       3058598.3     13887453.78
      3058414.49     13887531.05       3058204.4     13887622.05
      3057551.99      13887944.3      3054377.65     13887518.41
#Sta/Elev= 30
  1083.3  110.46  1163.3  110.07  1233.3  105.38  1483.3  105.68  1553.3  103.45
  1693.3  105.51  1923.3  102.98  2123.3  105.96  2593.3  102.78  3243.3  104.82
  3533.3  105.23  4153.3  105.15  4664.2  100.13  4824.2  102.24  4923.6  100.66
  4933.6  100.08 4997.13   84.71  5073.6  100.36  5092.5  102.28  5820.2  102.77
  5870.2  104.83  6130.2  101.97  6310.2  105.05  6370.2  100.64  6430.2  103.95
  8460.2  103.32  8560.2  105.97  8820.2   106.2  8970.2  105.97    9023   108.4
#Mann= 6 ,-1 , 0
  1083.3     .08       0  3243.3    .026       0  3533.3     .08       0
  4933.6     .04       0  5092.5     .08       0  8820.2    .045       0
#XS Ineff= 2 , 0
         4140.97  105.17
Permanent Ineff=
       F       F
Bank Sta=4923.6,5073.6
XS Rating Curve= 0 ,0
Exp/Cntr=0.5,0.3

Type RM Length L Ch R = 1 ,101325.0,43.7,51,102.6
BEGIN DESCRIPTION:
Upstream Section of Bridge/Culvert/Weir
END DESCRIPTION:
XS GIS Cut Line= 6
      3061630.96     13889203.71      3058564.34     13887354.73
      3058380.53       13887432.      3058170.44       13887523.
      3057518.03     13887845.25      3054364.31     13887498.35
#Sta/Elev= 30
  1083.7  110.41  1213.7  104.81  1423.7  105.81  1733.7  102.61  2093.7  105.91
  2463.7  102.61  3275.7  104.38  3433.7  104.12  3625.3  104.16  4265.7  105.26
  4725.1   98.98  4924.7  100.47  4945.7  100.04  4966.1   91.52  4989.3   87.86
  4996.7   84.65  5008.1   85.74    5020   91.28  5041.6   93.12  5060.7   99.98
  5074.6  101.01  5820.6  103.21  6080.6  100.01  6160.6  103.71  6330.6  100.81
  6500.6  103.91  7410.6  104.21  7460.6  102.61    8840  105.03  8993.3  107.91
#Mann= 10 ,-1 , 0
  1083.7     .08       0  3275.7    .026       0  3433.7     .08       0
  3625.3    .026       0  4265.7     .08       0  4924.7     .04       0
  4945.7     .04       0  5074.6     .08       0    8840    .045       0
  8993.3     .99       0
#XS Ineff= 3 ,-1
  1083.7  4263.3  105.31    4500  4935.8   100.6  5070.6  8993.3   100.6
Permanent Ineff=
       F       F       F
Bank Sta=4945.7,5074.6
XS Rating Curve= 0 ,0
Exp/Cntr=0.5,0.3

Type RM Length L Ch R = 3 ,101296.0,,,
BEGIN DESCRIPTION:
TAHOE
Structure ID: E100-00-00-51
END DESCRIPTION:
Bridge Culvert--1,0,-1,-1, 0
Deck Dist Width WeirC Skew NumUp NumDn MinLoCord MaxHiCord MaxSubmerge Is_Ogee
10,38,2.6,0, 60, 60, , , 0.95, 0, ,,,
  1083.7  1123.7  1163.7  1213.7  1423.7  1513.7  1563.7  1673.7  1733.7  1863.7
  2093.7  2433.7  2463.7  2973.7  3043.7  3143.7  3313.7  3963.7  4013.7  4173.7
  4263.7  4403.7  4563.7  4633.7  4732.5  4861.3 4935.49  4935.6  4942.4  4942.5
  4999.1  5062.3  5062.7  5069.7 5069.81  5074.6  5131.1  5219.6  5222.9  5792.9
  5820.6  5900.6  6080.6  6130.6  6160.6  6260.6  6330.6  6370.6  6400.6  6500.6
  6840.6  7410.6  7460.6  7500.6  8450.6  8500.6  8780.6  8830.6  8950.6  8993.3
   110.4   109.9   106.5   104.8   105.8   103.6   104.9   104.2   102.6   105.3
   105.9   103.6   102.6   104.2   102.6   104.7   103.8   105.2   103.7   103.8
   105.3   102.4   102.2   100.1    99.2  100.72  101.17  104.47   104.6  105.41
  105.65  105.46  104.65  104.51  101.21  101.12  101.98  100.44  101.01   102.1
   103.2   103.1     100   103.1   103.7     103   100.8   101.5   103.6   103.9
   103.2   104.2   102.6   104.2   103.7   105.4   106.1   104.9   106.4   107.9
   110.4   109.9   106.5   104.8   105.8   103.6   104.9   104.2   102.6   105.3
   105.9   103.6   102.6   104.2   102.6   104.7   103.8   105.2   103.7   103.8
   105.3   102.4   102.2   100.1   99.06  100.71  100.26  100.26  100.11   100.1
  100.15  100.09  100.12  100.64  100.65     101  101.97  100.21     101   102.1
   103.2   103.1     100   103.1   103.7     103   100.8   101.5   103.6   103.9
   103.2   104.2   102.6   104.2   103.7   105.4   106.1   104.9   106.4   107.9
  1083.7  1123.7  1163.7  1213.7  1423.7  1513.7  1563.7  1673.7  1733.7  1863.7
  2093.7  2433.7  2463.7  2973.7  3043.7  3143.7  3313.7  3963.7  4013.7  4173.7
  4263.7  4403.7  4563.7  4633.7  4732.5  4861.3 4935.49  4935.6  4942.4  4942.5
  4999.1  5062.3  5062.7  5069.7 5069.81  5074.6  5131.1  5219.6  5222.9  5792.9
  5820.6  5900.6  6080.6  6130.6  6160.6  6260.6  6330.6  6370.6  6400.6  6500.6
  6840.6  7410.6  7460.6  7500.6  8450.6  8500.6  8780.6  8830.6  8950.6  8993.3
  110.46  109.96  106.56  104.86  105.86  103.66  104.96  104.26  102.66  105.36
  105.96  103.66  102.66  104.26  102.66  104.76  103.86  105.26  103.76  103.86
  105.36  102.46  102.26  100.16    99.2  100.77  101.17  104.47   104.6  105.41
  105.65  105.46  104.65  104.51  101.21  101.12  102.03  100.44  101.06  102.16
  103.26  103.16  100.06  103.16  103.76  103.06  100.86  101.56  103.66  103.96
  103.26  104.26  102.66  104.26  103.76  105.46  106.16  104.96  106.46  107.96
  110.46  109.96  106.56  104.86  105.86  103.66  104.96  104.26  102.66  105.36
  105.96  103.66  102.66  104.26  102.66  104.76  103.86  105.26  103.76  103.86
  105.36  102.46  102.26  100.16   99.12  100.77  100.32  100.32  100.17  100.16
  100.21  100.15  100.18   100.7  100.71  101.06  102.03  100.27  101.06  102.16
  103.26  103.16  100.06  103.16  103.76  103.06  100.86  101.56  103.66  103.96
  103.26  104.26  102.66  104.26  103.76  105.46  106.16  104.96  106.46  107.96
Pier Skew, UpSta & Num, DnSta & Num=  ,4982.8, 2 ,4982.8, 2 , 0 , 0 , 0 ,,
     1.3     1.3
   87.28  101.08
     1.3     1.3
   87.34  101.14
Pier Skew, UpSta & Num, DnSta & Num=  ,5022.8, 2 ,5022.8, 2 , 0 , 0 , 0 ,,
     1.3     1.3
   89.73  101.08
     1.3     1.3
   89.79  101.14
Abutment Skew #Up #Dn= , 2 , 2
  4942.5  4966.2
   100.1   91.49
  4942.5  4966.2
  100.16   91.55
Abutment Skew #Up #Dn= , 2 , 2
  5041.7 5062.39
   93.15  100.08
  5041.7 5062.39
   93.21  100.14
BR Coef= 1 , 1 , 0 ,1.25, 0 ,,,0.8,-1,2,0,
WSPro=,,,, 1 ,,,, 0 ,,,, 0 ,,,,-1 ,-1 ,-1 , 0 , 0 , 0 , 0 , 0
BR U #Sta/Elev= 131
  1083.7   110.4  1123.7   109.9  1143.7   108.7  1163.7   106.5  1213.7   104.8
  1423.7   105.8  1513.7   103.6  1533.7   103.8  1563.7   104.9  1673.7   104.2
  1733.7   102.6  1763.7   102.8  1863.7   105.3  2093.7   105.9  2433.7   103.6
  2463.7   102.6  2493.7   102.7  2973.7   104.2  3043.7   102.6  3143.7   104.7
  3275.7  104.37  3303.7   104.3  3313.7   103.8  3403.7   104.1  3433.7  104.11
  3625.3  104.15  3813.7   104.2  3963.7   105.2  4013.7   103.7  4173.7   103.8
  4243.7   105.2  4263.7   105.3  4265.7  105.25  4333.7   103.7  4363.7   103.8
  4403.7   102.4  4473.7     102  4493.7   102.5  4563.7   102.2  4633.7   100.1
  4652.5    99.8  4664.6    99.6  4725.1   98.97  4732.5   99.06  4783.7   99.72
  4846.7  100.52  4861.3  100.71  4900.5  100.46  4901.4  100.46  4924.7  100.46
    4927  100.46 4935.49  100.26  4935.6  100.26 4935.71  100.26  4942.4  100.11
  4942.5   100.1 4942.61   100.1  4942.7   100.1  4945.7  100.03  4955.6   96.02
  4966.1   91.51  4966.2   91.49  4971.7   90.52  4980.6   89.55  4982.8   88.18
  4984.3   88.42  4989.3   87.85  4991.8   85.78  4993.4   84.96  4996.7   84.64
  4999.1   84.77  4999.3   84.78  5003.3   85.34  5008.1   85.73  5010.3   86.77
  5014.3   89.13    5020   91.27  5022.8   90.66  5033.5   91.86  5041.6   93.11
  5041.7   93.15  5051.5   96.69  5060.7   99.97 5062.19  100.08  5062.3  100.09
  5062.4   100.1  5062.7  100.12 5069.59  100.63  5069.7  100.64 5069.81  100.65
  5074.6     101  5100.1  101.52  5106.6  101.65  5129.4  101.95  5131.1  101.97
  5180.2  100.99  5219.6  100.21  5222.9     101  5608.4  101.86  5726.8  102.12
  5762.9   102.2  5792.9   102.1  5820.6   103.2  5900.6   103.1  5980.6     102
  6030.6   101.3  6050.6   100.3  6080.6     100  6100.6   100.7  6130.6   103.1
  6160.6   103.7  6250.6   102.7  6260.6     103  6330.6   100.8  6370.6   101.5
  6400.6   103.6  6500.6   103.9  6840.6   103.2  7130.6   103.8  7410.6   104.2
  7460.6   102.6  7470.6   102.8  7500.6   104.2  8450.6   103.7  8500.6   105.4
  8780.6   106.1  8830.6   104.9    8840  105.02  8950.6   106.4  8980.6   107.7
  8993.3   107.9
BR U #Mann= 11
  1083.7     .99  1083.7     .08  3275.7    .026  3433.7     .08  3625.3    .026
  4265.7     .08  4924.7     .04  4945.7     .04  5074.6     .08    8840    .045
  8993.3     .99
BR U Banks=4945.7,5074.6
BR D #Sta/Elev= 131
  1083.7  110.46  1123.7  109.96  1143.7  108.76  1163.7  106.56  1213.7  104.86
  1423.7  105.86  1513.7  103.66  1533.7  103.86  1563.7  104.96  1673.7  104.26
  1733.7  102.66  1763.7  102.86  1863.7  105.36  2093.7  105.96  2433.7  103.66
  2463.7  102.66  2493.7  102.76  2973.7  104.26  3043.7  102.66  3143.7  104.76
  3275.7  104.43  3303.7  104.36  3313.7  103.86  3403.7  104.16  3433.7  104.17
  3625.3  104.21  3813.7  104.26  3963.7  105.26  4013.7  103.76  4173.7  103.86
  4243.7  105.26  4263.7  105.36  4265.7  105.31  4333.7  103.76  4363.7  103.86
  4403.7  102.46  4473.7  102.06  4493.7  102.56  4563.7  102.26  4633.7  100.16
  4652.5   99.86  4664.6   99.66  4725.1   99.03  4732.5   99.12  4783.7   99.78
  4846.7  100.58  4861.3  100.77  4900.5  100.52  4901.4  100.52  4924.7  100.52
    4927  100.52 4935.49  100.32  4935.6  100.32 4935.71  100.32  4942.4  100.17
  4942.5  100.16 4942.61  100.16  4942.7  100.16  4945.7  100.09  4955.6   96.08
  4966.1   91.57  4966.2   91.55  4971.7   90.58  4980.6   89.61  4982.8   88.24
  4984.3   88.48  4989.3   87.91  4991.8   85.84  4993.4   85.02  4996.7    84.7
  4999.1   84.83  4999.3   84.84  5003.3    85.4  5008.1   85.79  5010.3   86.83
  5014.3   89.19    5020   91.33  5022.8   90.72  5033.5   91.92  5041.6   93.17
  5041.7   93.21  5051.5   96.75  5060.7  100.03 5062.19  100.14  5062.3  100.15
  5062.4  100.16  5062.7  100.18 5069.59  100.69  5069.7   100.7 5069.81  100.71
  5074.6  101.06  5100.1  101.58  5106.6  101.71  5129.4  102.01  5131.1  102.03
  5180.2  101.05  5219.6  100.27  5222.9  101.06  5608.4  101.92  5726.8  102.18
  5762.9  102.26  5792.9  102.16  5820.6  103.26  5900.6  103.16  5980.6  102.06
  6030.6  101.36  6050.6  100.36  6080.6  100.06  6100.6  100.76  6130.6  103.16
  6160.6  103.76  6250.6  102.76  6260.6  103.06  6330.6  100.86  6370.6  101.56
  6400.6  103.66  6500.6  103.96  6840.6  103.26  7130.6  103.86  7410.6  104.26
  7460.6  102.66  7470.6  102.86  7500.6  104.26  8450.6  103.76  8500.6  105.46
  8780.6  106.16  8830.6  104.96    8840  105.08  8950.6  106.46  8980.6  107.76
  8993.3  107.96
BR D #Mann= 11
  1083.7     .99  1083.7     .08  3275.7    .026  3433.7     .08  3625.3    .026
  4265.7     .08  4924.7     .04  4945.7     .04  5074.6     .08    8840    .045
  8993.3     .99
BR D Banks=4945.7,5074.6
BC Design=,, 0 ,, 0 ,,,,,,
BC HTab HWMax=110.41
BC Use User HTab Curves=0
BC User HTab FreeFlow(D)= 0