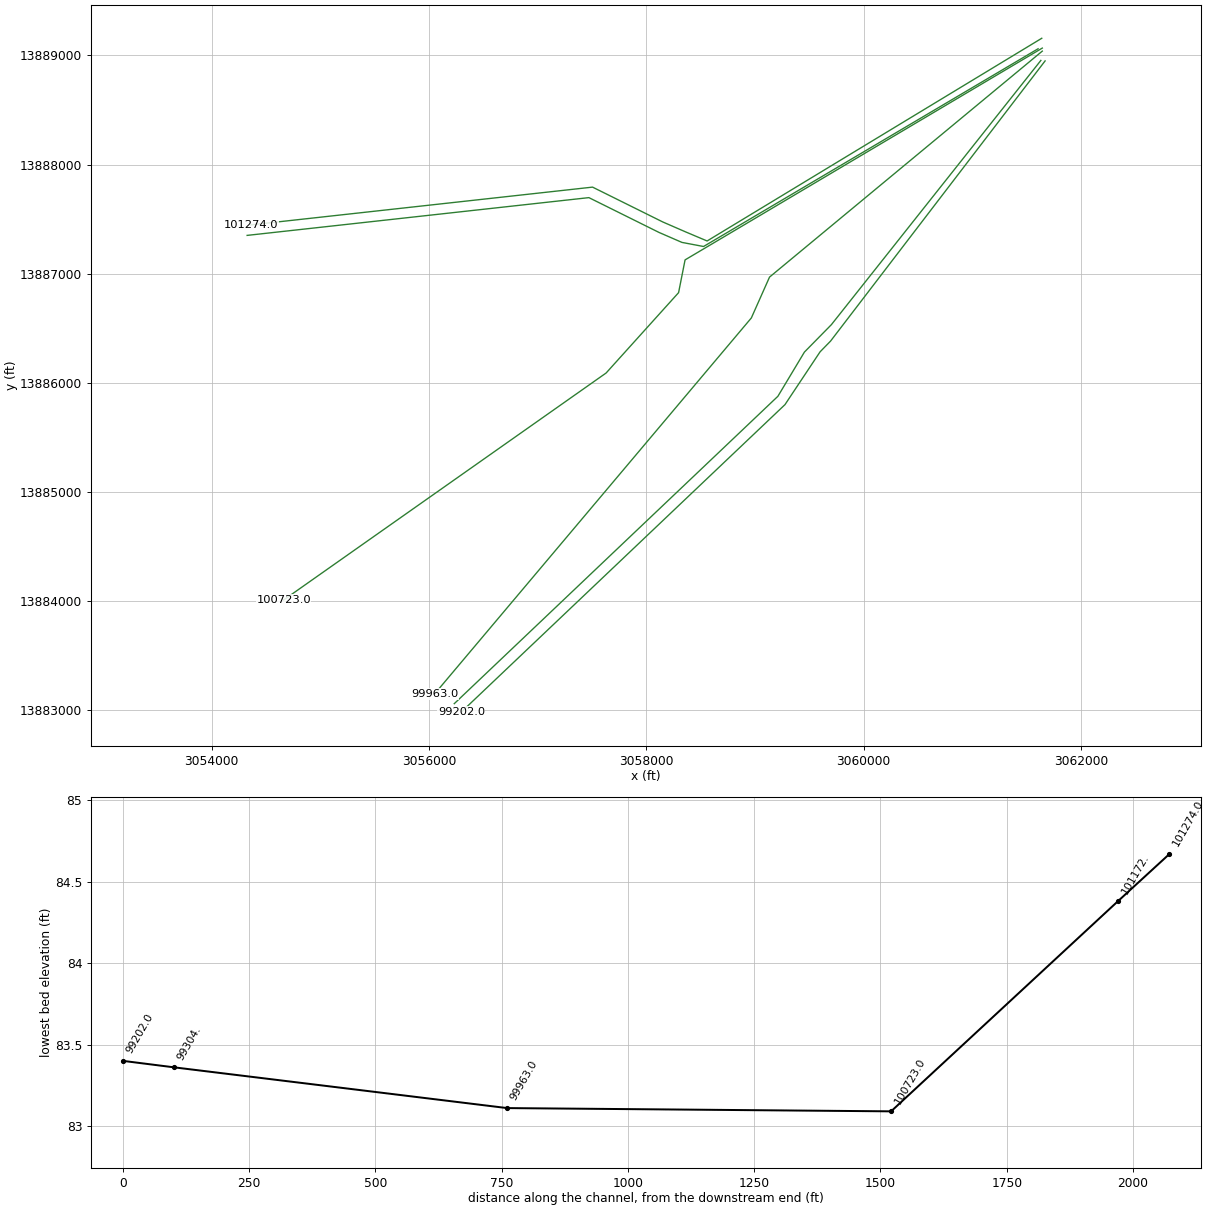
HEC-RAS study E100-00-00.prj: E100-00-00

--- E100-00-00.g02 (geometry) --- (continued)

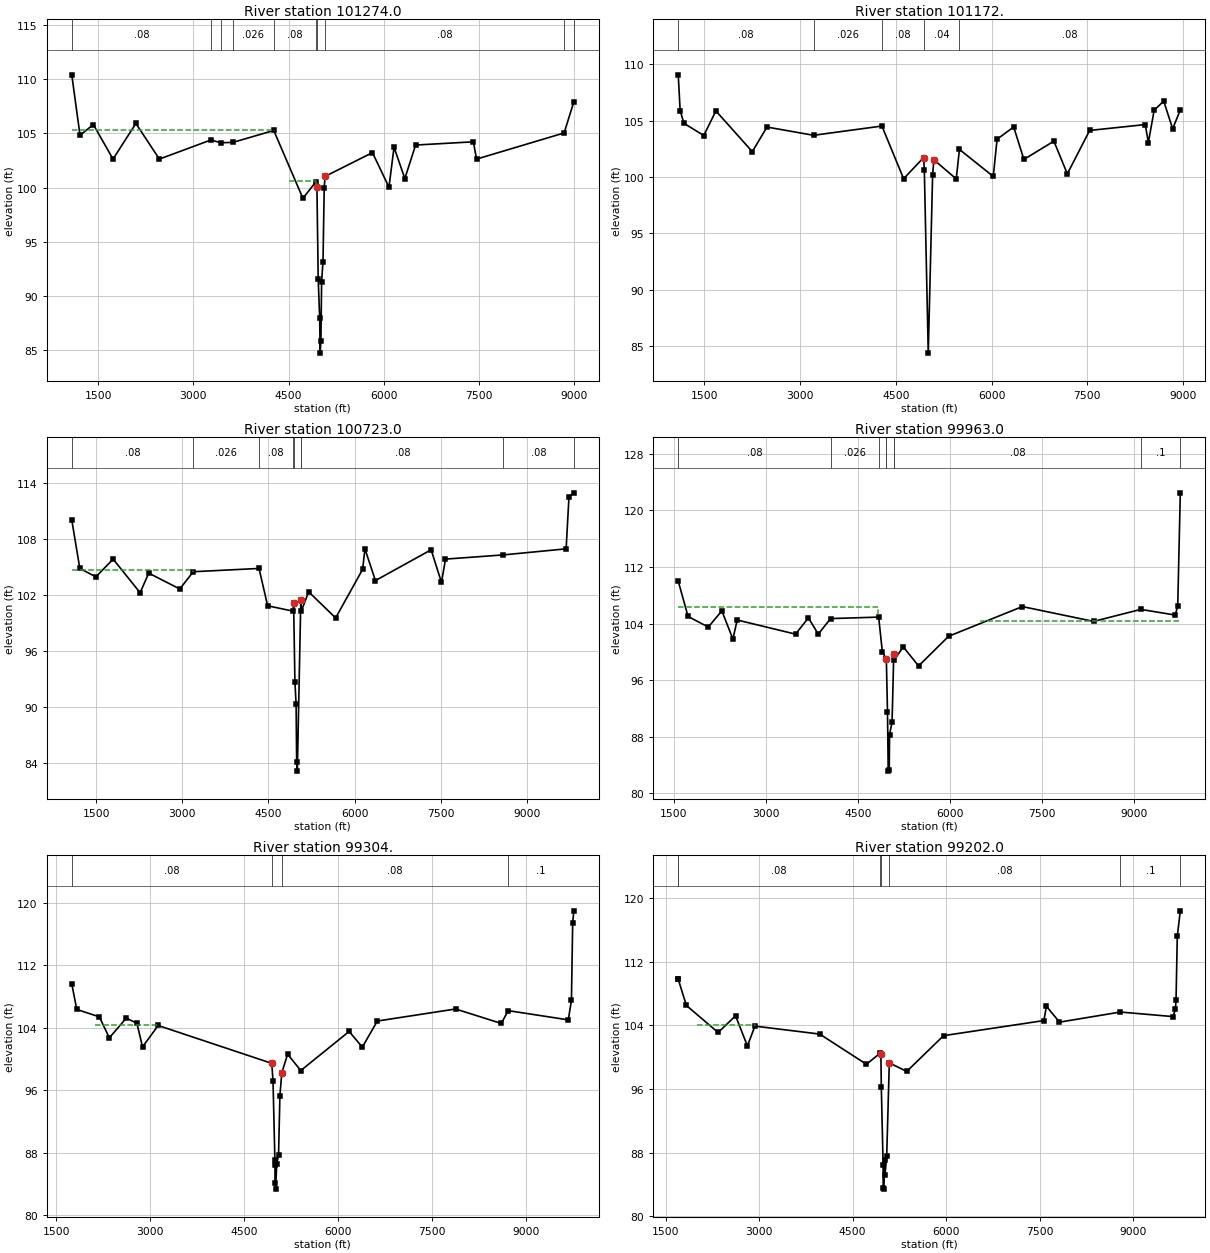
Type RM Length L Ch R = 1 ,101274.0,28.3,102,191.1
BEGIN DESCRIPTION:
Downstream Section of Bridge/Culvert/Weir
END DESCRIPTION:
XS GIS Cut Line= 6
      3061639.26     13889157.76      3058559.59      13887300.9
      3058361.57     13887384.15      3058150.64     13887475.51
      3057505.41     13887794.21      3054360.41     13887448.27
#Sta/Elev= 30
  1083.7  110.43  1213.7  104.83  1423.7  105.83  1733.7  102.63  2093.7  105.93
  2463.7  102.63  3275.7   104.4  3433.7  104.14  3625.3  104.18  4265.7  105.28
  4725.1      99  4924.7  100.49  4945.7  100.06  4966.1   91.54  4989.3   87.88
  4996.7   84.67  5008.1   85.76    5020    91.3  5041.6   93.14  5060.7     100
  5074.6  101.03  5820.6  103.23  6080.6  100.03  6160.6  103.73  6330.6  100.83
  6500.6  103.93  7410.6  104.23  7460.6  102.63    8840  105.05  8993.3  107.93
#Mann= 10 ,-1 , 0
  1083.7     .08       0  3275.7    .026       0  3433.7     .08       0
  3625.3    .026       0  4265.7     .08       0  4924.7     .04       0
  4945.7     .04       0  5074.6     .08       0    8840    .045       0
  8993.3     .99       0
#XS Ineff= 3 ,-1
  1083.7 4263.23  105.33    4500  4935.8   100.6  5070.6  8993.3   100.6
Permanent Ineff=
       F       F       F
Bank Sta=4945.7,5074.6
XS Rating Curve= 0 ,0
Exp/Cntr=0.5,0.3

Type RM Length L Ch R = 1 ,101172. ,19,449,1540.8
BEGIN DESCRIPTION:
Tahoe - D\S - XS 1
END DESCRIPTION:
XS GIS Cut Line= 6
       3061605.3     13889061.54      3058526.68     13887250.29
      3058327.61     13887287.93      3058116.68      13887379.3
      3057471.45     13887697.99      3054326.45     13887352.05
#Sta/Elev= 30
  1091.7  109.05  1121.7  105.88  1181.7  104.75  1491.7  103.67  1681.7  105.85
  2251.7  102.24  2481.7  104.42  3211.7  103.69  4281.7  104.51  4621.7   99.84
  4936.2  101.72  4946.2  100.63  5007.7   84.38  5076.2  100.18  5096.1  101.52
  5446.1   99.82  5496.1  102.44  6025.7  100.04  6085.7  103.34  6345.7  104.43
  6505.7  101.55  6975.7  103.17  7185.7  100.27  7535.7  104.12  8405.7  104.64
  8455.7  103.05  8545.7  105.91  8695.7  106.72  8835.7  104.27  8955.7  105.93
#Mann= 5 ,-1 , 0
  1091.7     .08       0  3211.7    .026       0  4281.7     .08       0
  4946.2     .04       0  5496.1     .08       0
#XS Ineff= 2 , 0
       0    4278   104.5               0
Permanent Ineff=
       F       F
Bank Sta=4936.2,5096.1
XS Rating Curve= 0 ,0
Exp/Cntr=0.3,0.1

Type RM Length L Ch R = 1 ,100723.0,593.2,760,761
BEGIN DESCRIPTION:
Cross Section E100-00-00-X73
END DESCRIPTION:
XS GIS Cut Line= 5
      3061644.17     13889067.87      3058356.74     13887127.71
      3058296.99     13886827.38      3057630.35      13886091.7
      3054662.01     13884011.97
#Sta/Elev= 30
  1075.3     110  1215.3   104.8  1495.3   103.9  1795.3   105.8  2265.3   102.2
  2415.3   104.3  2955.3   102.6  3190.6  104.45    4335   104.8  4485.3   100.8
    4933  100.22  4937.3  101.08  4960.1   92.66  4980.6   90.26  4990.4   84.04
  5002.1   83.09  5062.5  101.37  5074.3  100.26  5198.8   102.3  5668.8    99.5
  6138.8   104.7  6178.8   106.9  6361.6   103.5  7331.6   106.8  7511.6   103.3
  7581.6   105.8  8586.7  106.25  9681.6   106.9  9731.6   112.5    9816   112.9
#Mann= 9 ,-1 , 0
  1075.3     .08       0  3190.6    .026       0    4335     .08       0
    4933     .04       0  4937.3     .04       0  5062.5     .04       0
  5074.3     .08       0  8586.7     .08       0    9816     .99       0
#XS Ineff= 2 , 0
       0  3185.3   104.6  6178.8       0   106.9
Permanent Ineff=
       F       F
Bank Sta=4937.3,5062.5
XS Rating Curve= 0 ,0
Exp/Cntr=0.3,0.1

Type RM Length L Ch R = 1 ,99963.0 ,717.3,659,624.1
BEGIN DESCRIPTION:
Cross Section E100-00-00-X72
END DESCRIPTION:
XS GIS Cut Line= 4
      3061644.17     13889040.07      3059133.93     13886969.94
      3058966.66     13886595.85      3056051.65     13883151.72
#Sta/Elev= 30
    1573     110    1733     105    2063   103.5    2283   105.8    2463   101.8
    2533   104.5    3483   102.5    3693   104.8    3853   102.5  4053.6   104.7
  4836.6  104.91  4896.2  100.04  4959.3   98.95  4961.7   98.95  4980.4   91.53
  4992.1   83.11  5008.7   83.31  5014.1   88.29    5055   90.05  5082.7   99.75
  5089.1   98.82  5236.5   100.7  5486.5      98  5976.5   102.2  7176.5   106.4
  8336.5   104.3  9104.6     106  9666.5   105.2  9706.5   106.5  9748.6   122.5
#Mann= 9 ,-1 , 0
    1573     .08       0  4053.6    .026       0  4836.6     .08       0
  4959.3     .04       0  4961.7     .04       0  5082.7     .04       0
  5089.1     .08       0  9104.6      .1       0  9748.6     .99       0
#XS Ineff= 2 , 0
       0    4823   106.3  6496.5       0   104.4
Permanent Ineff=
       F       F
Bank Sta=4961.7,5082.7
XS Rating Curve= 0 ,0
Exp/Cntr=0.3,0.1

Type RM Length L Ch R = 1 ,99304.  ,92.1,102,108.1
BEGIN DESCRIPTION:
Lakeview - U\S - XS 4
END DESCRIPTION:
XS GIS Cut Line= 5
        3061631.     13888954.78       3059703.3     13886534.47
      3059455.05     13886283.18      3059211.02     13885878.26
      3056232.75     13883062.58
#Sta/Elev= 30
    1744   109.6    1824  106.33    2184  105.39    2344   102.7    2614  105.22
    2784  104.57    2874  101.54    3124  104.28  4938.2   99.44  4958.2   97.15
  4988.2   87.03  4989.5   86.43 4989.88   84.19 4999.98   83.36 5016.94   86.58
 5046.26   87.66  5068.2   95.32  5098.2   98.23  5191.4  100.61  5401.4   98.52
  6174.2  103.52  6384.2  101.51  6624.2  104.85  7874.2  106.39  8604.2  104.54
  8714.2  106.18  9674.2     105  9724.2   107.5  9744.2  117.44  9762.7  118.94
#Mann= 4 ,-1 , 0
    1744     .08       0  4938.2     .04       0  5098.2     .08       0
  8714.2      .1       0
#XS Ineff= 1 ,-1
 2115.23 3122.21  104.28
Permanent Ineff=
       F
Bank Sta=4938.2,5098.2
XS Rating Curve= 0 ,0
Exp/Cntr=0.5,0.3

Type RM Length L Ch R = 1 ,99202.0 ,51.9,48,47
BEGIN DESCRIPTION:
Upstream Section of Bridge/Culvert/Weir
END DESCRIPTION:
XS GIS Cut Line= 5
      3061669.92     13888950.31      3059695.69     13886383.88
      3059599.08     13886285.37      3059276.11     13885801.85
      3056297.84     13882986.17
#Sta/Elev= 30
  1702.5   109.8  1702.6   109.8  1832.6   106.5  2342.6   103.1  2622.6   105.2
  2812.6   101.4  2932.6   103.9  3972.6   102.9  4722.6    99.1  4943.8  100.51
  4954.2  100.39    4961   96.23  4989.8   86.47  4990.6   83.53  5001.2    83.4
  5018.1   87.03  5019.9   85.19  5047.3   87.53  5089.3   99.28  5368.5    98.2
    5960   102.7    7570   104.6    7610   106.4    7820   104.4  8797.2  105.67
    9640   105.1    9680     106    9690   107.2    9710   115.2  9758.5   118.4
#Mann= 7 ,-1 , 0
  1702.5     .99       0  1702.6     .08       0  4943.8     .04       0
  4954.2     .04       0  5089.3     .08       0  8797.2      .1       0
  9758.5     .99       0
#XS Ineff= 3 ,-1
    2000    2940   104.1  5089.7    8000    98.8    4000  4949.8    98.8
Permanent Ineff=
       F       F       F
Bank Sta=4954.2,5089.3
XS Rating Curve= 0 ,0
Exp/Cntr=0.5,0.3