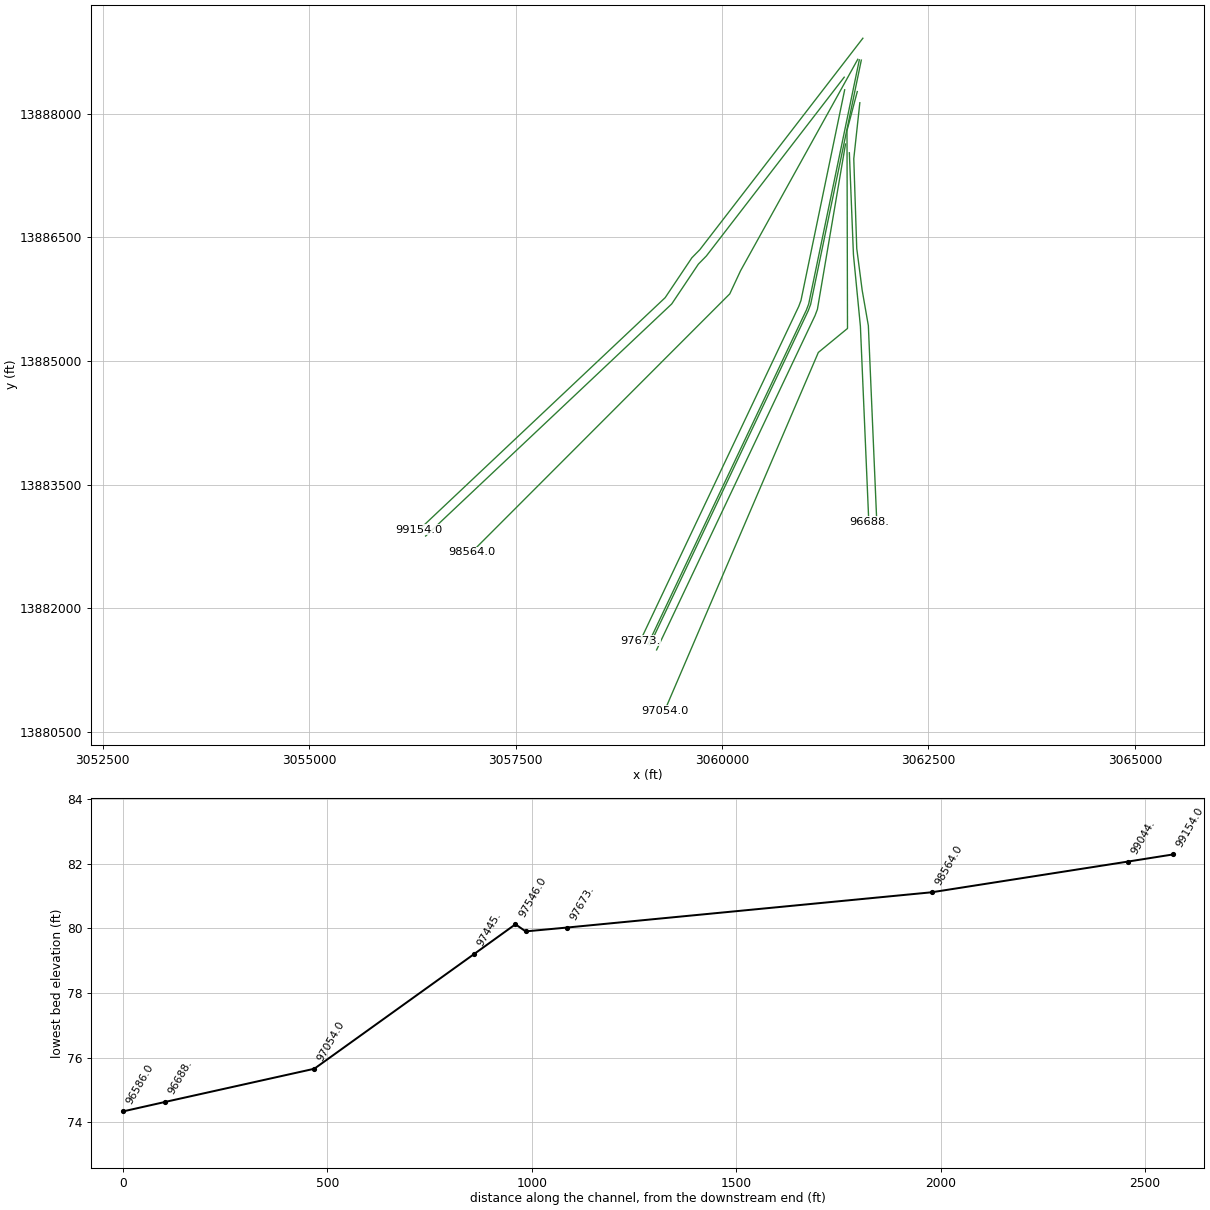
HEC-RAS study E100-00-00.prj: E100-00-00

--- E100-00-00.g02 (geometry) --- (continued)

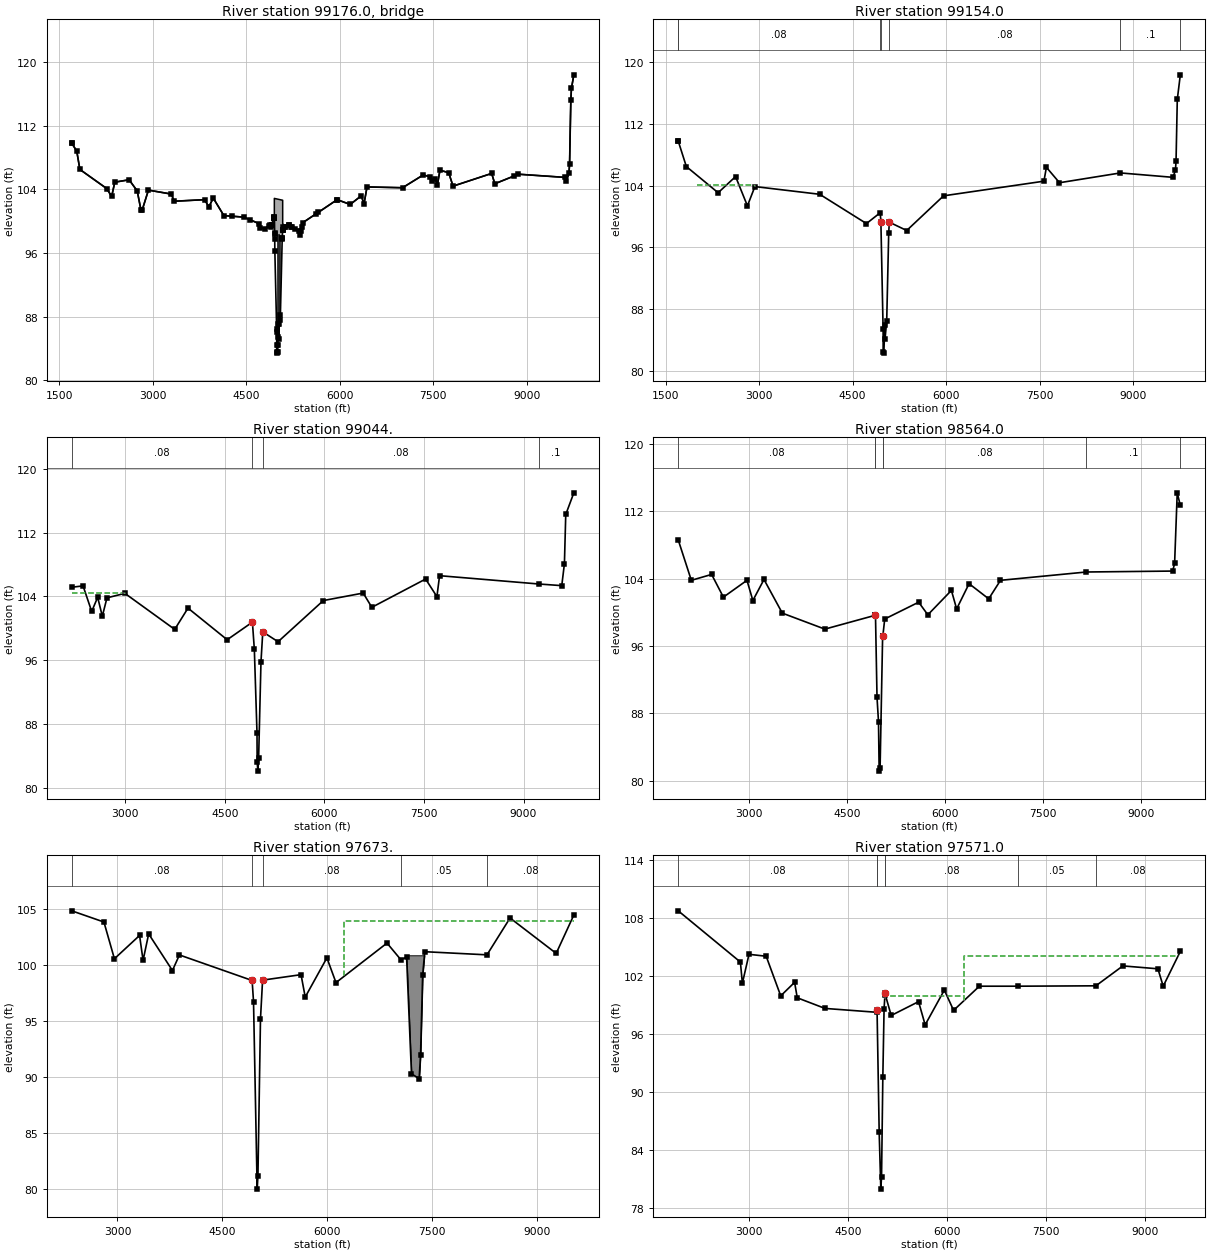
Type RM Length L Ch R = 3 ,99176.0 ,,,
BEGIN DESCRIPTION:
LAKEVIEW
Structure ID: E100-00-00-50
END DESCRIPTION:
Bridge Culvert--1,0,-1,-1, 0
Deck Dist Width WeirC Skew NumUp NumDn MinLoCord MaxHiCord MaxSubmerge Is_Ogee
10,32,2.6,0, 60, 60, , , 0.95, 0, ,,,
  1702.5  1782.6  1832.6  2262.6  2342.6  2392.6  2622.6  2752.6  2812.6  2832.6
  2932.6  3302.6  3342.6  3832.6  3902.6  3972.6  4142.6  4462.6  4702.6  4722.6
  4809.4  4901.2 4952.69  4952.8  4954.2  4957.7 5079.69  5079.8  5086.7 5086.81
  5116.4    5182  5348.5  5368.5  5388.5  5408.5    5960    6170    6350    6390
    6440    7010    7340    7450    7490    7530    7570    7610    7750    7820
    8440    8490    8870    9620    9640    9680    9690    9710    9720  9758.5
   109.8   108.8   106.5   104.1   103.1   104.9   105.2   103.8   101.4   101.4
   103.9   103.4   102.5   102.7   101.8   102.9   100.7  100.51   99.71   99.11
   99.15   99.46  100.42  102.86  102.86  102.85  102.64  102.64  102.63   99.73
   99.21   99.56   98.81   98.73   98.71   99.81   102.7   102.1   103.2   102.1
   104.3   104.2   105.8   105.6     105   105.3   104.6   106.4   106.1   104.4
     106   104.7   105.9   105.5   105.1     106   107.2   115.2   116.7   118.4
   109.8   108.8   106.5   104.1   103.1   104.9   105.2   103.8   101.4   101.4
   103.9   103.4   102.5   102.7   101.8   102.9   100.7   100.5    99.7    99.1
   99.04   99.28  100.41  100.41  100.39   98.45   98.24   97.89    98.9   98.91
    99.2   99.55    98.8    98.2    98.7    99.8   102.7   102.1   103.2   102.1
   104.3   104.2   105.8   105.6     105   105.3   104.6   106.4   106.1   104.4
     106   104.7   105.9   105.5   105.1     106   107.2   115.2   116.7   118.4
  1702.5  1782.6  1832.6  2262.6  2342.6  2392.6  2622.6  2752.6  2812.6  2832.6
  2932.6  3302.6  3342.6  3832.6  3902.6  3972.6  4142.6  4462.6  4702.6  4722.6
  4809.4  4901.2 4952.69  4952.8 4952.91  4954.2 5079.69  5079.8  5086.7 5086.81
  5116.4    5182  5348.5  5368.5  5388.5  5408.5    5960    6170    6350    6390
    6440    7010    7340    7450    7490    7530    7570    7610    7750    7820
    8440    8490    8870    9620    9640    9680    9690    9710    9720  9758.5
   109.8   108.8   106.5   104.1   103.1   104.9   105.2   103.8   101.4   101.4
   103.9   103.4   102.5   102.7   101.8   102.9   100.7  100.51   99.71   99.11
   99.15   99.46  100.42  102.86  102.86  102.86  102.64  102.64  102.63   99.73
   99.21   99.56   98.81   98.73   98.71   99.81   102.7   102.1   103.2   102.1
   104.3   104.2   105.8   105.6     105   105.3   104.6   106.4   106.1   104.4
     106   104.7   105.9   105.5   105.1     106   107.2   115.2   116.7   118.4
   109.8   108.8   106.5   104.1   103.1   104.9   105.2   103.8   101.4   101.4
   103.9   103.4   102.5   102.7   101.8   102.9   100.7   100.5    99.7    99.1
   99.04   99.28  100.41  100.41   98.45   98.45   98.24   97.89    98.9   98.91
    99.2   99.55    98.8    98.2    98.7    99.8   102.7   102.1   103.2   102.1
   104.3   104.2   105.8   105.6     105   105.3   104.6   106.4   106.1   104.4
     106   104.7   105.9   105.5   105.1     106   107.2   115.2   116.7   118.4
Pier Skew, UpSta & Num, DnSta & Num=  ,4989.8, 2 ,4989.8, 2 , 0 , 0 , 0 ,,
       2       2
   82.53    99.4
       2       2
   81.44    99.4
Pier Skew, UpSta & Num, DnSta & Num=  ,5019.9, 2 ,5019.9, 2 , 0 , 0 , 0 ,,
       2       2
   84.34   99.35
       2       2
   83.25   99.35
Pier Skew, UpSta & Num, DnSta & Num=  ,5050, 2 ,5050, 2 , 0 , 0 , 0 ,,
       2       2
   86.98   99.29
       2       2
   85.89   99.29
BR Coef= 1 , 1 , 0 ,1.25, 0 ,,,0.8,-1,2,0,
WSPro=,,,, 1 ,,,, 0 ,,,, 0 ,,,,-1 ,-1 ,-1 , 0 , 0 , 0 , 0 , 0
BR U #Sta/Elev= 99
  1702.5   109.8  1702.6   109.8  1782.6   108.8  1832.6   106.5  2262.6   104.1
  2342.6   103.1  2392.6   104.9  2622.6   105.2  2752.6   103.8  2812.6   101.4
  2832.6   101.4  2932.6   103.9  3302.6   103.4  3342.6   102.5  3832.6   102.7
  3902.6   101.8  3972.6   102.9  4142.6   100.7  4267.1  100.62  4462.6   100.5
  4567.6  100.15  4702.6    99.7  4722.6    99.1  4809.4   99.04  4861.4   99.38
  4884.3   99.53  4901.2   99.28  4913.7   99.54  4915.1   99.57  4942.8  100.52
  4943.8  100.51 4952.69  100.41  4952.8  100.41 4952.91   100.4  4954.2  100.39
 4957.61   98.47  4957.7   98.42  4958.9   97.75    4961   96.23  4989.8   86.47
  4990.2    86.1  4990.4    84.4  4990.6   83.53  5001.2    83.4  5007.7   83.56
  5009.5    84.4  5013.5   85.38  5018.1   87.03  5019.9   85.19  5032.6   87.09
  5047.3   87.53    5050   88.25  5078.6   97.71 5079.69   97.87  5079.8   97.89
 5086.59   98.88  5086.7    98.9 5086.81   98.91  5089.3   99.28  5116.4    99.2
    5131   99.28    5182   99.55    5185   99.53  5216.8   99.32  5234.4   99.21
  5279.1   99.05  5348.5    98.8  5368.5    98.2  5388.5    98.7  5399.1   99.28
  5408.5    99.8  5628.1  100.94    5660   101.1  5955.3  102.67    5960   102.7
    6170   102.1    6350   103.2    6390   102.1    6440   104.3    7010   104.2
    7340   105.8    7450   105.6    7490     105    7530   105.3    7570   104.6
    7610   106.4    7750   106.1    7820   104.4    8440     106    8490   104.7
  8797.2  105.67    8870   105.9    9620   105.5    9640   105.1    9680     106
    9690   107.2    9710   115.2    9720   116.7  9758.5   118.4
BR U #Mann= 7
  1702.5     .99  1702.6     .08  4943.8     .04  4954.2     .04  5089.3     .08
  8797.2      .1  9758.5     .99
BR U Banks=4954.2,5089.3
BR D #Sta/Elev= 99
  1702.5   109.8  1702.6   109.8  1782.6   108.8  1832.6   106.5  2262.6   104.1
  2342.6   103.1  2392.6   104.9  2622.6   105.2  2752.6   103.8  2812.6   101.4
  2832.6   101.4  2932.6   103.9  3302.6   103.4  3342.6   102.5  3832.6   102.7
  3902.6   101.8  3972.6   102.9  4142.6   100.7  4267.1  100.62  4462.6   100.5
  4567.6  100.15  4702.6    99.7  4722.6    99.1  4809.4   99.04  4861.4   99.38
  4884.3   99.53  4901.2   99.28  4913.7   99.54  4915.1   99.57  4942.8  100.52
  4943.8  100.51 4952.69  100.41  4952.8  100.41 4952.91   100.4  4954.2    99.3
 4957.61   97.38  4957.7   97.33  4958.9   96.66    4961   95.14  4989.8   85.38
  4990.2   85.01  4990.4   83.31  4990.6   82.44  5001.2   82.31  5007.7   82.47
  5009.5   83.31  5013.5   84.29  5018.1   85.94  5019.9    84.1  5032.6      86
  5047.3   86.44    5050   87.16  5078.6   96.62 5079.69   97.87  5079.8   97.89
 5086.59   98.88  5086.7    98.9 5086.81   98.91  5089.3   99.28  5116.4    99.2
    5131   99.28    5182   99.55    5185   99.53  5216.8   99.32  5234.4   99.21
  5279.1   99.05  5348.5    98.8  5368.5    98.2  5388.5    98.7  5399.1   99.28
  5408.5    99.8  5628.1  100.94    5660   101.1  5955.3  102.67    5960   102.7
    6170   102.1    6350   103.2    6390   102.1    6440   104.3    7010   104.2
    7340   105.8    7450   105.6    7490     105    7530   105.3    7570   104.6
    7610   106.4    7750   106.1    7820   104.4    8440     106    8490   104.7
  8797.2  105.67    8870   105.9    9620   105.5    9640   105.1    9680     106
    9690   107.2    9710   115.2    9720   116.7  9758.5   118.4
BR D #Mann= 6
  1702.5     .99  1702.6     .08  4943.8     .04  4954.2     .04  5089.3     .08
  8797.2      .1
BR D Banks=4954.2,5089.3
BC Design=,, 0 ,, 0 ,,,,,,
BC HTab HWMax=118.4
BC Use User HTab Curves=0
BC User HTab FreeFlow(D)= 0

Type RM Length L Ch R = 1 ,99154.0 ,118.6,110,108.3
BEGIN DESCRIPTION:
Downstream Section of Bridge/Culvert/Weir
END DESCRIPTION:
XS GIS Cut Line= 5
      3061706.03     13888918.71       3059730.7     13886350.84
      3059634.79     13886253.06       3059311.5     13885769.06
      3056330.78     13882951.05
#Sta/Elev= 30
  1702.5   109.8  1702.6   109.8  1832.6   106.5  2342.6   103.1  2622.6   105.2
  2812.6   101.4  2932.6   103.9  3972.6   102.9  4722.6    99.1  4943.8  100.51
  4954.2   99.28  4989.8   85.36  4990.6   82.42  5001.2   82.29  5018.1   85.92
  5019.9   84.08  5047.3   86.42 5079.69   97.87  5089.3   99.28  5368.5    98.2
    5960   102.7    7570   104.6    7610   106.4    7820   104.4  8797.2  105.67
    9640   105.1    9680     106    9690   107.2    9710   115.2  9758.5   118.4
#Mann= 7 ,-1 , 0
  1702.5     .99       0  1702.6     .08       0  4943.8     .04       0
  4954.2     .04       0  5089.3     .08       0  8797.2      .1       0
  9758.5     .99       0
#XS Ineff= 3 ,-1
    2000    2940   104.1  5089.7    8000    98.8    4000  4949.8    98.8
Permanent Ineff=
       F       F       F
Bank Sta=4954.2,5089.3
XS Rating Curve= 0 ,0
Exp/Cntr=0.5,0.3

Type RM Length L Ch R = 1 ,99044.  ,414.1,480,473.1
BEGIN DESCRIPTION:
Lakeview - D\S - XS 1
END DESCRIPTION:
XS GIS Cut Line= 5
      3061480.08     13888445.56      3059809.94     13886274.44
      3059714.03     13886176.65      3059390.74     13885692.65
      3056410.02     13882874.65
#Sta/Elev= 30
  2197.4  105.15  2367.4  105.32  2497.4  102.11  2587.4  103.89  2657.4  101.51
  2727.4  103.82  2997.4  104.38  3747.4   99.86  3947.4  102.53  4537.4   98.56
  4917.4  100.77  4946.6   97.34  4986.6   86.85 4988.71   83.27 4999.69   82.07
 5011.08   83.72  5046.6   95.81  5073.6   99.55  5303.6   98.31  5985.6  103.48
  6585.6  104.42  6715.6  102.63  7525.6  106.18  7695.6  103.97  7735.6   106.6
  9225.6  105.56  9575.6  105.35  9615.6  108.11  9635.6  114.28  9757.5     117
#Mann= 4 ,-1 , 0
  2197.4     .08       0  4917.4     .04       0  5073.6     .08       0
  9225.6      .1       0
#XS Ineff= 2 , 0
       0    3000  104.38               0
Permanent Ineff=
       F       F
Bank Sta=4917.4,5073.6
XS Rating Curve= 0 ,0
Exp/Cntr=0.3,0.1

Type RM Length L Ch R = 1 ,98564.0 ,720.8,891,906.7
BEGIN DESCRIPTION:
Cross Section E100-00-00-X71
END DESCRIPTION:
XS GIS Cut Line= 4
      3061644.17     13888662.78      3060224.07     13886094.76
      3060093.81     13885814.94      3056968.62     13882679.06
#Sta/Elev= 30
  1923.5   108.6  2123.5   103.8  2433.5   104.5  2613.5   101.8  2973.5   103.8
  3063.5   101.4  3233.5   103.9  3513.5    99.9  4163.5      98  4935.9   99.65
    4937   99.64  4960.3   89.89    4983   86.99  4993.1   81.12  5007.3   81.51
  5046.2   97.21  5049.4   97.18    5078    99.2  5596.7   101.2  5736.7    99.7
  6096.7   102.6  6176.7   100.4  6366.7   103.4  6666.7   101.6  6846.7   103.8
  8160.1  104.79  9476.7   104.9  9506.7   105.8  9546.7   114.2  9593.9   112.7
#Mann= 7 ,-1 , 0
  1923.5     .08       0  4935.9     .04       0    4937     .04       0
  5046.2     .04       0  5049.4     .08       0  8160.1      .1       0
  9593.9     .99       0
#XS Ineff= 2 , 0
       0  3233.5   103.9  6096.7       0   102.6
Permanent Ineff=
       F       F
Bank Sta=4937,5046.2
XS Rating Curve= 0 ,0
Exp/Cntr=0.3,0.1

Type RM Length L Ch R = 1 ,97673.  ,111.7,102,101
BEGIN DESCRIPTION:
Equador Drive - U\S - XS 4
END DESCRIPTION:
XS GIS Cut Line= 4
      3061485.71     13888292.58      3060956.39     13885735.09
      3060928.93     13885662.02      3059010.23     13881603.98
#Sta/Elev= 30
  2345.9  104.88  2805.9  103.88  2955.9   100.6  3315.9  102.68  3365.9  100.45
  3445.9  102.82  3785.9   99.55  3885.9  100.94  4925.9   98.66  4945.9   96.78
 4998.21   80.03 5009.01    81.2  5045.6   95.25  5075.6   98.69  5625.6   99.18
  5685.6   97.18  5995.6  100.68  6125.6   98.47  6855.6     102  7055.6   100.5
  7135.6  100.76  7205.6   90.33  7315.6   89.89  7335.6   92.04  7365.6   99.13
  7395.6  101.23  8285.6  100.95  8615.6  104.24  9275.6  101.08  9528.3  104.51
#Mann= 5 ,-1 , 0
  2345.9     .08       0  4925.9     .04       0  5075.6     .08       0
  7055.6     .05       0  8285.6     .08       0
#XS Ineff= 2 , 0
       0                    6240       0     104
Permanent Ineff=
       F       F
#Block Obstruct= 1 ,-1
 7131.28 7434.36  100.91
Bank Sta=4925.9,5075.6
XS Rating Curve= 0 ,0
Exp/Cntr=0.5,0.3

Type RM Length L Ch R = 1 ,97571.0 ,27,25,24.2
BEGIN DESCRIPTION:
Upstream Section of Bridge/Culvert/Weir
END DESCRIPTION:
XS GIS Cut Line= 4
      3061663.13     13888656.16      3061049.78     13885692.64
      3061022.32     13885619.57      3059103.61     13881561.53
#Sta/Elev= 30
  1935.1  108.71  2875.1  103.41  2905.1  101.21  3005.1  104.21  3265.1  104.01
  3485.1   99.91  3695.1  101.31  3735.1   99.71  4155.1   98.61  4936.5   98.21
    4942   98.42  4974.2   85.78  4998.8   79.91  5009.8   81.18  5029.2   91.47
  5048.2    98.6  5063.4  100.22  5068.9   99.97  5155.9   97.88  5569.5   99.31
  5669.5   96.91  5959.5  100.51  6099.5   98.41  6489.5  100.91  7071.1  100.91
  8251.3  100.95  8659.5  103.01  9189.5  102.71  9269.5  100.91  9528.3  104.51
#Mann= 7 ,-1 , 0
  1935.1     .08       0  4936.5     .04       0    4942     .04       0
  5063.4     .04       0  5068.9     .08       0  7071.1     .05       0
  8251.3     .08       0
#XS Ineff= 3 ,-1
    6250    9515     104  5057.9    6250    99.9    2500  4936.2    97.8
Permanent Ineff=
       F       F       F
Bank Sta=4942,5063.4
XS Rating Curve= 0 ,0
Exp/Cntr=0.5,0.3

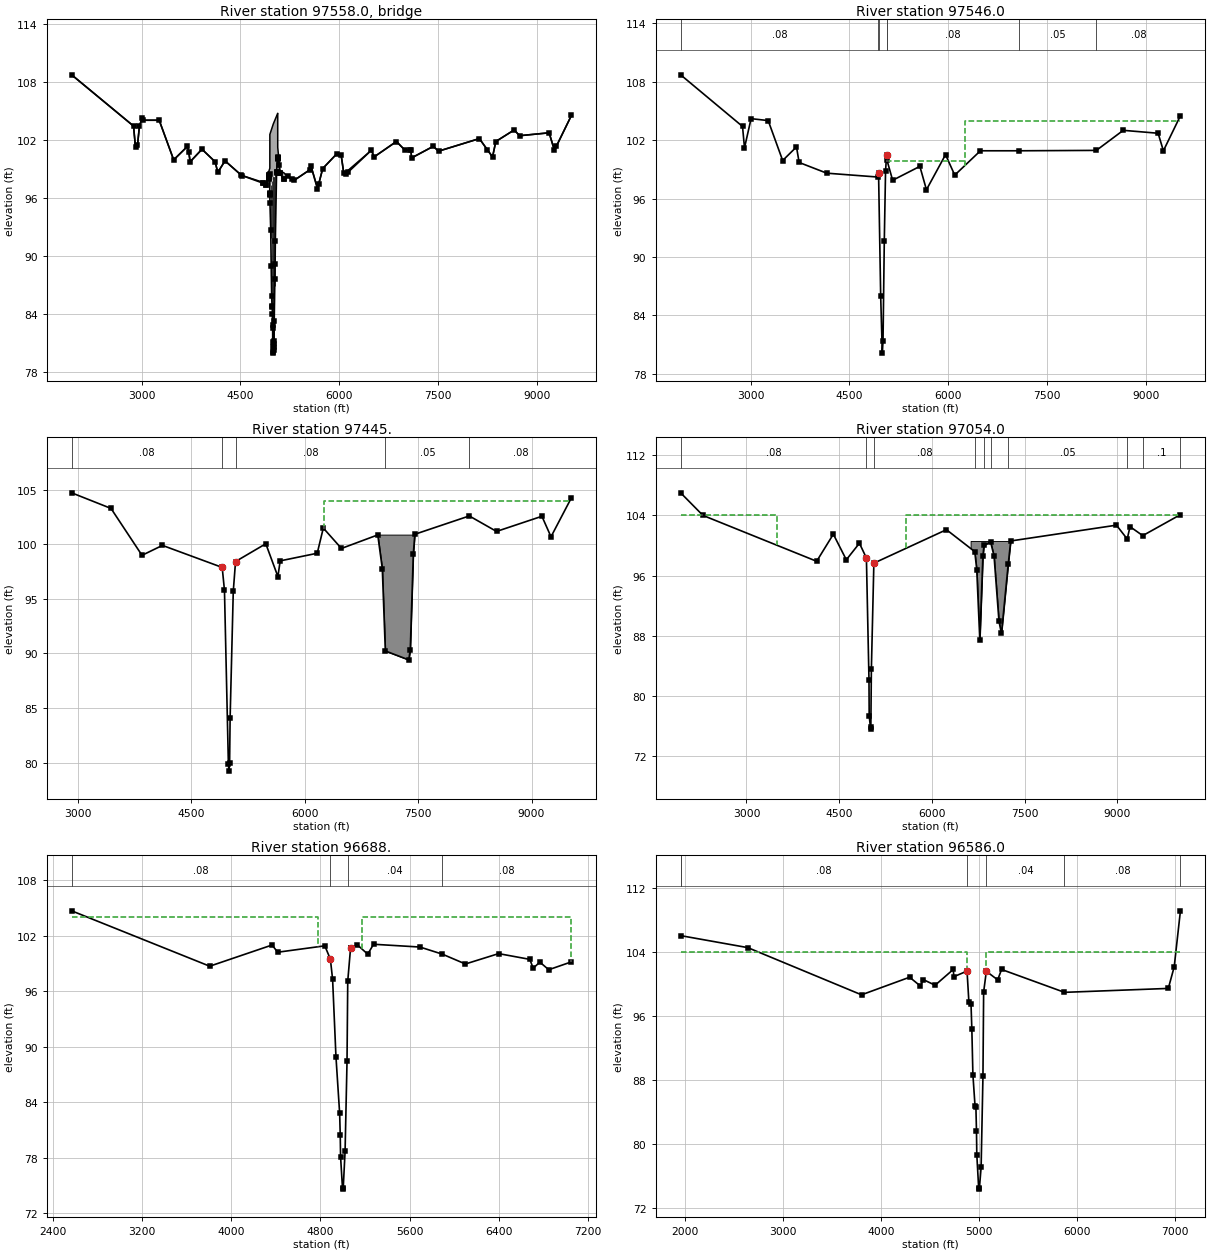
Type RM Length L Ch R = 3 ,97558.0 ,,,
BEGIN DESCRIPTION:
EQUADOR DRIVE
Structure ID: E100-00-00-49
END DESCRIPTION:
Bridge Culvert--1,0,-1,-1, 0
Deck Dist Width WeirC Skew NumUp NumDn MinLoCord MaxHiCord MaxSubmerge Is_Ogee
10,6,2.6,0, 60, 60, , , 0.95, 0, ,,,
  1935.1  2875.1  2905.1  2935.1  2965.1  3005.1  3025.1  3265.1  3485.1  3695.1
  3715.1  3735.1  3915.1  4115.1  4155.1  4265.1  4515.1  4846.5    4890  4928.8
    4942 4946.19  4946.3  4998.8 5048.96 5049.07  5063.4  5065.8    5066 5066.11
  5101.5  5155.9  5214.5  5319.5  5559.5  5569.5  5669.5  5686.9  5749.5  5959.5
  6029.5  6069.5  6099.5  6131.2  6489.5  6529.5  6869.5  6999.5  7089.5  7099.5
  7429.5  7509.5  8129.5  8329.5  8379.5  8659.5  8739.5  9189.5  9269.5  9528.3
  108.71  103.41  101.21  101.41  103.41  104.21  104.01  104.01   99.91  101.31
  100.71   99.71  101.01   99.71   98.61   99.81   98.31   97.58   97.55   98.68
   98.96   99.04  102.54  103.63  104.45  104.45  104.69  104.73   104.7   101.2
   98.69   98.59    98.2   97.81   98.91   99.31   97.02   97.37   99.01  100.51
  100.41   98.55   98.67    98.8  100.91  100.21  101.81  100.91  100.91  100.11
  101.31  100.81  102.11  100.21  101.81  103.01  102.41  102.71  100.91  104.51
  108.71  103.41  101.21  101.41  103.41  104.21  104.01  104.01   99.91  101.31
  100.71   99.71  101.01   99.71   98.61   99.81   98.31   97.49   97.29   97.92
   98.42   96.95   96.95   98.04   98.86   98.69  100.22  100.11   100.1   100.1
   98.56   97.88    98.2   97.81   98.91   99.31   96.91   97.37   99.01  100.51
  100.41   98.51   98.41   98.61  100.91  100.21  101.81  100.91  100.91  100.11
  101.31  100.81  102.11  100.21  101.81  103.01  102.41  102.71  100.91  104.51
  1935.1  2875.1  2905.1  2935.1  2965.1  3005.1  3025.1  3265.1  3485.1  3695.1
  3715.1  3735.1  3915.1  4115.1  4155.1  4265.1  4515.1  4846.5    4890  4928.8
    4942 4946.19  4946.3  4998.8 5048.96 5049.07  5063.4  5065.8    5066 5066.11
  5101.5  5155.9  5214.5  5319.5  5559.5  5569.5  5669.5  5686.9  5749.5  5959.5
  6029.5  6069.5  6099.5  6131.2  6489.5  6529.5  6869.5  6999.5  7089.5  7099.5
  7429.5  7509.5  8129.5  8329.5  8379.5  8659.5  8739.5  9189.5  9269.5  9528.3
  108.71  103.41  101.21  101.41  103.41  104.21  104.01  104.01   99.91  101.31
  100.71   99.71  101.01   99.71   98.61   99.81   98.31   97.58   97.55   98.68
   98.96   99.04  102.54  103.63  104.45  104.45  104.69  104.73   104.7   101.2
   98.69   98.59    98.2   97.81   98.91   99.31   97.02   97.37   99.01  100.51
  100.41   98.55   98.67    98.8  100.91  100.21  101.81  100.91  100.91  100.11
  101.31  100.81  102.11  100.21  101.81  103.01  102.41  102.71  100.91  104.51
  108.71  103.41  101.21  101.41  103.41  104.21  104.01  104.01   99.91  101.31
  100.71   99.71  101.01   99.71   98.61   99.81   98.31   97.49   97.29   97.92
   98.42   96.95   96.95   98.04   98.86   98.69  100.22  100.11   100.1   100.1
   98.56   97.88    98.2   97.81   98.91   99.31   96.91   97.37   99.01  100.51
  100.41   98.51   98.41   98.61  100.91  100.21  101.81  100.91  100.91  100.11
  101.31  100.81  102.11  100.21  101.81  103.01  102.41  102.71  100.91  104.51
Pier Skew, UpSta & Num, DnSta & Num=  ,4961.4, 2 ,4961.4, 2 , 0 , 0 , 0 ,,
       1       1
    90.6   98.27
       1       1
    90.9   98.57
Pier Skew, UpSta & Num, DnSta & Num=  ,4981.3, 2 ,4981.3, 2 , 0 , 0 , 0 ,,
       1       1
   83.68   98.69
       1       1
   83.98   98.99
Pier Skew, UpSta & Num, DnSta & Num=  ,5001.6, 2 ,5001.6, 2 , 0 , 0 , 0 ,,
       1       1
   79.18   99.09
       1       1
   79.48   99.39
Pier Skew, UpSta & Num, DnSta & Num=  ,5020.6, 2 ,5020.6, 2 , 0 , 0 , 0 ,,
       1       1
    85.6    99.4
       1       1
    85.9    99.7
Abutment Skew #Up #Dn= , 2 , 2
 4940.37 4984.77
   98.37   83.95
 4940.37 4984.77
   98.67   84.25
Abutment Skew #Up #Dn= , 2 , 2
 5004.27 5049.16
   80.56   98.86
 5004.27 5049.16
   80.86   99.16
BR Coef= 1 , 1 , 0 ,1.25, 0 ,,,0.8,0,2,0,
WSPro=,,,, 1 ,,,, 0 ,,,, 0 ,,,,-1 ,-1 ,-1 , 0 , 0 , 0 , 0 , 0
BR U #Sta/Elev= 99
  1935.1  108.71  2875.1  103.41  2905.1  101.21  2935.1  101.41  2965.1  103.41
  3005.1  104.21  3025.1  104.01  3265.1  104.01  3485.1   99.91  3695.1  101.31
  3715.1  100.71  3735.1   99.71  3915.1  101.01  4115.1   99.71  4155.1   98.61
  4265.1   99.81  4515.1   98.31  4527.5   98.28  4846.5   97.49    4848   97.48
  4888.9   97.27    4890   97.29  4928.8   97.92  4931.4   98.02  4936.5   98.21
 4940.48   98.36 4940.57   98.37    4942   98.42  4946.1   96.45 4946.19   96.41
  4946.3   96.36 4946.41   96.31  4948.3    95.4  4959.9   92.65  4966.9   88.91
  4974.2   85.78  4980.2   84.66  4983.3   84.79 4984.77   83.95  4986.8   82.79
  4988.8   82.56  4990.3   81.07  4991.1   80.59  4997.1   80.06  4998.8   79.91
 5004.27   80.56  5007.1    80.9  5007.2   80.21  5009.8   81.18  5012.5   83.24
  5022.2   87.55  5026.1   89.14  5029.2   91.47  5048.2    98.6 5048.96   98.68
 5049.07   98.69  5063.4  100.22  5065.8  100.11 5065.89  100.11    5066   100.1
 5066.11   100.1  5068.9   99.97  5081.9   99.37  5101.5   98.56  5102.8   98.51
  5155.9   97.88  5164.1   97.92  5214.5    98.2  5286.9   97.93  5319.5   97.81
  5559.5   98.91  5569.5   99.31  5669.5   96.91  5686.9   97.37  5749.5   99.01
  5959.5  100.51  6029.5  100.41  6069.5   98.51  6099.5   98.41  6131.2   98.61
  6489.5  100.91  6529.5  100.21  6869.5  101.81  6999.5  100.91  7071.1  100.91
  7089.5  100.91  7099.5  100.11  7429.5  101.31  7509.5  100.81  8129.5  102.11
  8251.3  100.95  8329.5  100.21  8379.5  101.81  8659.5  103.01  8739.5  102.41
  9189.5  102.71  9269.5  100.91  9299.5  101.31  9528.3  104.51
BR U #Mann= 8
  1935.1     .99  1935.1     .08  4936.5     .04    4942     .04  5063.4     .04
  5068.9     .08  7071.1     .05  8251.3     .08
BR U Banks=4942,5063.4
BR D #Sta/Elev= 99
  1935.1  108.71  2875.1  103.41  2905.1  101.21  2935.1  101.41  2965.1  103.41
  3005.1  104.21  3025.1  104.01  3265.1  104.01  3485.1   99.91  3695.1  101.31
  3715.1  100.71  3735.1   99.71  3915.1  101.01  4115.1   99.71  4155.1   98.61
  4265.1   99.81  4515.1   98.31  4527.5   98.28  4846.5   97.49    4848   97.48
  4888.9   97.27    4890   97.29  4928.8   97.92  4931.4   98.02  4936.5   98.21
 4940.48   98.36 4940.57   98.37    4942   98.72  4946.1   96.75 4946.19   96.71
  4946.3   96.66 4946.41   96.61  4948.3    95.7  4959.9   92.95  4966.9   89.21
  4974.2   86.08  4980.2   84.96  4983.3   85.09 4984.77   84.25  4986.8   83.09
  4988.8   82.86  4990.3   81.37  4991.1   80.89  4997.1   80.36  4998.8   80.21
 5004.27   80.86  5007.1    81.2  5007.2   80.51  5009.8   81.48  5012.5   83.54
  5022.2   87.85  5026.1   89.44  5029.2   91.77  5048.2    98.9 5048.96   98.98
 5049.07   98.99  5063.4  100.52  5065.8  100.11 5065.89  100.11    5066   100.1
 5066.11   100.1  5068.9   99.97  5081.9   99.37  5101.5   98.56  5102.8   98.51
  5155.9   97.88  5164.1   97.92  5214.5    98.2  5286.9   97.93  5319.5   97.81
  5559.5   98.91  5569.5   99.31  5669.5   96.91  5686.9   97.37  5749.5   99.01
  5959.5  100.51  6029.5  100.41  6069.5   98.51  6099.5   98.41  6131.2   98.61
  6489.5  100.91  6529.5  100.21  6869.5  101.81  6999.5  100.91  7071.1  100.91
  7089.5  100.91  7099.5  100.11  7429.5  101.31  7509.5  100.81  8129.5  102.11
  8251.3  100.95  8329.5  100.21  8379.5  101.81  8659.5  103.01  8739.5  102.41
  9189.5  102.71  9269.5  100.91  9299.5  101.31  9528.3  104.51
BR D #Mann= 7
  1935.1     .08  4936.5     .04    4942     .04  5063.4     .04  5068.9     .08
  7071.1     .05  8251.3     .08
BR D Banks=4942,5063.4
BC Design=,, 0 ,, 0 ,,,,,,
BC HTab HWMax=108.71
BC Use User HTab Curves=0
BC User HTab FreeFlow(D)= 0

Type RM Length L Ch R = 1 ,97546.0 ,91.5,101,102
BEGIN DESCRIPTION:
Downstream Section of Bridge/Culvert/Weir
END DESCRIPTION:
XS GIS Cut Line= 4
      3061687.23     13888653.17       3061073.4     13885687.36
      3061044.68     13885610.95      3059125.45     13881551.79
#Sta/Elev= 30
  1935.1  108.71  2875.1  103.41  2905.1  101.21  3005.1  104.21  3265.1  104.01
  3485.1   99.91  3695.1  101.31  3735.1   99.71  4155.1   98.61  4936.5   98.21
    4942   98.64  4974.2      86  4998.8   80.13  5009.8    81.4  5029.2   91.69
  5048.2   98.82  5063.4  100.44  5068.9   99.97  5155.9   97.88  5569.5   99.31
  5669.5   96.91  5959.5  100.51  6099.5   98.41  6489.5  100.91  7071.1  100.91
  8251.3  100.95  8659.5  103.01  9189.5  102.71  9269.5  100.91  9528.3  104.51
#Mann= 7 ,-1 , 0
  1935.1     .08       0  4936.5     .04       0    4942     .04       0
  5063.4     .04       0  5068.9     .08       0  7071.1     .05       0
  8251.3     .08       0
#XS Ineff= 3 ,-1
    2500  4936.2    97.8  5057.9    625099.89999    6250    9515     104
Permanent Ineff=
       F       F       F
Bank Sta=4942,5063.4
XS Rating Curve= 0 ,0
Exp/Cntr=0.5,0.3

Type RM Length L Ch R = 1 ,97445.  ,528.4,391,232.8
BEGIN DESCRIPTION:
Equador Drive - D\S - XS 1
END DESCRIPTION:
XS GIS Cut Line= 4
      3061495.79     13887634.08      3061155.47     13885627.93
      3061126.75     13885551.52      3059207.52     13881492.36
#Sta/Elev= 30
  2920.9  104.73  3440.9   103.3  3850.9      99  4120.9   99.91  4910.9   97.89
  4940.9   95.79 4992.69   79.87 5000.69   79.21 5008.78   79.97 5015.67   84.12
  5057.3    95.7  5087.3   98.43  5487.3  100.06  5647.3   97.05  5677.3   98.49
  6167.3   99.19  6247.3   101.5  6487.3   99.63  6967.3  100.87  7027.3   97.79
  7067.3   90.23  7377.3   89.41  7397.3   90.35  7437.3   99.12  7457.3  100.93
  8177.3  102.61  8537.3  101.19  9137.3  102.58  9257.3   100.7  9527.4  104.28
#Mann= 5 ,-1 , 0
  2920.9     .08       0  4910.9     .04       0  5087.3     .08       0
  7067.3     .05       0  8177.3     .08       0
#XS Ineff= 2 , 0
       0                    6255       0     104
Permanent Ineff=
       F       F
#Block Obstruct= 1 ,-1
 6969.16 7490.75   100.9
Bank Sta=4910.9,5087.3
XS Rating Curve= 0 ,0
Exp/Cntr=0.3,0.1

Type RM Length L Ch R = 1 ,97054.0 ,247.4,366,562.2
BEGIN DESCRIPTION:
Cross Section E100-00-00-X70
END DESCRIPTION:
XS GIS Cut Line= 5
       3061638.4     13888271.02      3061513.66     13887797.02
      3061519.82     13885395.06      3061166.63     13885103.85
      3059303.58     13880750.58
#Sta/Elev= 30
  1935.5     107  2295.5     104  4135.6    97.9  4405.6   101.5  4615.6    98.1
  4827.6   100.3  4940.5   98.33  4982.1   82.17  4985.5   77.37    5008   75.66
  5012.3   75.81  5020.8   83.53  5061.2   97.65  6235.4   102.1  6693.6   99.18
  6725.4    96.8  6775.4    87.4  6825.4    98.6  6843.2  100.01    6949   100.5
  7005.4    98.6  7085.4    89.9  7125.4    88.3  7234.4   97.48  7275.4   100.6
  8985.4   102.7  9159.7  100.86  9205.4   102.5  9411.1  101.31 10020.5   104.1
#Mann= 10 ,-1 , 0
  1935.5     .08       0  4940.5     .04       0  5061.2     .08       0
  6693.6     .04       0  6843.2     .08       0    6949     .04       0
  7234.4     .05       0  9159.7     .08       0  9411.1      .1       0
 10020.5     .99       0
#XS Ineff= 2 , 0
       0    3490     104    5589       0     104
Permanent Ineff=
       F       F
#Block Obstruct= 2 ,-1
  6626.2  7275.4   100.6    7276  7276.5      70
Bank Sta=4940.5,5061.2
XS Rating Curve= 0 ,0
Exp/Cntr=0.3,0.1

Type RM Length L Ch R = 1 ,96688.  ,130.1,102,97.3
BEGIN DESCRIPTION:
Hwy 8 South Feeder - U\S - XS 4
-Modified left bank location
END DESCRIPTION:
XS GIS Cut Line= 4
      3061542.33     13887527.71      3061591.85     13886289.63
      3061676.13     13885420.66      3061777.68     13883049.36
#Sta/Elev= 30
  2567.7  104.68  3806.8    98.7  4366.8  100.99  4416.8  100.21  4839.8   100.9
  4889.8   99.46  4909.8   97.28  4939.8   88.94 4973.02    82.8 4978.27   80.45
 4981.26   78.14 4999.01   74.63 5005.34    74.8 5021.73    78.7 5039.14   88.43
 5045.66    97.1 5071.37  100.72  5077.3  100.64 5132.47     101 5224.92     100
 5277.53  101.07 5693.63  100.77 5895.01     100 6101.69   98.94  6399.8  100.06
  6679.8   99.44  6709.8   98.48  6769.8   99.14  6849.8   98.32  7053.3   99.17
#Mann= 4 ,-1 , 0
  2567.7     .08       0  4889.8     .04       0 5045.66     .04       0
 5895.01     .08       0
#XS Ineff= 2 , 0
       0  4779.4     104  5170.1       0     104
Permanent Ineff=
       F       F
Bank Sta=4889.8,5077.3
XS Rating Curve= 0 ,0
Exp/Cntr=0.5,0.3

Type RM Length L Ch R = 1 ,96586.0 ,73,72,67.7
BEGIN DESCRIPTION:
Upstream Section of Bridge/Culvert/Weir
END DESCRIPTION:
XS GIS Cut Line= 6
      3061669.24     13888135.23      3061595.79     13887454.89
      3061631.86     13886365.75      3061697.42     13885859.99
      3061772.35     13885429.15       3061873.9     13883057.85
#Sta/Elev= 30
  1957.9  106.03  2642.2  104.53  3801.9   98.63  4291.9  100.83  4401.9   99.73
  4431.9  100.53  4551.9   99.83  4737.8  101.81  4742.1  100.89  4877.4   101.6
  4896.4    97.7  4917.9   97.48  4926.4   94.33  4937.1   88.66  4958.8   84.74
  4967.8   84.58  4973.6    81.6  4976.9   78.66  4996.5   74.34  5003.3   74.43
  5020.9   77.07  5039.6   88.45  5046.6   98.98  5074.2  101.57  5189.8   100.5
  5229.4   101.8  5870.8   98.94  6929.2   99.43  6989.2  102.13  7052.7  109.13
#Mann= 6 , 1 , 0
  1957.9     .99       0  1957.9     .08       0  4877.4     .04       0
  5074.2     .04       0  5870.8     .08       0  7052.7     .99       0
#XS Ineff= 2 , 0
       0  4879.4     104  5070.1       0     104
Permanent Ineff=
       F       F
Bank Sta=4877.4,5074.2
XS Rating Curve= 0 ,0
Exp/Cntr=0.5,0.3