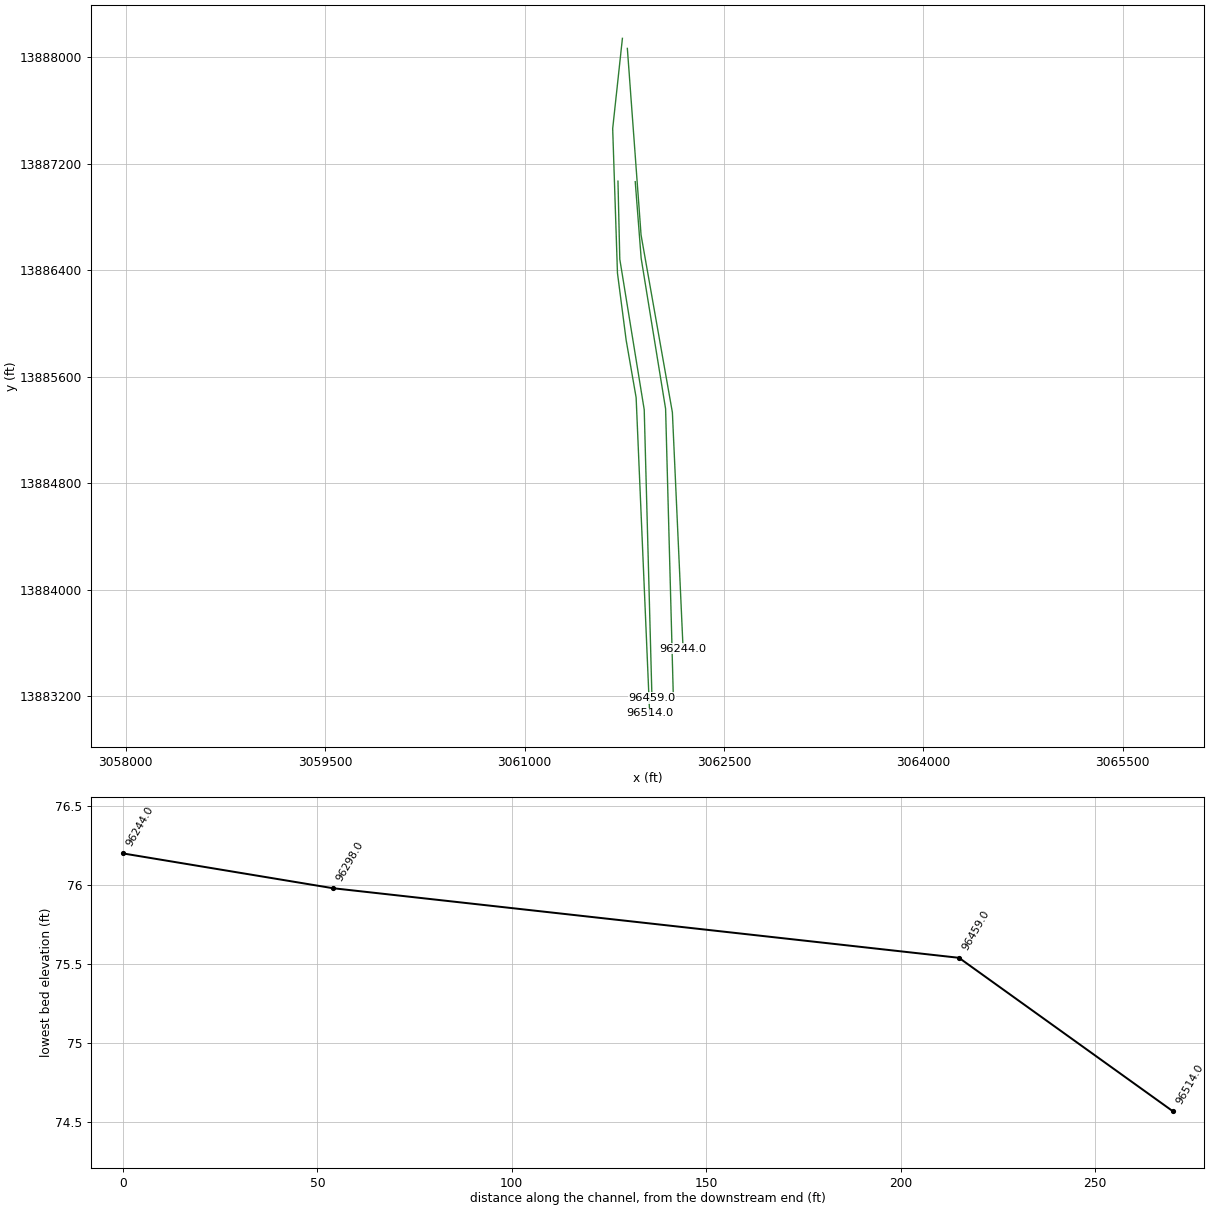
HEC-RAS study E100-00-00.prj: E100-00-00

--- E100-00-00.g02 (geometry) --- (continued)

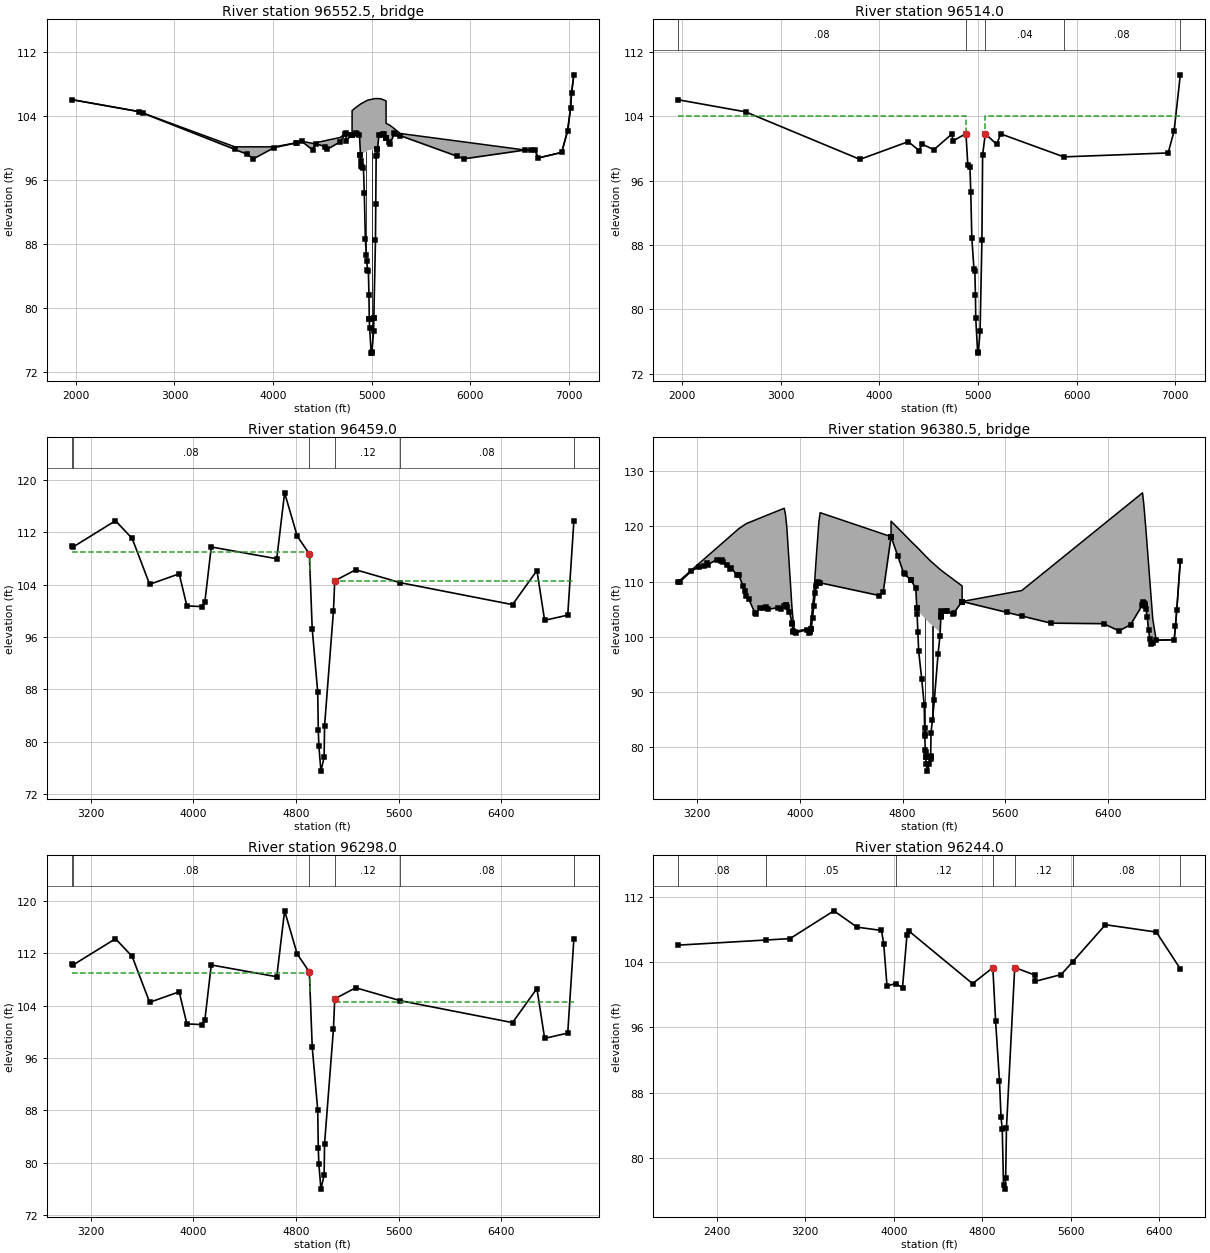
Type RM Length L Ch R = 3 ,96552.5 ,,,
BEGIN DESCRIPTION:
SAM HOUSTON TOLLWAY-SOUTHBOUND FEEDER
Structure ID: E100-00-00-48
END DESCRIPTION:
Bridge Culvert--1,0,-1,-1, 0
Deck Dist Width WeirC Skew NumUp NumDn MinLoCord MaxHiCord MaxSubmerge Is_Ogee
10,47,2.6,0, 40, 40, , , 0.95, 0, ,,,
  1957.9  2642.2  3612.2  3731.9  3801.9  4011.9  4241.9  4291.9  4401.9  4431.9
  4531.9  4551.9  4679.2  4737.8  4742.1 4802.39  4802.5  4837.5  4877.4 4887.51
  4958.8  5039.6  5060.1  5074.2  5094.5  5120.2  5147.1 5147.21  5189.8  5229.4
  5290.1  5939.2  6559.2  6659.2  6689.2  6929.2  6989.2  7019.2  7029.2  7052.7
     106   104.5   100.1   100.1   100.1   100.1  100.61  100.81  100.53  100.61
  100.87  100.93  101.26  101.79  101.45  101.83  104.63  104.99  105.35  105.44
  105.93  106.14  106.13  106.12   106.1  105.98  105.84  103.04  102.76  102.38
  101.77  100.71    99.7    99.7    98.7    99.4   102.1   104.9   106.8   109.1
     106   104.5   99.78    99.2    98.6     100   100.6   100.8    99.7   100.5
   100.1    99.8   100.7  101.78  100.86  101.57  101.57  101.78  101.57   99.13
   99.63   99.84   99.78  101.54  101.62  101.73  101.24  101.24  100.47  101.77
   101.5    98.6    99.7    99.7    98.7    99.4   102.1   104.9   106.8   109.1
  1957.9  2642.2  3612.2  3731.9  3801.9  4011.9  4241.9  4291.9  4401.9  4431.9
  4531.9  4551.9  4679.2  4737.8  4742.1 4802.39  4802.5  4837.5  4877.4 4887.51
  4958.8  5039.6  5060.1  5074.2  5094.5  5120.2  5147.1 5147.21  5189.8  5229.4
  5290.1  5939.2  6559.2  6659.2  6689.2  6929.2  6989.2  7019.2  7029.2  7052.7
     106   104.5   100.1   100.1   100.1   100.1  100.61  100.81  100.53  100.61
  100.87  100.93  101.26  101.79  101.45  101.83  104.63  104.99  105.35  105.44
  105.93  106.14  106.13  106.12   106.1  105.98  105.84  103.04  102.76  102.38
  101.77  100.71    99.7    99.7    98.7    99.4   102.1   104.9   106.8   109.1
     106   104.5   99.78    99.2    98.6     100   100.6   100.8    99.7   100.5
   100.1    99.8   100.7  101.78  100.86  101.57  101.57  101.78  101.57   99.13
   99.63   99.84   99.78  101.54  101.62  101.73  101.24  101.24  100.47  101.77
   101.5    98.6    99.7    99.7    98.7    99.4   102.1   104.9   106.8   109.1
Pier Skew, UpSta & Num, DnSta & Num=  ,4946.4, 2 ,4946.4, 2 , 0 , 0 , 0 ,,
     1.5     1.5
   85.51  100.57
     1.5     1.5
   85.64   100.7
Pier Skew, UpSta & Num, DnSta & Num=  ,5003.3, 2 ,5003.3, 2 , 0 , 0 , 0 ,,
     1.5     1.5
   73.39  100.78
     1.5     1.5
   73.52  100.91
Abutment Skew #Up #Dn= , 2 , 2
  4887.4    4977
   99.14    78.6
  4887.4    4977
   99.27   78.73
Abutment Skew #Up #Dn= , 2 , 2
  5022.9 5060.19
   78.74   99.83
  5022.9 5060.19
   78.87   99.96
BR Coef= 1 , 1 , 0 ,1.25, 0 ,,,0.8,-1,2,0,
WSPro=,,,, 1 ,,,, 0 ,,,, 0 ,,,,-1 ,-1 ,-1 , 0 , 0 , 0 , 0 , 0
BR U #Sta/Elev= 77
  1957.9     106  2642.2   104.5  2682.3   104.3  3612.2   99.78  3731.9    99.2
  3801.9    98.6  4011.9     100  4236.4  100.59  4241.9   100.6  4291.9   100.8
  4401.9    99.7  4431.9   100.5  4531.9   100.1  4551.9    99.8  4679.2   100.7
  4733.2   101.7  4737.8  101.78  4742.1  100.86  4795.1  101.53  4798.5  101.55
 4802.39  101.57  4802.5  101.57 4802.61  101.57  4837.5  101.78  4852.6   101.7
  4877.4  101.57 4887.51   99.13  4887.6   99.11  4891.1   98.27  4896.4   97.67
  4902.3   97.61  4917.9   97.45  4926.4    94.3  4937.1   88.63  4946.4   86.63
  4951.4   85.86  4958.8   84.71  4967.8   84.55  4973.6   81.57  4976.9   78.63
    4977    78.6  4980.4   77.44  4996.5   74.31  5000.1   74.36  5003.3    74.4
  5020.9   77.04  5022.8   78.68  5022.9   78.74  5039.6   88.42  5042.6   92.93
  5046.6   98.95    5054   99.02 5059.99   99.77  5060.1   99.78  5074.2  101.54
  5094.5  101.62  5120.2  101.73    5122   101.7 5146.99  101.25  5147.1  101.24
 5147.21  101.24  5179.1  100.66  5189.8  100.47  5229.4  101.77  5236.4  101.74
  5290.1   101.5  5870.8   98.91  5939.2    98.6  6559.2    99.7  6619.6    99.7
  6659.2    99.7  6689.2    98.7  6929.2    99.4  6989.2   102.1  7019.2   104.9
  7029.2   106.8  7052.7   109.1
BR U #Mann= 6
  1957.9     .99  1957.9     .08  4877.4    .035  5074.2     .04  5870.8     .08
  7052.7     .99
BR U Banks=4877.4,5074.2
BR D #Sta/Elev= 77
  1957.9     106  2642.2   104.5  2682.3   104.3  3612.2   99.78  3731.9    99.2
  3801.9    98.6  4011.9     100  4236.4  100.59  4241.9   100.6  4291.9   100.8
  4401.9    99.7  4431.9   100.5  4531.9   100.1  4551.9    99.8  4679.2   100.7
  4733.2   101.7  4737.8  101.78  4742.1  100.86  4795.1  101.53  4798.5  101.55
 4802.39  101.57  4802.5  101.57 4802.61  101.57  4837.5  101.78  4852.6   101.7
  4877.4   101.7 4887.51   99.26  4887.6   99.24  4891.1    98.4  4896.4    97.8
  4902.3   97.74  4917.9   97.58  4926.4   94.43  4937.1   88.76  4946.4   86.76
  4951.4   85.99  4958.8   84.84  4967.8   84.68  4973.6    81.7  4976.9   78.76
    4977   78.73  4980.4   77.57  4996.5   74.44  5000.1   74.49  5003.3   74.53
  5020.9   77.17  5022.8   78.81  5022.9   78.87  5039.6   88.55  5042.6   93.06
  5046.6   99.08    5054   99.15 5059.99    99.9  5060.1   99.91  5074.2  101.67
  5094.5  101.62  5120.2  101.73    5122   101.7 5146.99  101.25  5147.1  101.24
 5147.21  101.24  5179.1  100.66  5189.8  100.47  5229.4  101.77  5236.4  101.74
  5290.1   101.5  5870.8   98.91  5939.2    98.6  6559.2    99.7  6619.6    99.7
  6659.2    99.7  6689.2    98.7  6929.2    99.4  6989.2   102.1  7019.2   104.9
  7029.2   106.8  7052.7   109.1
BR D #Mann= 4
  1957.9     .08  4877.4    .035  5074.2     .04  5870.8     .08
BR D Banks=4877.4,5074.2
BC Design=,, 0 ,, 0 ,,,,,,
BC HTab HWMax=109.13
BC Use User HTab Curves=0
BC User HTab FreeFlow(D)= 0

Type RM Length L Ch R = 1 ,96514.0 ,55.2,55,52
BEGIN DESCRIPTION:
Downstream Section of Bridge/Culvert/Weir
END DESCRIPTION:
XS GIS Cut Line= 6
      3061736.16     13888143.91      3061662.93     13887465.67
      3061698.88     13886380.09      3061764.18     13885876.39
      3061839.32     13885444.28      3061940.96     13883071.04
#Sta/Elev= 30
  1957.9  106.03  2642.2  104.53  3801.9   98.63  4291.9  100.83  4401.9   99.73
  4431.9  100.53  4551.9   99.83  4737.8  101.81  4742.1  100.89  4877.4  101.83
  4896.4   97.93  4917.9   97.71  4926.4   94.56  4937.1   88.89  4958.8   84.97
  4967.8   84.81  4973.6   81.83  4976.9   78.89  4996.5   74.57  5003.3   74.66
  5020.9    77.3  5039.6   88.68  5046.6   99.21  5074.2   101.8  5189.8   100.5
  5229.4   101.8  5870.8   98.94  6929.2   99.43  6989.2  102.13  7052.7  109.13
#Mann= 5 ,-1 , 0
  1957.9     .08       0  4877.4     .04       0  5074.2     .04       0
  5870.8     .08       0  7052.7     .99       0
#XS Ineff= 2 , 0
       0  4879.4     104  5070.1       0     104
Permanent Ineff=
       F       F
Bank Sta=4877.4,5074.2
XS Rating Curve= 0 ,0
Exp/Cntr=0.5,0.3

Type RM Length L Ch R = 1 ,96459.0 ,160,161,161.1
BEGIN DESCRIPTION:
Upstream Section of Bridge/Culvert/Weir
END DESCRIPTION:
XS GIS Cut Line= 4
      3061702.68     13887070.73      3061716.38     13886484.67
       3061900.2     13885353.05      3061958.42     13883186.21
#Sta/Elev= 30
  3052.9  109.85  3063.3  109.75  3393.3  113.75  3523.3  111.05  3659.5  104.05
  3889.5  105.65  3949.5  100.75  4069.5  100.65  4089.5  101.35  4139.5  109.75
  4649.5  107.95  4710.8  118.01  4808.9  111.41  4903.3  108.69  4925.8   97.25
  4968.7   87.59    4973   81.84  4977.3   79.45  4993.5   75.54  5018.4   77.65
    5022   82.49  5091.2     100  5101.1  104.58  5264.6  106.27  5613.3  104.29
    6486  100.95    6676  106.15    6736   98.55    6916   99.35  6963.6  113.65
#Mann= 6 , 1 , 0
  3052.9     .99       0  3063.3     .08       0  4903.3     .04       0
  5101.1     .12       0  5613.3     .08       0  6963.6     .99       0
#XS Ineff= 2 , 0
       0  4909.3     109  5099.9       0   104.5
Permanent Ineff=
       F       F
Bank Sta=4903.3,5101.1
XS Rating Curve= 0 ,0
Exp/Cntr=0.5,0.3

Type RM Length L Ch R = 3 ,96380.5 ,,,
BEGIN DESCRIPTION:
SAM HOUSTON TOLLWAY MAIN LANES
Structure ID: E100-00-00-47a
END DESCRIPTION:
Bridge Culvert--1,0,-1,-1, 0
Deck Dist Width WeirC Skew NumUp NumDn MinLoCord MaxHiCord MaxSubmerge Is_Ogee
10,137,2.6,0, 60, 60, 106.4, , 0.95, 0, ,,,
  3052.9  3153.3  3273.3  3283.3  3393.3  3453.3  3463.3  3523.3  3583.3  3659.5
  3689.5  3849.5  3878.7  3888.7  3898.7  3919.5  3938.7  3949.5  3958.7  4059.5
  4078.7  4089.5  4108.7  4119.5  4129.5  4148.7  4158.7  4619.5  4649.5 4710.49
  4710.6  4710.8  4808.9  4865.9  4903.3  4911.3  4913.3  5009.5  5091.2  5101.1
  5194.2    5264 5264.11  5264.6  5728.9    5956    6366    6486    6576  6669.4
  6679.4    6696    6706    6716    6736  6749.3    6776    6916    6936  6963.6
     110  112.04  114.49  114.69  116.93  118.15  118.36  119.58  120.53  121.24
  121.53  123.03   123.3   122.1   119.9  112.36   105.4  102.56     101  101.42
   101.5  103.27   107.6  111.38  114.88   120.9   122.5  118.88  118.64  118.16
  120.96  120.96  118.66  117.31  116.46  116.28  116.24  113.93  112.25  112.06
  110.44  109.23  106.43  106.42   108.4  112.67  120.39  122.65  124.34   126.1
     124  119.39  116.36  113.32  107.24   103.2    99.4    99.5   104.9   113.8
  109.99  111.89  113.39  113.09  113.89  112.29  112.49  111.19  107.49  104.19
  105.29  104.99  105.57  105.77  105.42  104.59  102.48  100.89  100.84  101.29
  100.88  101.49  105.59  107.89  109.29  109.84  109.79  107.49  108.09   118.1
  118.12  118.15  111.55  110.25  108.83  105.15  104.83  102.52  100.84  104.72
  104.18  106.39  106.39  106.41  103.78  102.49  102.39  101.09  102.19  105.89
  106.19  105.09  103.59  101.19   98.69   98.92   99.39   99.49  104.89  113.79
  3052.9  3153.3  3273.3  3283.3  3353.3  3393.3  3453.3  3463.3  3523.3  3583.3
  3659.5  3689.5  3849.5  3878.7  3888.7  3898.7  3919.5  3938.7  3949.5  3958.7
  4059.5  4078.7  4089.5  4108.7  4119.5  4129.5  4148.7  4158.7  4619.5  4649.5
 4710.49  4710.6  4710.8  4808.9  4865.9  4903.3  4911.3  4913.3  5009.5  5091.2
  5101.1  5194.2    5264 5264.11  5728.9    5956    6366    6486    6576  6669.4
  6679.4    6696    6706    6716    6736  6749.3    6776    6916    6936  6963.6
  110.25  112.15  114.49  114.69  116.12  116.93  118.15  118.36  119.58  120.53
  121.24  121.53  123.03   123.3   122.1   119.9  112.36   105.4  102.56   101.1
  101.55   101.5  103.27   107.6  111.38  114.88   120.9   122.5  118.88  118.64
  118.36  120.96  120.96  118.66  117.31  116.46  116.28  116.24  113.93  112.25
  112.06  110.44  109.23  106.65   108.4  112.67  120.39  122.65  124.34   126.1
     124  119.39  116.36  113.32  107.24   103.2   99.65   99.75  105.15  114.05
  110.25  112.15  113.65  113.35  114.25  114.15  112.55  112.75  111.45  107.75
  104.45  105.55  105.25  105.83  106.03  105.68  104.85  102.74  101.15   101.1
  101.55  101.14  101.75  105.85  108.15  109.55   110.1  110.05  107.75  108.35
  118.36  118.38  118.41  111.81  110.51  109.09  105.41  105.09  102.78   101.1
  104.98  104.44  106.65  106.65  104.04  102.75  102.65  101.35  102.45  106.15
  106.45  105.35  103.85  101.45   98.95   99.18   99.65   99.75  105.15  114.05
Pier Skew, UpSta & Num, DnSta & Num=  ,4973, 2 ,4973, 2 , 0 , 0 , 0 ,,
     1.5     1.5
   80.56  104.42
     1.5     1.5
   80.82  104.68
Pier Skew, UpSta & Num, DnSta & Num=  ,5032.7, 2 ,5032.7, 2 , 0 , 0 , 0 ,,
     1.5     1.5
   83.75  103.06
     1.5     1.5
   84.01  103.32
Abutment Skew #Up #Dn= , 2 , 2
  4911.1    4981
  105.15   78.26
  4911.1    4981
  105.41   78.52
Abutment Skew #Up #Dn= , 2 , 2
    5019 5098.99
   78.47  103.65
    5019 5098.99
   78.73  103.91
BR Coef= 1 , 1 , 0 ,1.25, 0 ,,,0.8,0,2,0,
WSPro=,,,, 1 ,,,, 0 ,,,, 0 ,,,,-1 ,-1 ,-1 , 0 , 0 , 0 , 0 , 0
BR U #Sta/Elev= 127
  3052.9  109.99  3063.3  109.89  3153.3  111.89  3213.3  112.69  3253.3  112.89
  3273.3  113.39  3283.3  113.09  3353.3  113.99  3383.3  113.69  3393.3  113.89
  3403.3  113.49  3433.3  113.09  3453.3  112.29  3463.3  112.49  3513.3  111.19
  3523.3  111.19  3558.7  109.21  3573.3  108.39  3583.3  107.49  3603.3  106.79
  3649.5  104.39  3659.5  104.19  3689.5  105.29  3719.5  105.29  3739.5  105.49
  3749.5  104.99  3829.5  105.29  3849.5  104.99  3878.7  105.57  3888.7  105.77
  3889.5  105.79  3898.7  105.42  3919.5  104.59  3938.7  102.48  3939.5  102.39
  3948.7  101.01  3949.5  100.89  3958.7  100.84  3969.5  100.79  4059.5  101.29
  4069.5  100.79  4078.7  100.88  4079.5  100.89  4088.7  101.44  4089.5  101.49
  4098.7  103.45  4108.7  105.59  4119.5  107.89  4129.5  109.29  4138.7  109.84
  4139.5  109.89  4148.7  109.84  4158.7  109.79  4619.5  107.49  4649.5  108.09
 4710.49   118.1  4710.6  118.12 4710.71  118.14  4710.8  118.15  4710.9  118.14
  4763.1  114.63  4808.9  111.55  4815.5   111.4  4865.8  110.25  4865.9  110.25
  4903.3  108.83 4911.21  105.19  4911.3  105.15  4913.3  104.23  4919.3  100.95
  4925.8   97.39  4948.9   92.45  4968.7   87.73    4972   83.53  4972.9   82.39
    4973   81.98  4977.3   79.59  4979.9   79.22  4980.9   78.32    4981   78.26
    4983   77.02  4993.5   75.68  5009.5   77.04  5018.4   77.79  5018.9   78.33
    5019   78.47    5022   82.63  5032.7   84.91  5047.5   88.48  5076.4   96.83
  5091.2  100.14 5098.79  103.65  5098.9   103.7    5099  103.75  5101.1  104.72
  5142.3  104.64  5143.9  104.63  5194.2  104.18  5200.2  104.37 5263.89  106.39
    5264  106.39 5264.11  106.39  5264.5  106.41  5264.6  106.41  5613.3  104.43
  5728.9  103.78    5956  102.49    6366  102.39    6486  101.09    6576  102.19
    6666  105.69  6669.4  105.89    6676  106.29  6679.4  106.19    6686  105.99
  6689.4  105.68    6696  105.09    6706  103.59    6716  101.19    6726   99.69
    6736   98.69  6749.3   98.92    6776   99.39    6916   99.49    6926  101.89
    6936  104.89  6963.6  113.79
BR U #Mann= 6
  3052.9     .99  3063.3     .08  4903.3    .035  5101.1     .12  5613.3     .08
  6963.6     .99
BR U Banks=4903.3,5101.1
BR D #Sta/Elev= 127
  3052.9  110.25  3063.3  110.15  3153.3  112.15  3213.3  112.95  3253.3  113.15
  3273.3  113.65  3283.3  113.35  3353.3  114.25  3383.3  113.95  3393.3  114.15
  3403.3  113.75  3433.3  113.35  3453.3  112.55  3463.3  112.75  3513.3  111.45
  3523.3  111.45  3558.7  109.47  3573.3  108.65  3583.3  107.75  3603.3  107.05
  3649.5  104.65  3659.5  104.45  3689.5  105.55  3719.5  105.55  3739.5  105.75
  3749.5  105.25  3829.5  105.55  3849.5  105.25  3878.7  105.83  3888.7  106.03
  3889.5  106.05  3898.7  105.68  3919.5  104.85  3938.7  102.74  3939.5  102.65
  3948.7  101.27  3949.5  101.15  3958.7   101.1  3969.5  101.05  4059.5  101.55
  4069.5  101.05  4078.7  101.14  4079.5  101.15  4088.7   101.7  4089.5  101.75
  4098.7  103.71  4108.7  105.85  4119.5  108.15  4129.5  109.55  4138.7   110.1
  4139.5  110.15  4148.7   110.1  4158.7  110.05  4619.5  107.75  4649.5  108.35
 4710.49  118.36  4710.6  118.38 4710.71   118.4  4710.8  118.41  4710.9   118.4
  4763.1  114.89  4808.9  111.81  4815.5  111.66  4865.8  110.51  4865.9  110.51
  4903.3  109.09 4911.21  105.45  4911.3  105.41  4913.3  104.49  4919.3  101.21
  4925.8   97.65  4948.9   92.71  4968.7   87.99    4972   83.79  4972.9   82.65
    4973   82.24  4977.3   79.85  4979.9   79.48  4980.9   78.58    4981   78.52
    4983   77.28  4993.5   75.94  5009.5    77.3  5018.4   78.05  5018.9   78.59
    5019   78.73    5022   82.89  5032.7   85.17  5047.5   88.74  5076.4   97.09
  5091.2   100.4 5098.79  103.91  5098.9  103.96    5099  104.01  5101.1  104.98
  5142.3   104.9  5143.9  104.89  5194.2  104.44  5200.2  104.63 5263.89  106.65
    5264  106.65 5264.11  106.65  5264.5  106.67  5264.6  106.67  5613.3  104.69
  5728.9  104.04    5956  102.75    6366  102.65    6486  101.35    6576  102.45
    6666  105.95  6669.4  106.15    6676  106.55  6679.4  106.45    6686  106.25
  6689.4  105.94    6696  105.35    6706  103.85    6716  101.45    6726   99.95
    6736   98.95  6749.3   99.18    6776   99.65    6916   99.75    6926  102.15
    6936  105.15  6963.6  114.05
BR D #Mann= 6
  3052.9     .99  3063.3     .08  4903.3    .035  5101.1     .12  5613.3     .08
  6963.6     .99
BR D Banks=4903.3,5101.1
BC Design=,, 0 ,, 0 ,,,,,,
BC HTab HWMax=118.01
BC Use User HTab Curves=0
BC User HTab FreeFlow(D)= 0

Type RM Length L Ch R = 1 ,96298.0 ,52,54,55.9
BEGIN DESCRIPTION:
Downstream Section of Bridge/Culvert/Weir
END DESCRIPTION:
XS GIS Cut Line= 4
      3061832.57     13887066.82      3061877.19     13886491.15
      3062060.98     13885359.68      3062119.37      13883186.8
#Sta/Elev= 30
  3052.9  110.29  3063.3  110.19  3393.3  114.19  3523.3  111.49  3659.5  104.49
  3889.5  106.09  3949.5  101.19  4069.5  101.09  4089.5  101.79  4139.5  110.19
  4649.5  108.39  4710.8  118.45  4808.9  111.85  4903.3  109.13  4925.8   97.69
  4968.7   88.03    4973   82.28  4977.3   79.89  4993.5   75.98  5018.4   78.09
    5022   82.93  5091.2  100.44  5101.1  105.02  5264.6  106.71  5613.3  104.73
    6486  101.39    6676  106.59    6736   98.99    6916   99.79  6963.6  114.09
#Mann= 6 , 1 , 0
  3052.9     .99       0  3063.3     .08       0  4903.3     .04       0
  5101.1     .12       0  5613.3     .08       0  6963.6     .99       0
#XS Ineff= 2 , 0
       0  4909.3     109  5099.9       0   104.5
Permanent Ineff=
       F       F
Bank Sta=4903.3,5101.1
XS Rating Curve= 0 ,0
Exp/Cntr=0.5,0.3

Type RM Length L Ch R = 1 ,96244.0 ,67.6,68,69
BEGIN DESCRIPTION:
Upstream Section of Bridge/Culvert/Weir
END DESCRIPTION:
XS GIS Cut Line= 4
      3061773.25     13888068.17      3061876.51     13886665.54
      3062112.03     13885332.86      3062192.45     13883557.87
#Sta/Elev= 30
  2052.3  106.06  2846.8  106.69  3062.3  106.86  3458.7  110.26  3668.7  108.26
  3888.7  107.86  3908.7  106.26  3938.7  101.06  4015.7  101.36  4078.7  100.86
  4118.7  107.26  4138.7  107.76  4711.7  101.35    4895   103.3  4919.9   96.75
  4955.1   89.42    4969   84.97    4980   83.54  4991.3   76.72  5004.3    76.2
  5010.9   77.57    5018   83.69  5092.7  103.32  5276.7  102.39  5278.3  101.63
  5512.1  102.46    5616  104.02  5912.1  108.56  6372.1  107.66  6588.9  103.16
#Mann= 7 ,-1 , 0
  2052.3     .08       0  2846.8     .05       0  4015.7     .12       0
    4895     .04       0  5092.7     .12       0    5616     .08       0
  6588.9     .99       0
#XS Ineff= 2 , 0
       0  4898.4     102  5088.9       0   101.9
Permanent Ineff=
       F       F
Bank Sta=4895,5092.7
XS Rating Curve= 0 ,0
Exp/Cntr=0.5,0.3