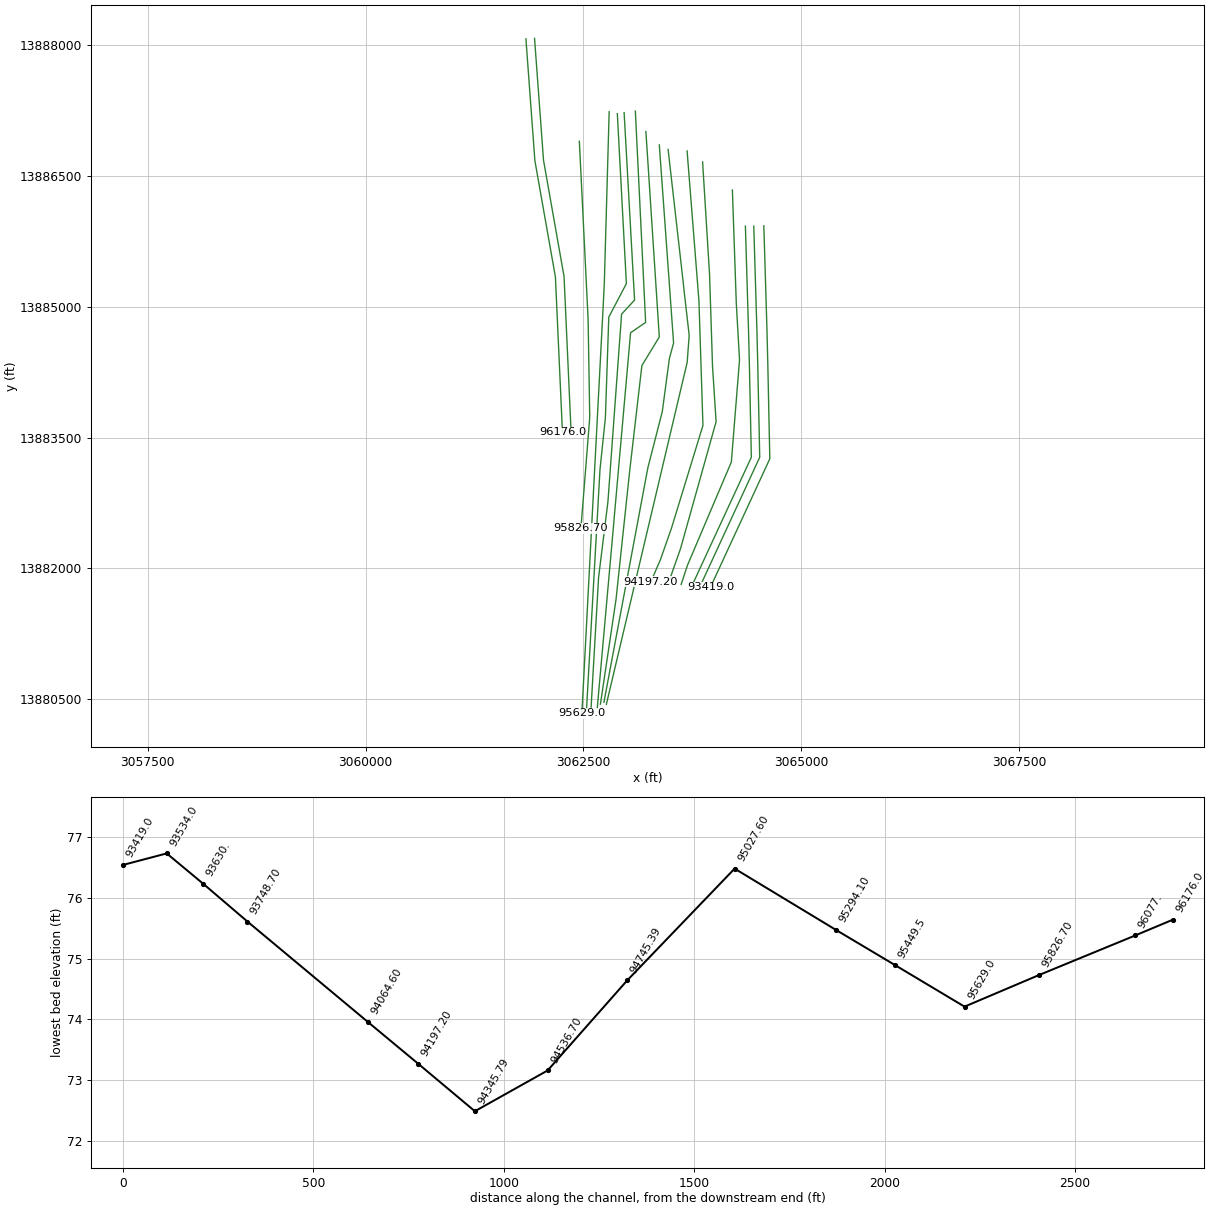
HEC-RAS study E100-00-00.prj: E100-00-00

--- E100-00-00.g02 (geometry) --- (continued)

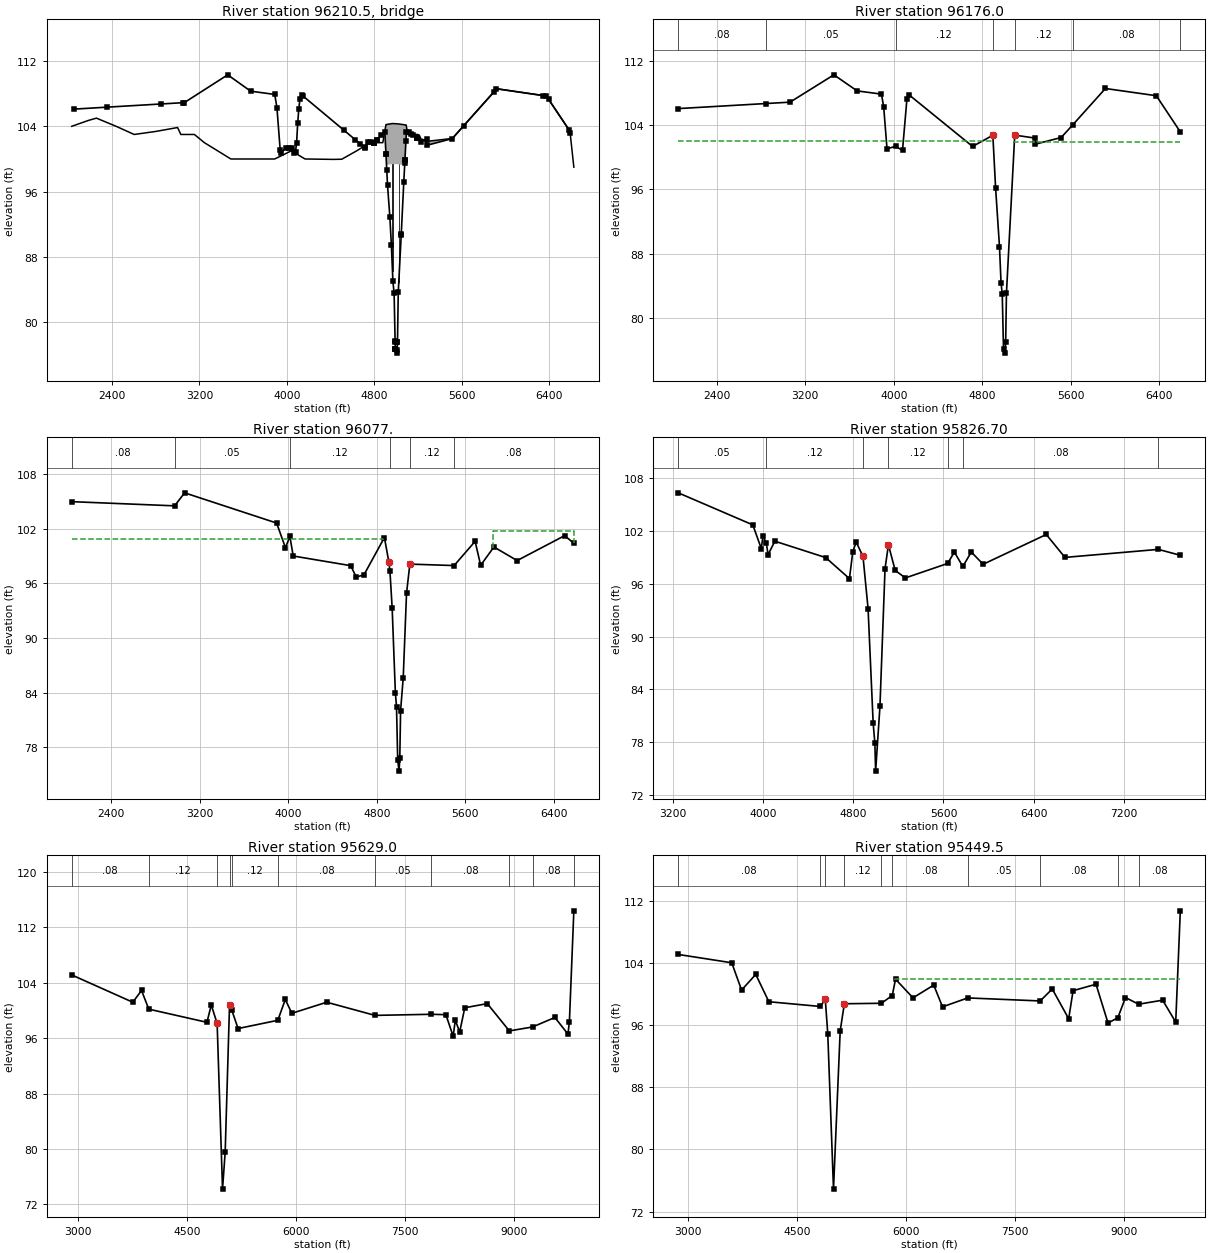
Type RM Length L Ch R = 3 ,96210.5 ,,,
BEGIN DESCRIPTION:
SAM HOUSTON TOLLWAY-NORTHBOUND FEEDER
Structure ID: E100-00-00-47
END DESCRIPTION:
Bridge Culvert--1,0,-1,-1, 0
Deck Dist Width WeirC Skew NumUp NumDn MinLoCord MaxHiCord MaxSubmerge Is_Ogee
10,47,2.6,0, 49, 49, 102, , 0.95, 0, ,,,
  2033.4  2183.5  2258.6  2438.7  2603.9    2805  3000.5  3030.6  3154.4  3245.3
  3487.8  3888.6  4040.6  4165.9  4426.5  4501.3  4638.2  4755.7  4876.6  4905.8
  4909.4  4965.1  5022.2  5086.6  5090.2  5105.1  5120.1  5135.1  5150.1  5165.1
  5180.1  5195.1  5210.1  5225.2  5240.2  5255.2  5270.2  5276.7  5278.3  5512.1
    5616  5892.1  5912.1  6341.5  6372.1  6392.1  6582.1  6588.9    6623
     104  104.71     105     104     103  103.38  103.85     103     103     102
     100     100     101     100   99.95   99.97     101  101.98     102  104.22
  104.22  104.34  104.29  104.16  104.16     103     103     103     103     103
     103     103  102.92  102.44   102.4  102.31     102  102.44  102.16  102.51
  104.07  108.21  108.61  107.77  107.71  107.31  103.51  103.21      99
                                                                                
                                                                           99.27
   99.27   99.39   99.34   99.21   99.21     102     102     102     102     102
     102     102 101.917 101.444 101.405 101.307     101
                                                                        
  2033.4  2183.5  2258.6  2438.7  2603.9    2805  3000.5  3030.6  3154.4  3245.3
  3487.8  3888.6  4040.6  4165.9  4426.5  4501.3  4638.2  4755.7  4876.6  4905.8
  4909.4  4965.1  5022.2  5086.6  5090.2  5105.1  5120.1  5135.1  5150.1  5165.1
  5180.1  5195.1  5210.1  5225.2  5240.2  5255.2  5270.2  5276.7  5278.3  5512.1
    5616  5892.1  5912.1  6341.5  6372.1  6392.1  6582.1  6588.9    6623
     104  104.71     105     104     103  103.38  103.85     103     103     102
     100     100     101     100   99.95   99.97     101  101.98     102  104.22
  104.22  104.34  104.29  104.16  104.16     103     103     103     103     103
     103     103  102.92  102.44   102.4  102.31     102  102.44  102.16  102.51
  104.07  108.21  108.61  107.77  107.71  107.31  103.51  103.21      99
                                                                                
                                                                           99.27
   99.27   99.39   99.34   99.21   99.21     102     102     102     102     102
     102     102 101.917 101.444 101.405 101.307     101
                                                                        
Pier Skew, UpSta & Num, DnSta & Num=  ,4965.1, 4 ,4965.1, 4 , 3 , 3 , 0 ,,
     1.5     1.5     2.5     2.5
   56.88   96.88   96.89   99.39
     1.5     1.5     2.5     2.5
   56.88   96.88   96.89   99.39
Pier Skew, UpSta & Num, DnSta & Num=  ,5022.2, 4 ,5022.2, 4 , 3 , 3 , 0 ,,
     1.5     1.5     2.5     2.5
   56.83   96.83   96.84   99.34
     1.5     1.5     2.5     2.5
   56.83   96.83   96.84   99.34
Abutment Skew #Up #Dn= , 2 , 2
  4905.2  4989.2
   100.7   77.64
  4905.2  4989.2
  100.13   77.07
Abutment Skew #Up #Dn= , 2 , 2
  5010.9 5078.99
   77.61  100.01
  5010.9 5078.99
   77.04   99.44
BR Coef= 1 , 1 , 0 ,1.25, 0 ,,,0.8,-1,2,0,
WSPro=,,,, 1 ,,,, 0 ,,,, 0 ,,,,-1 ,-1 ,-1 , 0 , 0 , 0 , 0 , 0
BR U #Sta/Elev= 81
  2052.3   106.1  2351.9  106.34  2846.8  106.73  3047.6  106.89  3062.3   106.9
  3458.7   110.3  3668.7   108.3  3888.7   107.9  3908.7   106.3  3938.7   101.1
  3948.7   100.7  3988.7   101.4  4015.7   101.4  4048.7   101.4  4068.7   100.7
  4078.7   100.9  4088.7     102  4098.7   104.4  4108.7   106.1  4118.7   107.3
  4138.7   107.8  4145.1  107.73  4521.4  103.52  4624.8  102.36  4669.9  101.86
  4711.7  101.39  4717.7  101.52  4744.5  102.12  4770.1  102.06 4796.29     102
  4796.4     102 4796.51     102  4799.9  101.99  4821.2  102.31  4821.5  102.31
  4863.2  102.93    4895  103.34 4905.31  100.63  4905.4   100.6  4912.9   98.63
  4919.9   96.79  4941.2   92.88  4955.1   89.46    4969   85.01    4980   83.58
  4989.1   77.68  4989.2   77.64  4991.3   76.76    4992   76.73  4992.4   76.72
  5004.3   76.24  5008.7   76.64  5010.8   77.57  5010.9   77.61    5018   83.73
  5045.1   90.75  5045.2   90.78  5068.3   97.13  5077.5   99.53 5078.79   99.86
  5078.9   99.88    5088  102.18  5092.7  103.36  5111.7  103.28  5138.8  103.04
    5156  102.89 5191.09  102.53  5191.2  102.53 5191.31  102.53  5229.9  102.14
  5276.7  102.43  5278.3  101.67  5512.1   102.5    5616  104.06  5892.1   108.2
  5912.1   108.6  6341.5  107.76  6372.1   107.7  6392.1   107.3  6582.1   103.5
  6588.9   103.2
BR U #Mann= 7
  2052.3     .08  2846.8     .05  4015.7     .12    4895    .035  5092.7     .12
    5616     .08  6588.9     .99
BR U Banks=4895,5092.7
BR D #Sta/Elev= 81
  2052.3   106.1  2351.9  106.34  2846.8  106.73  3047.6  106.89  3062.3   106.9
  3458.7   110.3  3668.7   108.3  3888.7   107.9  3908.7   106.3  3938.7   101.1
  3948.7   100.7  3988.7   101.4  4015.7   101.4  4048.7   101.4  4068.7   100.7
  4078.7   100.9  4088.7     102  4098.7   104.4  4108.7   106.1  4118.7   107.3
  4138.7   107.8  4145.1  107.73  4521.4  103.52  4624.8  102.36  4669.9  101.86
  4711.7  101.39  4717.7  101.52  4744.5  102.12  4770.1  102.06 4796.29     102
  4796.4     102 4796.51     102  4799.9  101.99  4821.2  102.31  4821.5  102.31
  4863.2  102.93    4895  102.77 4905.31  100.06  4905.4  100.03  4912.9   98.06
  4919.9   96.22  4941.2   92.31  4955.1   88.89    4969   84.44    4980   83.01
  4989.1   77.11  4989.2   77.07  4991.3   76.19    4992   76.16  4992.4   76.15
  5004.3   75.67  5008.7   76.07  5010.8      77  5010.9   77.04    5018   83.16
  5045.1   90.18  5045.2   90.21  5068.3   96.56  5077.5   98.96 5078.79   99.29
  5078.9   99.31    5088  101.61  5092.7  102.79  5111.7  103.28  5138.8  103.04
    5156  102.89 5191.09  102.53  5191.2  102.53 5191.31  102.53  5229.9  102.14
  5276.7  102.43  5278.3  101.67  5512.1   102.5    5616  104.06  5892.1   108.2
  5912.1   108.6  6341.5  107.76  6372.1   107.7  6392.1   107.3  6582.1   103.5
  6588.9   103.2
BR D #Mann= 7
  2052.3     .08  2846.8     .05  4015.7     .12    4895    .035  5092.7     .12
    5616     .08  6588.9     .99
BR D Banks=4895,5092.7
BC Design=,, 0 ,, 0 ,,,,,,
BC HTab HWMax=110.26
BC Use User HTab Curves=0
BC User HTab FreeFlow(D)= 0

Type RM Length L Ch R = 1 ,96176.0 ,98,99,121.9
BEGIN DESCRIPTION:
Downstream Section of Bridge/Culvert/Weir
END DESCRIPTION:
XS GIS Cut Line= 4
      3061840.57     13888075.24       3061943.5     13886677.16
      3062179.24     13885343.22      3062259.92      13883562.4
#Sta/Elev= 30
  2052.3  106.06  2846.8  106.69  3062.3  106.86  3458.7  110.26  3668.7  108.26
  3888.7  107.86  3908.7  106.26  3938.7  101.06  4015.7  101.36  4078.7  100.86
  4118.7  107.26  4138.7  107.76  4711.7  101.35    4895  102.74  4919.9   96.19
  4955.1   88.86    4969   84.41    4980   82.98  4991.3   76.16  5004.3   75.64
  5010.9   77.01    5018   83.13  5092.7  102.76  5276.7  102.39  5278.3  101.63
  5512.1  102.46    5616  104.02  5912.1  108.56  6372.1  107.66  6588.9  103.16
#Mann= 7 ,-1 , 0
  2052.3     .08       0  2846.8     .05       0  4015.7     .12       0
    4895     .04       0  5092.7     .12       0    5616     .08       0
  6588.9     .99       0
#XS Ineff= 2 , 0
       0  4898.4     102  5088.9       0   101.9
Permanent Ineff=
       F       F
Bank Sta=4895,5092.7
XS Rating Curve= 0 ,0
Exp/Cntr=0.5,0.3

Type RM Length L Ch R = 1 ,96077.  ,247.9,252.3,377.8
BEGIN DESCRIPTION:
Hwy 8 North Feeder- D\S - XS 1
END DESCRIPTION:
XS GIS Cut Line= 4
      3061939.62      13888080.9      3062042.55     13886682.82
      3062278.29     13885348.88      3062358.97     13883568.06
#Sta/Elev= 30
  2043.2  104.98  2973.2  104.52  3063.2  105.95  3895.1  102.63  3975.1   99.92
  4015.1  101.16  4045.1   99.01  4565.1   97.95  4615.1   96.69  4685.1   96.95
  4869.7  101.04  4909.7   98.36  4919.7   97.35  4939.7    93.3 4968.77   83.98
 4979.13   82.46 4989.77    76.6 5002.02   75.38 5008.73   76.79 5015.95   82.03
  5039.7   85.62  5069.7   94.92  5099.7   98.12  5499.7   97.96  5689.7  100.62
  5739.7   97.99  5859.7     100  6069.7   98.51  6499.7  101.25  6582.3   100.4
#Mann= 6 ,-1 , 0
  2043.2     .08       0  2973.2     .05       0  4015.1     .12       0
  4919.7     .04       0  5099.7     .12       0  5499.7     .08       0
#XS Ineff= 2 , 0
       0    4859  100.86    5855       0   101.8
Permanent Ineff=
       F       F
Bank Sta=4909.7,5099.7
XS Rating Curve= 0 ,0
Exp/Cntr=0.3,0.1

Type RM Length L Ch R = 1 ,95826.70,199.1,195.7,140.4
BEGIN DESCRIPTION:
PBS&J Add XS
END DESCRIPTION:
XS GIS Cut Line= 6
        3062454.       13886900.        3062553.       13884890.
        3062555.       13884831.        3062573.       13883751.
        3062571.       13883702.        3062472.       13882458.
#Sta/Elev= 30
    3249  106.32 3910.07  102.68  3985.2   99.99 4000.23  101.45 4030.27  100.57
  4045.3    99.3  4105.4  100.83 4556.13   98.97 4766.47   96.58 4796.53   99.66
 4826.57  100.73 4886.67    99.1 4931.73   93.17 4976.83   80.18 4991.83   77.91
  4998.7   74.73 5036.93   82.07    5082   97.71 5112.03  100.42 5172.13   97.51
  5262.3   96.66 5636.53    98.3 5696.57   99.59  5771.6   97.96 5846.63    99.6
  5951.7   98.21 6511.26  101.59 6676.83   98.99 7504.75    99.9 7699.38   99.23
#Mann= 7 ,-1 , 0
    3249     .05       0 4030.27     .12       0 4886.67     .04       0
 5112.03     .12       0 5636.53     .05       0  5771.6     .08       0
 7504.75     .05       0
Bank Sta=4886.67,5112.03
XS Rating Curve= 0 ,0
Exp/Cntr=0.3,0.1

Type RM Length L Ch R = 1 ,95629.0 ,301,181.6,108.8
BEGIN DESCRIPTION:
Cross Section E100-00-00-X69
END DESCRIPTION:
XS GIS Cut Line= 4
  3062796.35073313887238.6858203      3062740.89     13885281.39
      3062729.87     13885051.31      3062483.15      13880336.7
#Sta/Elev= 30
    2917  105.14    3757   101.2    3877   102.9  3976.9   100.2    4777    98.3
    4837   100.8  4917.5   98.13  4991.7   74.21  5028.2   79.55  5088.2  100.82
  5120.5  100.02  5205.4    97.4  5752.7   98.59  5855.4   101.6  5945.4    99.6
  6425.4   101.2  7090.2    99.3  7867.4   99.46  8065.4    99.4  8165.4    96.3
  8195.4    98.6  8255.4    96.9  8325.4   100.4  8635.4     101  8938.8   97.06
  9259.2   97.63  9565.4      99  9745.4    96.6  9765.4    98.4  9826.5   114.4
#Mann= 11 ,-1 , 0
    2917     .08       0  3976.9     .12       0  4917.5     .04       0
  5088.2     .04       0  5120.5     .12       0  5752.7     .08       0
  7090.2     .05       0  7867.4     .08       0  8938.8     .05       0
  9259.2     .08       0  9826.5     .99       0
#XS Ineff= 2 , 0
       0                  5855.4       0   101.6
Permanent Ineff=
       F       F
Bank Sta=4917.5,5088.2
XS Rating Curve= 0 ,0
Exp/Cntr=0.3,0.1

Type RM Length L Ch R = 1 ,95449.5 ,99.9,155.5,101.7
BEGIN DESCRIPTION:
PBS&J Add XS
END DESCRIPTION:
XS GIS Cut Line= 6
        3062890.       13887217.        3062994.       13885267.
        3062792.       13884883.        3062753.       13883728.
        3062691.       13883134.        3062536.       13880376.
#Sta/Elev= 30
    2866  105.07 3601.97     104 3737.13  100.49 3932.37   102.5  4112.6   98.99
 4820.26   98.38 4888.75   99.29 4922.75   94.89  5001.7   74.89 5093.74   95.25
    5151   98.73  5659.8   98.79 5809.96   99.79 5855.03  101.89  6095.3   99.49
 6380.59  101.13 6501.13   98.33 6848.18   99.48 7844.73   99.09 8010.59  100.63
 8236.79    96.8 8297.12  100.41 8612.67  101.24 8777.89   96.25 8913.07   96.93
 9018.21   99.53 9198.45   98.67 9528.89   99.19 9709.13   96.37 9772.21  110.68
#Mann= 10 ,-1 , 0
    2866     .08       0 4820.26     .12       0 4888.75     .04       0
    5151     .12       0  5659.8     .05       0 5809.96     .08       0
 6848.18     .05       0 7844.73     .08       0 8913.07     .05       0
 9198.45     .08       0
#XS Ineff= 2 , 0
                            5853          101.92
Permanent Ineff=
       F       F
Bank Sta=4888.75,5151
XS Rating Curve= 0 ,0
Exp/Cntr=0.3,0.1

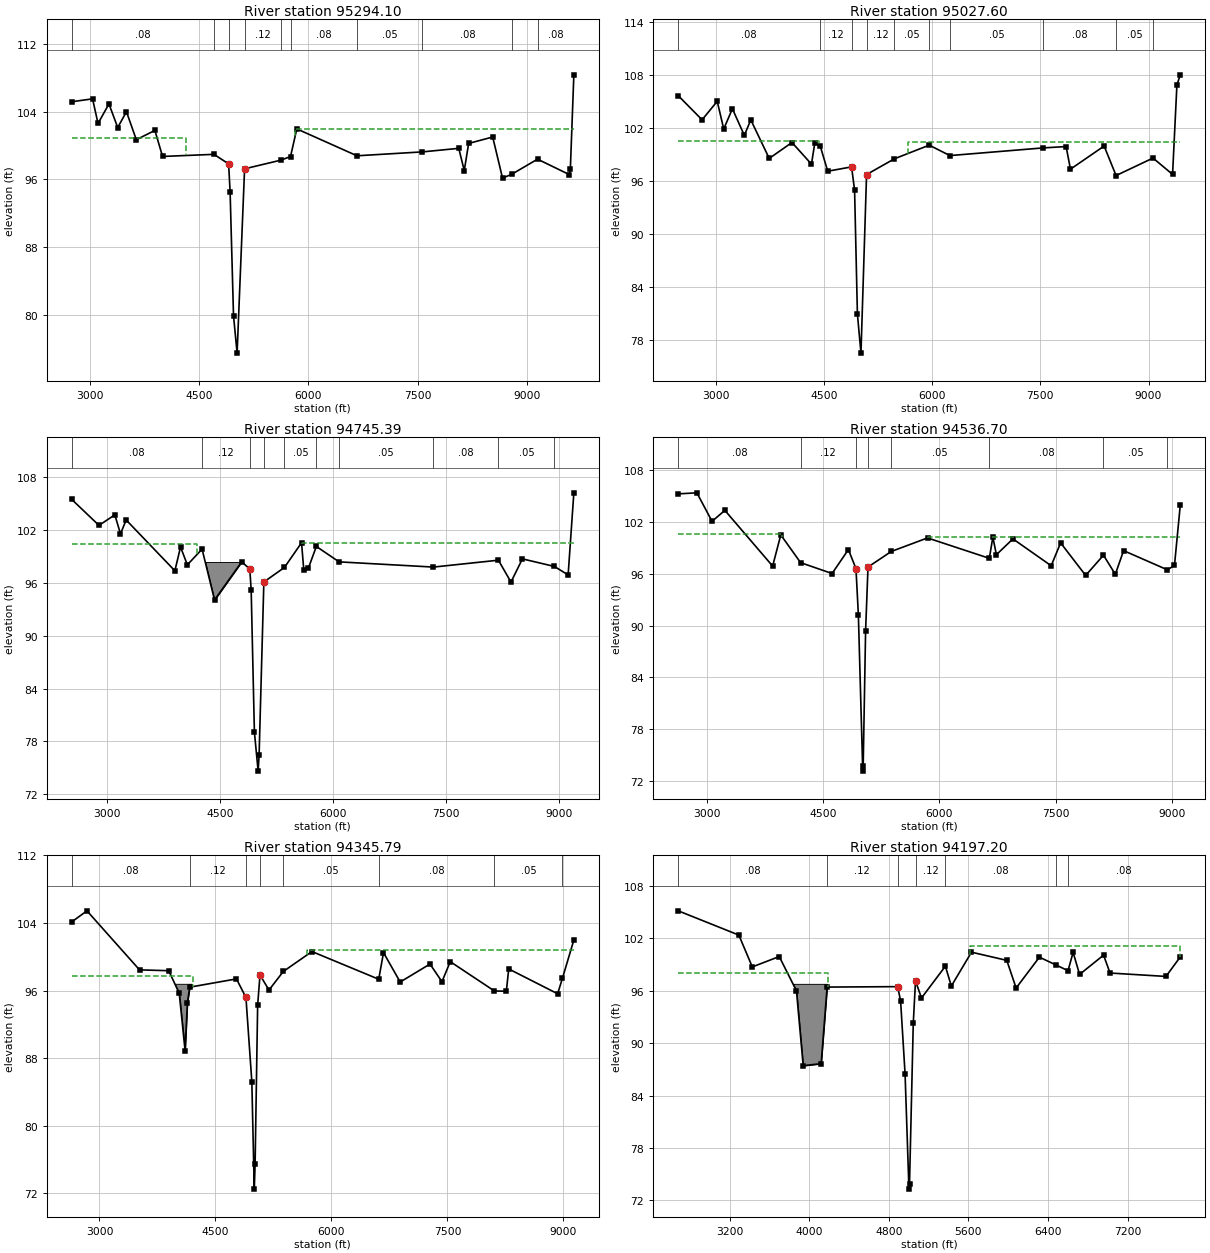
Type RM Length L Ch R = 1 ,95294.10,135.9,266.6,121.8
BEGIN DESCRIPTION:
PBS&J Add XS
END DESCRIPTION:
XS GIS Cut Line= 6
        3062968.       13887229.        3063088.       13885078.
        3062939.       13884917.        3062782.       13882763.
        3062675.       13881897.        3062589.       13880409.
#Sta/Elev= 30
    2750  105.19 3035.53  105.53 3110.67  102.62 3260.93  104.93 3381.17  102.14
  3501.4  104.01 3636.63   100.7 3892.13   101.8  3997.3   98.72 4703.63   98.97
 4904.99   97.84 4925.51    94.5  4972.2   79.89  5021.6   75.47 5124.37   97.26
 5621.86   98.28 5755.47   98.71 5841.68  101.98 6668.44    98.8 7567.87   99.26
 8066.85   99.68 8142.42   97.05 8202.63  100.26 8533.17  101.02  8668.4   96.15
 8803.62   96.66 9149.19    98.4 9584.92   96.58 9599.94    97.2 9648.02  108.37
#Mann= 10 ,-1 , 0
    2750     .08       0 4703.63     .12       0 4904.99     .04       0
 5124.37     .12       0 5621.86     .05       0 5755.47     .08       0
 6668.44     .05       0 7567.87     .08       0 8803.62     .05       0
 9149.19     .08       0
#XS Ineff= 2 , 0
         4323.66  100.85 5820.08          101.97
Permanent Ineff=
       F       F
Bank Sta=4904.99,5124.37
XS Rating Curve= 0 ,0
Exp/Cntr=0.3,0.1

Type RM Length L Ch R = 1 ,95027.60,156.3,282.3,155.6
BEGIN DESCRIPTION:
PBS&J Add XS
END DESCRIPTION:
XS GIS Cut Line= 6
        3063097.       13887246.        3063215.       13884822.
        3063042.       13884703.        3062815.       13882138.
        3062665.       13880458.        3062660.       13880396.
#Sta/Elev= 30
    2477  105.62 2807.53  102.89 3017.87  104.98 3108.03  101.85 3228.23  104.14
  3393.5  101.13 3483.63  102.88 3739.03   98.52 4054.57  100.32    4325   97.87
 4370.07  100.21  4445.2   99.96 4550.36   97.07  4880.9   97.56 4922.96   94.94
  4962.280.89999  5011.6   76.48 5089.1796.69503 5476.55   98.48 5958.71  100.02
 6244.94   98.84 7540.58   99.71 7856.98   99.86 7917.21    97.3 8384.33   99.92
    8550   96.58 9062.32   98.56 9333.52   96.71 9393.75  106.84 9440.93  107.98
#Mann= 10 ,-1 , 0
    2477     .08       0  4445.2     .12       0  4880.9     .04       0
 5089.17     .12       0 5476.55     .05       0 5958.71     .08       0
 6244.94     .05       0 7540.58     .08       0    8550     .05       0
 9062.32     .08       0
#XS Ineff= 2 , 0
         4423.97  100.46 5657.24          100.43
Permanent Ineff=
       F       F
Bank Sta=4880.9,5089.17
XS Rating Curve= 0 ,0
Exp/Cntr=0.3,0.1

Type RM Length L Ch R = 1 ,94745.39,183,208.8,257.1
BEGIN DESCRIPTION:
PBS&J Add XS
END DESCRIPTION:
XS GIS Cut Line= 6
        3063218.       13887012.        3063372.       13884655.
        3063172.       13884327.        3063033.       13883128.
        3062875.       13881643.        3062696.       13880443.
#Sta/Elev= 30
    2534  105.45  2894.8  102.51 3105.23   103.7  3180.4  101.55 3255.57  103.12
 3901.96   97.36 3977.13  100.06 4067.33   98.03 4262.76   99.82  4428.1   94.05
  4788.9   98.38 4896.12   97.55  4914.2   95.16  4957.2   79.06  5006.6   74.64
  5019.4   76.44  5082.6   96.09 5355.91   97.74  5582.5  100.54 5612.67   97.42
  5673.1   97.65 5778.83  100.12 6080.99   98.37 7333.03   97.78 8194.35   98.56
 8361.18   96.08 8512.85   98.71 8937.51   97.85 9119.51   96.89 9195.34   106.2
#Mann= 10 ,-1 , 0
    2534     .08       0 4262.76     .12       0 4896.12     .04       0
  5082.6     .12       0 5355.91     .05       0 5778.83     .08       0
 6080.99     .05       0 7333.03     .08       0 8194.35     .05       0
 8937.51     .08       0
#XS Ineff= 2 , 0
         4197.07  100.39 5584.31          100.56
Permanent Ineff=
       F       F
#Block Obstruct= 1 ,-1
 4283.17 4775.88   98.36
Bank Sta=4896.12,5082.6
XS Rating Curve= 0 ,0
Exp/Cntr=0.3,0.1

Type RM Length L Ch R = 1 ,94536.70,155.5,191,163
BEGIN DESCRIPTION:
PBS&J Add XS
-Increased elevation of right ineffective area to remove jump in 500-year profile (BS-08-04-10)
END DESCRIPTION:
XS GIS Cut Line= 6
        3063372.       13886858.        3063536.       13884586.
        3063488.       13884409.        3063406.       13883798.
        3063241.       13883156.        3062736.       13880463.
#Sta/Elev= 30
    2627  105.25 2867.83  105.37 3063.46  102.07 3228.93  103.34 3845.99   96.89
 3951.32   100.5 4207.09   97.29 4613.49   96.03 4824.15    98.8    4922    96.6
 4953.05   91.26  5009.7   73.16  5015.2   73.71 5046.48   89.43 5077.53   96.78
 5377.42   98.58 5845.91  100.15 6643.97   97.79 6689.69  100.24 6735.42   98.21
 6948.92  100.04 7442.86   96.93 7564.74   99.58 7887.78   95.81 8118.23   98.15
 8271.01   95.94 8377.97   98.68 8943.28   96.46 9034.96   96.97 9110.33     104
#Mann= 8 ,-1 , 0
    2627     .08       0 4207.09     .12       0    4922     .04       0
 5077.53     .12       0 5377.42     .05       0 6643.97     .08       0
 8118.23     .05       0 8943.28     .08       0
#XS Ineff= 2 , 0
       0 3966.29  100.59 5855.48       0   100.2
Permanent Ineff=
       F       F
Bank Sta=4922,5077.53
XS Rating Curve= 0 ,0
Exp/Cntr=0.3,0.1

Type RM Length L Ch R = 1 ,94345.79,185.1,148.6,330.5
BEGIN DESCRIPTION:
PBS&J Add XS
END DESCRIPTION:
XS GIS Cut Line= 6
        3063473.       13886806.        3063647.       13885276.
        3063658.       13885171.        3063715.       13884673.
        3063692.       13884364.        3062764.       13880440.
#Sta/Elev= 30
    2642  104.13 2838.33  105.44 3518.01   98.45 3895.53   98.35 4031.53   95.68
 4106.99    88.9 4137.16   94.56 4167.42    96.4 4771.54   97.38 4894.01   95.18
 4970.15   85.22  5001.7   72.49  5012.5   75.46 5045.41   94.29 5075.78 97.8408
 5192.03   96.06 5377.19   98.26 5747.27  100.62 6610.95   97.34 6672.59  100.49
 6888.34   97.01 7273.95   99.14 7428.28   97.05 7536.04   99.42  8106.8   95.95
 8260.91   95.92 8291.73   98.56 8924.14   95.62 8985.78   97.44 9133.81  101.98
#Mann= 8 ,-1 , 0
    2642     .08       0 4167.42     .12       0 4894.01     .04       0
 5075.78     .12       0 5377.19     .05       0 6610.95     .08       0
  8106.8     .05       0 8985.78     .08       0
#XS Ineff= 2 , 0
         4210.29   97.73    5683          100.86
Permanent Ineff=
       F       F
#Block Obstruct= 1 ,-1
 3942.58 4191.39    96.8
Bank Sta=4894.01,5075.78
XS Rating Curve= 0 ,0
Exp/Cntr=0.3,0.1

Type RM Length L Ch R = 1 ,94197.20,156.8,132.7,141.4
BEGIN DESCRIPTION:
PBS&J Add XS
END DESCRIPTION:
XS GIS Cut Line= 6
3063691.00000001       13886789.        3063827.       13885069.
3063873.00000001       13883640.3063511.9202561413882461.9055277
3063385.7810022713882102.56496463063275.2656078913881845.9129394
#Sta/Elev= 30
    2681  105.17 3290.59  102.39 3426.04   98.74 3696.99   99.93 3870.12      96
 3937.82   87.42 4118.47   87.65 4178.65   96.43 4887.43   96.48 4917.46   94.88
 4962.53   86.51  5001.7   73.27  5007.2   73.82 5045.11   92.27 5067.63   97.13
  5127.7   95.18 5367.96   98.82 5428.03   96.55 5630.74  100.43  5985.8   99.49
 6079.52   96.32 6313.99   99.86 6477.19   98.98 6601.76   98.31 6652.81  100.41
 6717.96   97.88 6959.22  100.09 7024.31   98.04 7586.87   97.65 7731.17   99.89
#Mann= 7 ,-1 , 0
    2681     .08       0 4178.65     .12       0 4887.43     .04       0
 5067.63     .12       0 5367.96     .08       0 6477.19     .05       0
 6601.76     .08       0
#XS Ineff= 2 , 0
   -9.14 4182.91   98.01 5612.18   -9.14  101.18
Permanent Ineff=
       F       F
#Block Obstruct= 1 ,-1
  3837.8 4176.74    96.8
Bank Sta=4887.43,5067.63
XS Rating Curve= 0 ,0
Exp/Cntr=0.3,0.1

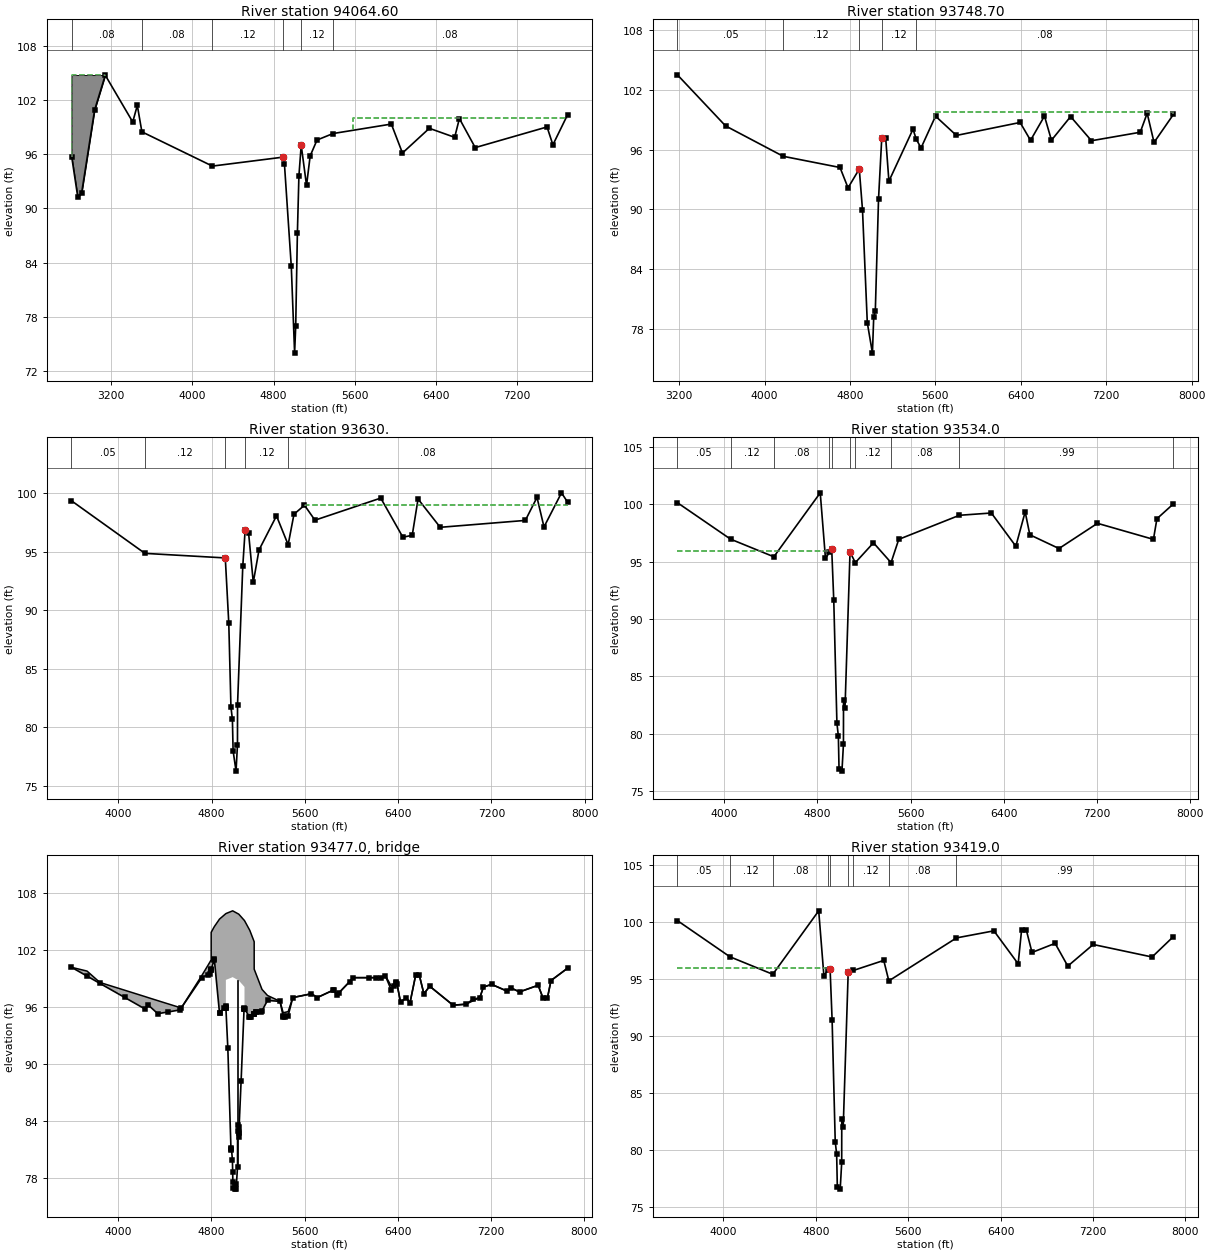
Type RM Length L Ch R = 1 ,94064.60,315.9,316,257.6
BEGIN DESCRIPTION:
PBS&J Add XS
END DESCRIPTION:
XS GIS Cut Line= 6
3063869.00000003       13886663.3063949.00000006       13885370.
3063983.00000001       13884318.3064024.00000001       13883683.
3063616.00000006       13882228.3063487.64906655 13881862.729633
#Sta/Elev= 30
 2811.01   95.74 2871.14   91.25 2908.71    91.7 3036.48   100.9 3141.68  104.78
 3412.24   99.59 3457.34  101.43 3502.44    98.5 4196.77    94.7 4891.49   95.69
 4906.52   94.94 4974.09   83.57  5006.7   73.96  5017.5   76.93 5034.16   87.27
 5049.17   93.62 5071.69   97.02 5124.26   92.55 5159.79   95.82 5227.44   97.59
 5385.29   98.31 5959.72   99.36 6068.97   96.15 6333.75   98.89 6583.28   97.89
 6629.86   99.97 6785.82   96.75 7493.28   99.04 7550.92   97.06 7695.02  100.38
#Mann= 6 ,-1 , 0
 2811.01     .08       0 3502.44     .08       0 4196.77     .12       0
 4891.49     .04       0 5071.69     .12       0 5385.29     .08       0
#XS Ineff= 2 , 0
   -2.58  3139.3  104.82 5579.11   -2.58  100.06
Permanent Ineff=
       F       F
#Block Obstruct= 1 ,-1
  2808.8 3137.95 104.794
Bank Sta=4891.49,5071.69
XS Rating Curve= 0 ,0
Exp/Cntr=0.3,0.1

Type RM Length L Ch R = 1 ,93748.70,138,115.9,174.8
BEGIN DESCRIPTION:
PBS&J Add XS
END DESCRIPTION:
XS GIS Cut Line= 6
        3064211.       13886341.        3064256.       13885036.
        3064293.       13884393.        3064199.       13883220.
        3063695.       13882035.        3063623.       13881817.
#Sta/Elev= 30
    3184  103.48 3634.53   98.37 4175.13   95.32 4706.89    94.2 4782.06   92.16
 4887.26   94.05 4917.29   89.98 4962.39   78.66 5010.42   75.61 5022.52   79.22
 5037.52   79.86 5067.59   91.05 5097.66   97.12 5134.71   97.14 5164.78   92.83
 5390.58   98.04 5420.74   97.03 5465.84   96.16 5601.34   99.34 5797.07   97.41
 6393.46   98.71 6491.19   96.92 6621.63   99.35 6687.04   96.93 6866.35    99.3
  7061.8   96.88 7518.52   97.73 7583.54   99.63  7647.8   96.71 7829.71   99.52
#Mann= 5 ,-1 , 0
    3184     .05       0 4175.13     .12       0 4887.26     .04       0
 5097.66     .12       0 5420.74     .08       0
#XS Ineff= 2 , 0
                         5590.17           99.79
Permanent Ineff=
       F       F
Bank Sta=4887.26,5097.66
XS Rating Curve= 0 ,0
Exp/Cntr=0.3,0.1

Type RM Length L Ch R = 1 ,93630.  ,99.4,96,95
BEGIN DESCRIPTION:
Gessner SB - U/S - XS 4
END DESCRIPTION:
XS GIS Cut Line= 5
      3064360.26     13885926.53      3064396.13     13884737.92
      3064405.86     13884348.95      3064428.68      13883275.1
      3063756.27     13881821.31
#Sta/Elev= 30
  3599.1   99.36  4229.1   94.86  4918.2   94.47  4948.2   88.89 4966.75   81.71
 4979.21   80.67 4985.19   77.97 5010.42   76.23 5022.74   78.49 5023.22   81.91
  5068.2   93.76  5088.2   96.83  5118.2   96.58  5158.2   92.38  5207.3   95.15
  5357.3   98.07  5457.3    95.6  5507.3   98.21  5597.3   98.98  5687.3    97.7
  6251.4   99.59  6441.4   96.24  6521.4   96.41  6571.4   99.51  6761.4   97.09
  7491.4   97.68  7591.4   99.65  7651.4   97.12  7801.4  100.04  7853.2   99.25
#Mann= 5 ,-1 , 0
  3599.1     .05       0  4229.1     .12       0  4918.2     .04       0
  5088.2     .12       0  5457.3     .08       0
#XS Ineff= 2 , 0
       0                    5603       0      99
Permanent Ineff=
       F       F
Bank Sta=4918.2,5088.2
XS Rating Curve= 0 ,0
Exp/Cntr=0.5,0.3

Type RM Length L Ch R = 1 ,93534.0 ,114,115,127.9
BEGIN DESCRIPTION:
Upstream Section of Bridge/Culvert/Weir
END DESCRIPTION:
XS GIS Cut Line= 5
      3064456.47     13885926.53      3064492.35     13884737.92
      3064502.07     13884348.95       3064524.9      13883275.1
      3063852.49     13881821.31
#Sta/Elev= 30
  3600.4  100.15  4056.1   96.97  4427.5   95.43  4825.3  101.01  4870.1    95.3
  4904.6   95.81  4923.8   96.09  4941.3   91.63  4968.4    80.9  4980.7    79.8
  4986.6   76.88  5011.5   76.73  5024.4   79.08  5024.9   82.91  5037.7   82.23
  5080.8   95.84  5126.3   94.92  5281.8   96.65  5432.6   94.92  5498.6   96.95
  6018.6   99.05  6292.7   99.25  6502.7   96.35  6582.7   99.35  6622.7   97.35
  6872.7   96.15  7202.7   98.35  7682.7   96.95  7712.7   98.75  7854.5  100.05
#Mann= 10 ,-1 , 0
  3600.4     .05       0  4056.1     .12       0  4427.5     .08       0
  4904.6     .04       0  4923.8     .04       0  5080.8     .04       0
  5126.3     .12       0  5432.6     .08       0  6018.6     .99       0
  7854.5     .99       0
#XS Ineff= 2 , 0
       0  4913.8   95.95  5090.8       0    95.4
Permanent Ineff=
       F       F
Bank Sta=4923.8,5080.8
XS Rating Curve= 0 ,0
Exp/Cntr=0.5,0.3

Type RM Length L Ch R = 3 ,93477.0 ,,,
BEGIN DESCRIPTION:
GESSNER
Structure ID: E100-00-00-46
END DESCRIPTION:
Bridge Culvert--1,0,-1,-1, 0
Deck Dist Width WeirC Skew NumUp NumDn MinLoCord MaxHiCord MaxSubmerge Is_Ogee
10,94,2.6,0, 60, 60, , , 0.95, 0, ,,,
  3600.4  3733.9  3843.9  4230.4  4260.4  4340.4  4530.4  4543.9  4717.2  4788.1
 4798.39  4798.5  4825.3  4870.1  4923.8 4924.61  4924.7  4982.8    5035 5084.09
  5084.2    5130  5167.3 5167.41  5234.6  5281.8  5388.6  5416.2  5458.6  5498.6
  5658.6  5708.6  5848.6  5878.6  6018.6  6252.7  6292.7  6342.7  6387.3  6392.7
  6422.7  6472.7  6502.7  6552.7  6582.7  6622.7  6672.7  6872.7  6982.7  7102.7
  7132.7  7202.7  7332.7  7372.7  7442.7  7602.7  7642.7  7682.7  7712.7  7854.5
   100.2    99.8    98.6   97.11   96.99   96.68   95.95   95.95   99.31  100.76
  100.99  103.89  104.49  105.29  105.86  105.87  105.87  106.16  105.81  105.13
  105.13  104.09   102.9     100   97.86   97.22   96.61    95.4   95.52   97.01
   97.41   97.01   97.81   97.31   99.11   99.11   99.31   98.22   98.52    98.4
    96.5      97    96.4    99.4    99.4    97.4    98.2    96.2    96.3      97
    98.1    98.4    97.7      98    97.6    98.3      97      97    98.8   100.1
   100.2   99.27    98.5    95.8    96.2    95.3    95.7   95.94   99.09   99.54
   99.96   99.96  101.06   95.35   96.14   95.93   98.87   99.16   98.81   98.13
   95.82    94.9   95.27   95.27   95.62    96.7    96.6   95.04    95.1      97
    97.4      97    97.8    97.3    99.1    99.1    99.3    97.8   98.51    98.4
    96.5      97    96.4    99.4    99.4    97.4    98.2    96.2    96.3      97
    98.1    98.4    97.7      98    97.6    98.3      97      97    98.8   100.1
  3600.4  3733.9  3843.9  4230.4  4260.4  4340.4  4530.4  4543.9  4717.2  4788.1
 4798.39  4798.5  4825.3  4870.1  4923.8 4924.61  4924.7  4982.8    5035 5084.09
  5084.2    5130  5167.3 5167.41  5234.6  5281.8  5388.6  5416.2  5458.6  5498.6
  5658.6  5708.6  5848.6  5878.6  6018.6  6252.7  6292.7  6342.7  6387.3  6392.7
  6422.7  6472.7  6502.7  6552.7  6582.7  6622.7  6672.7  6872.7  6982.7  7102.7
  7132.7  7202.7  7332.7  7372.7  7442.7  7602.7  7642.7  7682.7  7712.7  7854.5
   100.2    99.8    98.6   97.11   96.99   96.68   95.95   95.95   99.31  100.76
  100.99  103.89  104.49  105.29  105.86  105.87  105.87  106.16  105.81  105.13
  105.13  104.09   102.9     100   97.86   97.22   96.61    95.4   95.52   97.01
   97.41   97.01   97.81   97.31   99.11   99.11   99.31   98.22   98.52    98.4
    96.5      97    96.4    99.4    99.4    97.4    98.2    96.2    96.3      97
    98.1    98.4    97.7      98    97.6    98.3      97      97    98.8   100.1
   100.2   99.27    98.5    95.8    96.2    95.3    95.7   95.94   99.09   99.54
   99.96   99.96  101.06   95.35   96.14   95.93   98.87   99.16   98.81   98.13
   95.82    94.9   95.27   95.27   95.62    96.7    96.6   95.04    95.1      97
    97.4      97    97.8    97.3    99.1    99.1    99.3    97.8   98.51    98.4
    96.5      97    96.4    99.4    99.4    97.4    98.2    96.2    96.3      97
    98.1    98.4    97.7      98    97.6    98.3      97      97    98.8   100.1
Pier Skew, UpSta & Num, DnSta & Num=  ,5024.4, 2 ,5024.4, 2 , 0 , 0 , 0 ,,
       3       3
   77.83   99.89
       3       3
   77.62   99.68
Abutment Skew #Up #Dn= , 2 , 2
  4924.5  4968.4
   98.87   80.95
  4924.5  4968.4
   98.66   80.74
Abutment Skew #Up #Dn= , 2 , 2
  5037.8 5084.29
    82.8   98.13
  5037.8 5084.29
   82.59   97.92
BR Coef= 1 , 1 , 0 ,1.25, 0 ,,,0.8,0,1.2,0,
WSPro=,,,, 1 ,,,, 0 ,,,, 0 ,,,,-1 ,-1 ,-1 , 0 , 0 , 0 , 0 , 0
BR U #Sta/Elev= 103
  3600.4   100.2  3733.9   99.27  3843.9    98.5  4056.1   97.02  4230.4    95.8
  4260.4    96.2  4340.4    95.3  4427.5   95.48  4530.4    95.7  4543.9   95.94
  4717.2   99.09  4767.1   99.41  4788.1   99.54 4798.39   99.96  4798.5   99.96
 4798.61   99.97  4824.4  101.02  4825.3  101.06  4870.1   95.35  4873.2    95.4
  4904.6   95.86  4923.8   96.14  4924.5   95.96 4924.61   95.93  4924.7   95.91
  4941.3   91.68  4968.3   80.99  4968.4   80.95  4972.1    81.1  4980.7   79.85
  4982.8   78.58  4984.6   77.49  4986.6   76.93  5001.1   76.81  5011.5   76.78
  5015.5   77.37  5024.4   79.13  5024.9   82.96  5029.2   83.55    5035   82.68
  5037.7   82.28  5037.8    82.8  5037.9   83.31  5055.2    88.2  5080.8   95.89
 5084.09   95.82  5084.2   95.82  5084.3   95.82  5126.3   94.97    5130    94.9
  5136.6   94.97 5167.19   95.27  5167.3   95.27 5167.41   95.27    5183   95.43
  5185.7   95.43  5228.3   95.48  5234.6   95.62  5281.8    96.7  5388.6    96.6
  5416.2   95.04  5418.6    94.9  5432.6   94.97  5458.6    95.1  5498.6      97
  5658.6    97.4  5708.6      97  5846.2   97.79  5848.6    97.8  5878.6    97.3
  5896.2   97.53  5986.2   98.68  6018.6    99.1  6156.2    99.1  6216.2    99.1
  6252.7    99.1  6292.7    99.3  6342.7    97.8  6366.2   98.27  6382.7    98.6
  6387.3   98.51  6392.7    98.4  6422.7    96.5  6472.7      97  6502.7    96.4
  6552.7    99.4  6582.7    99.4  6622.7    97.4  6672.7    98.2  6872.7    96.2
  6982.7    96.3  7042.7    96.8  7102.7      97  7132.7    98.1  7202.7    98.4
  7332.7    97.7  7372.7      98  7442.7    97.6  7602.7    98.3  7642.7      97
  7682.7      97  7712.7    98.8  7854.5   100.1
BR U #Mann= 9
  3600.4     .05  4056.1     .12  4427.5     .08  4904.6     .04  4923.8     .04
  5080.8     .04  5126.3     .12  5432.6     .08  6018.6     .99
BR U Banks=4923.8,5080.8
BR D #Sta/Elev= 103
  3600.4   100.2  3733.9   99.27  3843.9    98.5  4056.1   97.02  4230.4    95.8
  4260.4    96.2  4340.4    95.3  4427.5   95.48  4530.4    95.7  4543.9   95.94
  4717.2   99.09  4767.1   99.41  4788.1   99.54 4798.39   99.96  4798.5   99.96
 4798.61   99.97  4824.4  101.02  4825.3  101.06  4870.1   95.35  4873.2    95.4
  4904.6   95.86  4923.8   95.93  4924.5   95.75 4924.61   95.72  4924.7    95.7
  4941.3   91.47  4968.3   80.78  4968.4   80.74  4972.1   80.89  4980.7   79.64
  4982.8   78.37  4984.6   77.28  4986.6   76.72  5001.1    76.6  5011.5   76.57
  5015.5   77.16  5024.4   78.92  5024.9   82.75  5029.2   83.34    5035   82.47
  5037.7   82.07  5037.8   82.59  5037.9    83.1  5055.2   87.99  5080.8   95.68
 5084.09   95.82  5084.2   95.82  5084.3   95.82  5126.3   94.97    5130    94.9
  5136.6   94.97 5167.19   95.27  5167.3   95.27 5167.41   95.27    5183   95.43
  5185.7   95.43  5228.3   95.48  5234.6   95.62  5281.8    96.7  5388.6    96.6
  5416.2   95.04  5418.6    94.9  5432.6   94.97  5458.6    95.1  5498.6      97
  5658.6    97.4  5708.6      97  5846.2   97.79  5848.6    97.8  5878.6    97.3
  5896.2   97.53  5986.2   98.68  6018.6    99.1  6156.2    99.1  6216.2    99.1
  6252.7    99.1  6292.7    99.3  6342.7    97.8  6366.2   98.27  6382.7    98.6
  6387.3   98.51  6392.7    98.4  6422.7    96.5  6472.7      97  6502.7    96.4
  6552.7    99.4  6582.7    99.4  6622.7    97.4  6672.7    98.2  6872.7    96.2
  6982.7    96.3  7042.7    96.8  7102.7      97  7132.7    98.1  7202.7    98.4
  7332.7    97.7  7372.7      98  7442.7    97.6  7602.7    98.3  7642.7      97
  7682.7      97  7712.7    98.8  7854.5   100.1
BR D #Mann= 9
  3600.4     .05  4056.1     .12  4427.5     .08  4904.6     .04  4923.8     .04
  5080.8     .04  5126.3     .12  5432.6     .08  6018.6     .99
BR D Banks=4923.8,5080.8
BC Design=,, 0 ,, 0 ,,,,,,
BC HTab HWMax=101.01
BC Use User HTab Curves=0
BC User HTab FreeFlow(D)= 0

Type RM Length L Ch R = 1 ,93419.0 ,100,99,90.1
BEGIN DESCRIPTION:
Downstream Section of Bridge/Culvert/Weir
END DESCRIPTION:
XS GIS Cut Line= 5
      3064571.95     13885930.21      3064607.83     13884741.37
      3064617.56       13884352.      3064640.84     13883257.18
      3063959.69     13881784.49
#Sta/Elev= 30
  3601.4  100.15  4056.1   96.97  4427.5   95.43  4825.3  101.01  4870.1    95.3
  4904.6   95.81  4923.8    95.9  4941.3   91.44  4968.4   80.71  4980.7   79.61
  4986.6   76.69  5011.5   76.54  5024.4   78.89  5024.9   82.72  5037.7   82.04
  5080.8   95.65  5126.3   95.77  5388.6   96.65  5432.6   94.85  6018.6   98.63
  6342.7   99.25  6552.7   96.35  6582.7   99.35  6622.7   99.35  6672.7   97.35
  6872.7   98.15  6982.7   96.15  7202.7   98.05  7712.7   96.95  7897.9   98.75
#Mann= 9 ,-1 , 0
  3601.4     .05       0  4056.1     .12       0  4427.5     .08       0
  4904.6     .04       0  4923.8     .04       0  5080.8     .04       0
  5126.3     .12       0  5432.6     .08       0  6018.6     .99       0
#XS Ineff= 2 , 0
       0 4917.13   95.95 5087.47       0    95.4
Permanent Ineff=
       F       F
Bank Sta=4923.8,5080.8
XS Rating Curve= 0 ,0
Exp/Cntr=0.5,0.3