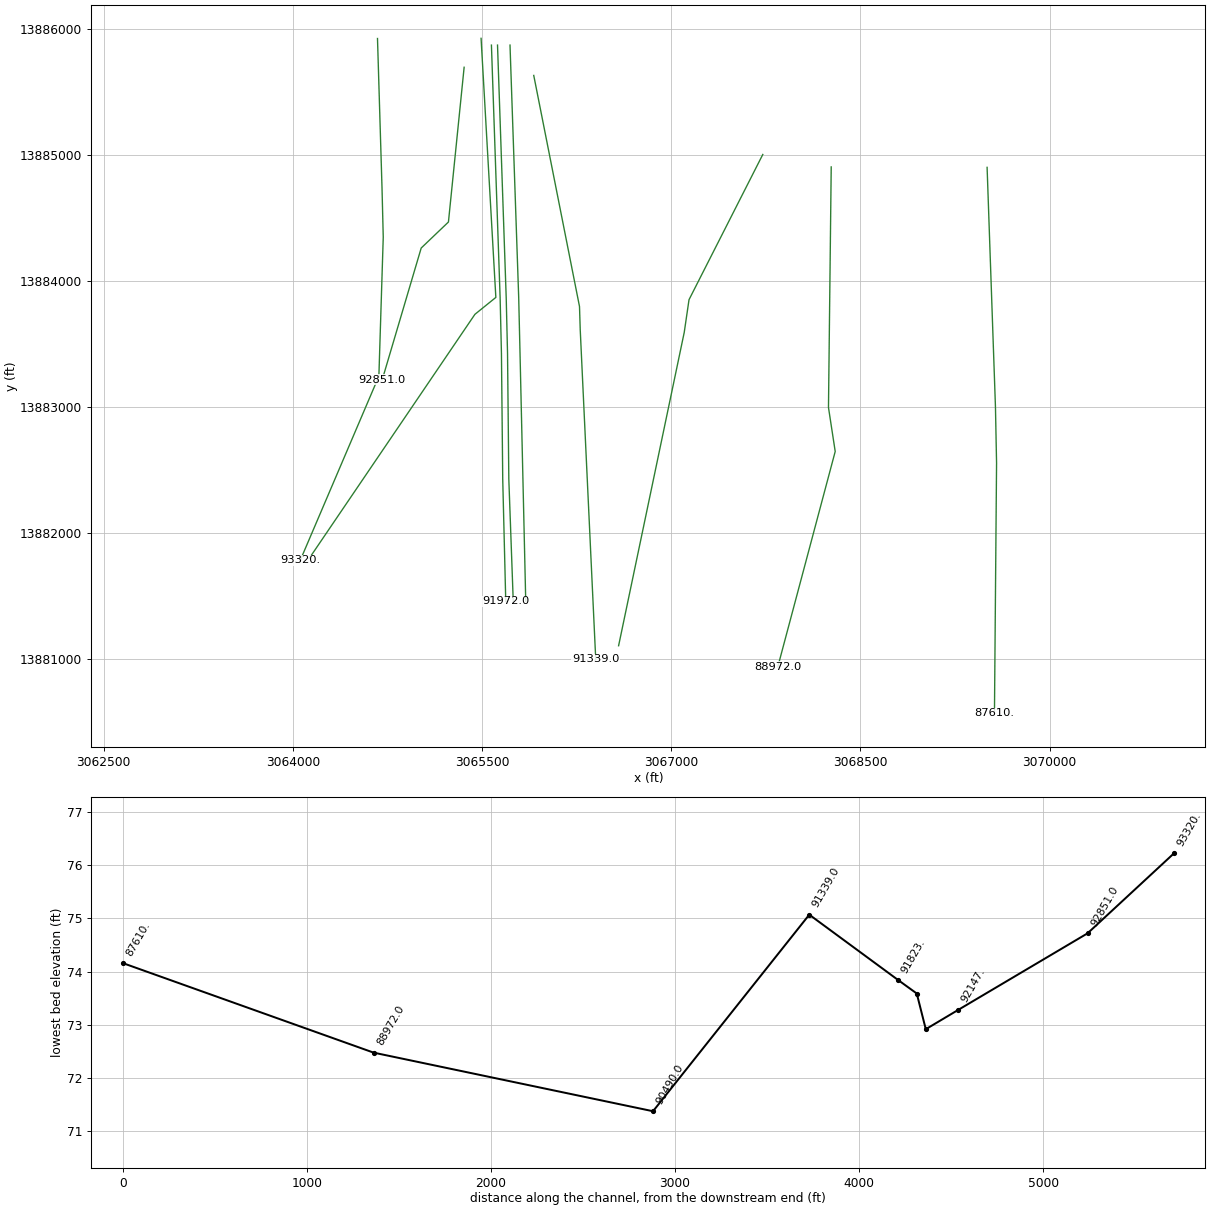
HEC-RAS study E100-00-00.prj: E100-00-00

--- E100-00-00.g02 (geometry) --- (continued)

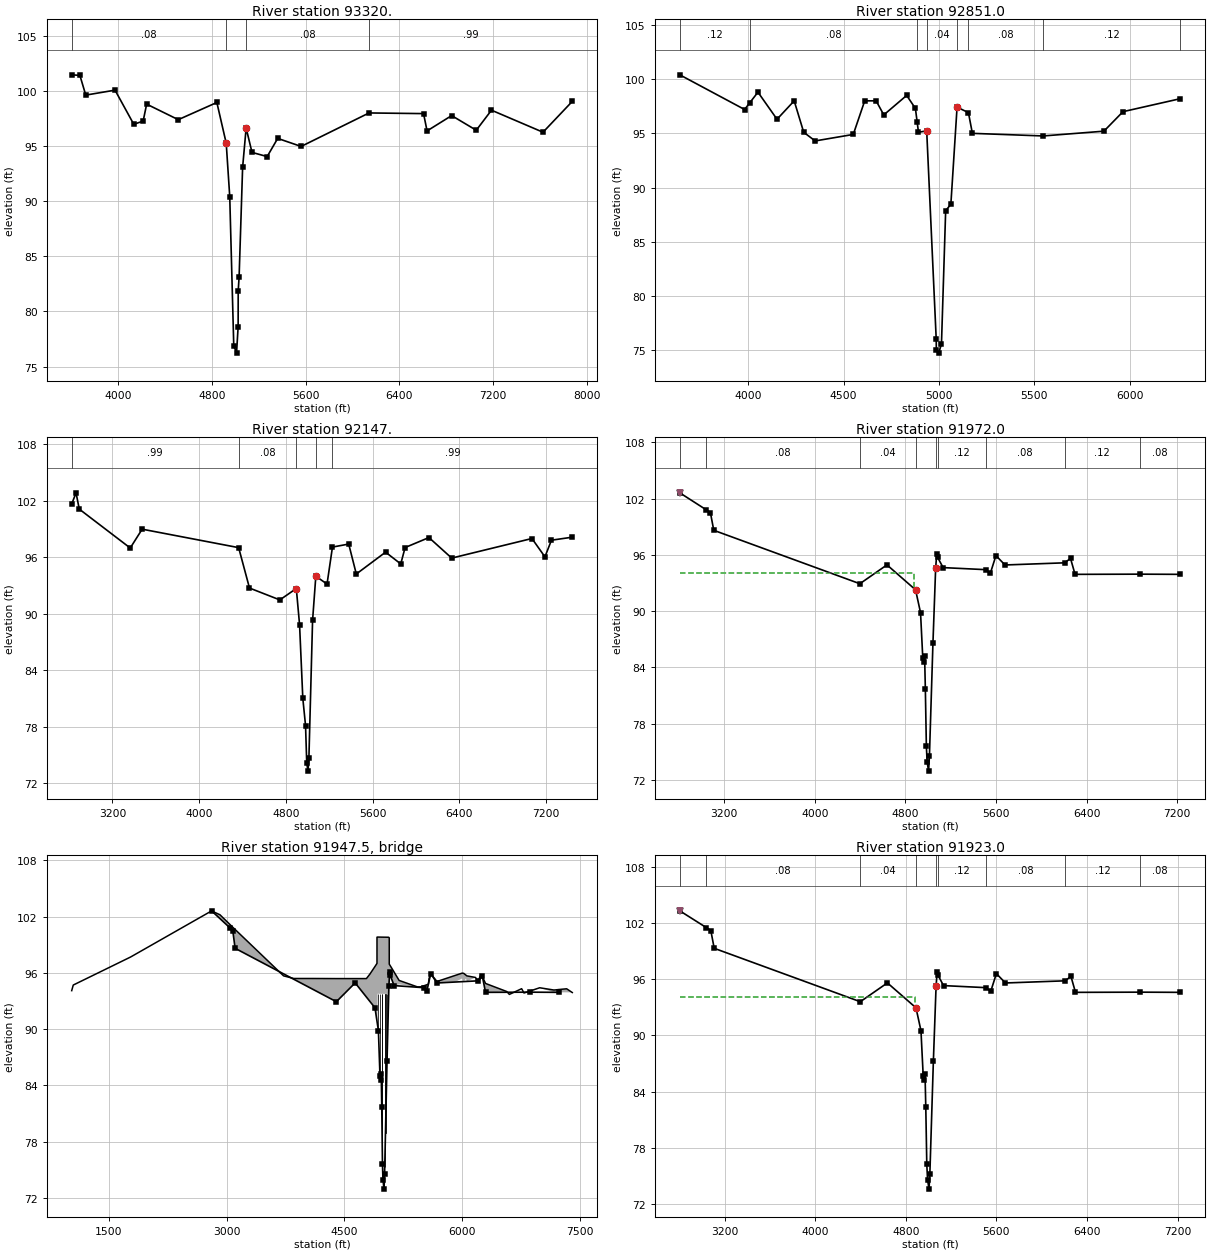
Type RM Length L Ch R = 1 ,93320.  ,544.8,469,238.7
BEGIN DESCRIPTION:
Gessner SB - D/S - XS 1
END DESCRIPTION:
XS GIS Cut Line= 5
        3064671.     13885927.38      3064706.88     13884738.54
      3064716.61     13884349.17      3064681.97     13883244.38
      3064058.74     13881781.66
#Sta/Elev= 30
  3601.9  101.48  3671.9  101.43  3721.9   99.64  3971.9  100.09  4131.9   96.99
  4211.9   97.28  4241.9   98.82  4511.9   97.41  4841.3   98.97  4921.3   95.27
  4951.3   90.43 4985.62   76.91 5009.29   76.22 5023.07   78.63  5023.6   81.86
  5031.3   83.14  5061.3   93.09  5091.3   96.65  5141.3   94.44  5270.8   94.06
  5360.8   95.71  5560.8   94.98  6140.8   98.02  6606.1   97.96  6636.1   96.39
  6846.1   97.78  7056.1   96.45  7186.1   98.27  7626.1   96.27  7876.1   99.07
#Mann= 4 ,-1 , 0
  3601.9     .08       0  4921.3     .04       0  5091.3     .08       0
  6140.8     .99       0
#XS Ineff= 2 , 0
       0    4840   98.94               0
Permanent Ineff=
       F       F
Bank Sta=4921.3,5091.3
XS Rating Curve= 0 ,0
Exp/Cntr=0.3,0.1

Type RM Length L Ch R = 1 ,92851.0 ,516.8,704,705
BEGIN DESCRIPTION:
Cross Section E100-00-00-X66
END DESCRIPTION:
XS GIS Cut Line= 4
      3065357.91      13885698.9      3065233.43     13884469.32
      3065017.51     13884262.74      3064708.54     13883216.26
#Sta/Elev= 30
  3640.9   100.4  3980.9    97.2  4006.6   97.79  4050.9    98.8  4150.9    96.3
  4240.9      98  4290.9    95.1  4350.9    94.3  4550.9    94.9  4610.9      98
  4670.9      98  4710.9    96.7  4830.9    98.5  4876.8    97.3  4886.1   96.03
  4892.9    95.1    4936   95.23  4985.9   76.03  4986.6   74.98  4998.8   74.72
  5013.5   75.57  5035.5   87.86  5062.8   88.46  5095.3   97.42  5154.9   96.91
  5175.6      95  5547.2   94.76  5865.6    95.2  5965.6      97  6266.7    98.2
#Mann= 8 ,-1 , 0
  3640.9     .12       0  4006.6     .08       0  4886.1     .04       0
    4936     .04       0  5095.3     .04       0  5154.9     .08       0
  5547.2     .12       0  6266.7     .99       0
#XS Ineff= 2 , 0
       0  4830.9    98.5               0
Permanent Ineff=
       F       F
Bank Sta=4936,5095.3
XS Rating Curve= 0 ,0
Exp/Cntr=0.3,0.1

Type RM Length L Ch R = 1 ,92147.  ,42.3,175,504.8
BEGIN DESCRIPTION:
Winfern - U/S - XS 4
END DESCRIPTION:
XS GIS Cut Line= 4
      3065492.22     13885928.76       3065609.3      13883870.2
      3065443.37     13883735.96      3064129.74      13881796.7
#Sta/Elev= 30
    2824  101.64    2864  102.83    2894   101.1    3364   96.97    3474   98.97
    4364   97.01    4464   92.72    4744   91.46  4895.9   92.67  4925.9   88.83
  4955.9      81 4981.02   78.12 4992.12   74.12 5003.77   73.28 5012.08   74.69
  5045.9   89.28  5075.9   93.98  5179.3   93.14  5229.3   97.07  5379.3   97.39
  5449.3   94.21  5719.3   96.53  5859.3   95.28  5899.3   97.02  6119.3   98.08
  6329.3    95.9  7069.3   97.98  7189.3   96.03  7249.3    97.8  7441.6   98.12
#Mann= 5 ,-1 , 0
    2824     .99       0    4364     .08       0  4895.9     .04       0
  5075.9     .08       0  5229.3     .99       0
Bank Sta=4895.9,5075.9
XS Rating Curve= 0 ,0
Exp/Cntr=0.5,0.3

Type RM Length L Ch R = 1 ,91972.0 ,48,49,52.4
BEGIN DESCRIPTION:
Upstream Section of Bridge/Culvert/Weir
ross section spills into E117-00-00, therefore extending the right overbank to contain the floodplain is not possible.  Also levee added on the left overbank to prevent shortening the cross section (real levee not present).
END DESCRIPTION:
XS GIS Cut Line= 5
      3065574.29     13885874.99      3065643.27     13883866.71
      3065653.71     13883424.68       3065663.9     13882426.24
      3065687.86     13881456.36
#Sta/Elev= 30
  2808.2  102.62  3037.6  100.84  3078.3  100.52  3108.3   98.62  4398.3   92.92
  4637.6   94.93    4890   92.27    4934   89.83  4953.8      85  4962.1   84.52
  4969.8   85.25  4976.5   81.72  4985.5   75.55  4992.2   73.94    5005   72.92
  5012.5   74.52  5043.5   86.56  5067.5   94.59  5076.7   96.05  5084.5   95.74
  5133.3   94.64  5509.9   94.42  5549.9   94.02  5599.9   95.92  5679.9   94.92
  6206.3   95.15  6258.4   95.62  6298.4   93.92  6868.7   93.94  7228.5   93.92
#Mann= 9 ,-1 , 0
  2808.2     .12       0  3037.6     .08       0  4398.3     .04       0
    4890     .04       0  5067.5     .04       0  5084.5     .12       0
  5509.9     .08       0  6206.3     .12       0  6868.7     .08       0
Levee=-1,2808.3,102.62,0,,,,
#XS Ineff= 2 , 0
       0    4880    94.1  5077.5       0    93.7
Permanent Ineff=
       F       F
Bank Sta=4890,5067.5
XS Rating Curve= 0 ,0
Exp/Cntr=0.5,0.3

Type RM Length L Ch R = 3 ,91947.5 ,,,
BEGIN DESCRIPTION:
WINFERN
Structure ID: E100-00-00-45
END DESCRIPTION:
Bridge Culvert--1,0,-1,-1, 0
Deck Dist Width WeirC Skew NumUp NumDn MinLoCord MaxHiCord MaxSubmerge Is_Ogee
10,29,2.6,0, 60, 58, , , 0.95, 0, ,,,
  1026.6  1046.6  1776.6  2808.3  2915.3  3078.3  3108.3  3725.3  3855.3  4078.3
  4388.3  4428.3  4637.6  4780.9  4824.6    4890 4915.59  4915.7 4923.51  4923.6
 5062.32 5062.43  5067.5  5071.9 5072.01  5076.7  5100.2  5133.3    5198  5431.8
  5469.9  5489.9  5519.9  5549.9  5569.9  5579.9  5599.9  5679.9  5909.9  5999.9
  6019.9  6049.9  6059.9  6169.9  6199.9  6206.3  6239.9  6258.4  6298.4  6568.4
  6588.4  6601.8  6758.4  6788.4  6988.4  7168.4  7188.4  7228.6  7331.8  7403.7
    94.1    94.7   97.69  102.61   102.2  100.87  100.63   95.68    95.4    95.4
   95.39   95.39   95.39   95.39   95.86   96.68   97.01   99.81   99.82   99.82
    99.8    99.8   99.78   99.73   96.93   96.87   96.55   96.09   95.19    94.5
   94.51   94.56   94.64   94.73   94.78   95.41   95.91   95.08   95.72   95.97
   95.95   95.75   95.68   95.51   95.19   95.17   95.81   95.61   94.87   94.01
   93.83    93.7   94.31   93.85   94.41   94.17   94.18   94.22    94.3    93.9
    94.1    94.2   97.68   102.6  101.77   100.5    98.6   95.67   95.06      94
      93    92.6   94.91   93.23   93.04   92.25   90.83   90.82   90.39   93.77
   93.75    93.1   94.57   95.27   95.29   96.03   95.09   94.62   94.77   94.49
    94.4      94    94.6      94    94.6    95.4    95.9    94.9    94.9    95.4
      95    95.4    94.8    95.5      95   95.13    95.8    95.6    93.9      94
    93.5   93.56    94.3    93.6    94.4    93.5    93.7    92.9   93.49    93.9
  1026.6  2808.3  3078.3  3108.3  3725.3  3855.3  4078.3  4388.3  4428.3  4637.6
  4780.9  4788.4  4824.6    4890 4915.59  4915.7 4923.51  4923.6 5062.32 5062.43
  5067.5  5071.9 5072.01  5076.7  5100.2  5133.3  5167.1    5198  5278.1  5469.9
  5489.9  5519.9  5549.9  5569.9  5579.9  5599.9  5679.9  5909.9  5999.9  6019.9
  6049.9  6059.9  6071.8  6169.9  6199.9  6239.9  6258.4  6298.4  6568.4  6588.4
  6758.4  6788.4  6988.4  7168.4  7188.4  7228.6  7331.8  7403.7
   94.76  103.26  101.16  100.63   96.33   95.72    95.4   95.39   95.39   95.57
   95.39   95.47   95.86   96.68   97.01   99.81   99.82   99.82    99.8    99.8
   99.78   99.73   96.93   96.87   96.55   96.09   95.62   95.43   95.51   95.06
   94.66   95.26   94.73   95.26   96.06   96.56   95.56   95.72   96.06   95.95
   96.06   95.68    95.6   96.16   95.66   96.46   96.26   94.87   94.66   94.16
   94.96   94.26   95.06   94.17   94.36   94.22    94.3   94.56
   94.76  103.26  101.16   99.26   96.33   95.72   94.66   93.66   93.26   95.57
   93.89    93.8    93.7   92.91   91.49   91.48   91.05   94.43   94.41   93.76
   95.23   95.93   95.95   96.69   95.75   95.28    95.4   95.43   95.51   95.06
   94.66   95.26   94.66   95.26   96.06   96.56   95.56   95.56   96.06   95.66
   96.06   95.46   95.54   96.16   95.66   96.46   96.26   94.56   94.66   94.16
   94.96   94.26   95.06   94.16   94.36   93.56   94.15   94.56
Pier Skew, UpSta & Num, DnSta & Num=  ,4934, 2 ,4934, 2 , 0 , 0 , 0 ,,
     1.3     1.3
   88.55   94.77
     1.3     1.3
   89.21   95.43
Pier Skew, UpSta & Num, DnSta & Num=  ,4953.8, 2 ,4953.8, 2 , 0 , 0 , 0 ,,
     1.3     1.3
   83.94   94.77
     1.3     1.3
    84.6   95.43
Pier Skew, UpSta & Num, DnSta & Num=  ,4980, 2 ,4980, 2 , 0 , 0 , 0 ,,
     1.3     1.3
   77.23   94.76
     1.3     1.3
   77.89   95.42
Pier Skew, UpSta & Num, DnSta & Num=  ,4984.1, 2 ,4984.1, 2 , 0 , 0 , 0 ,,
     1.3     1.3
   75.06   94.76
     1.3     1.3
   75.72   95.42
Pier Skew, UpSta & Num, DnSta & Num=  ,5014.5, 2 ,5014.5, 2 , 0 , 0 , 0 ,,
     1.3     1.3
   74.28   94.76
     1.3     1.3
   74.94   95.42
Pier Skew, UpSta & Num, DnSta & Num=  ,5023.9, 2 ,5023.9, 2 , 0 , 0 , 0 ,,
     1.3     1.3
   77.48   94.76
     1.3     1.3
   78.14   95.42
Pier Skew, UpSta & Num, DnSta & Num=  ,5044.7, 2 ,5044.7, 2 , 0 , 0 , 0 ,,
     1.3     1.3
   85.73   94.75
     1.3     1.3
   86.39   95.41
BR Coef= 1 , 1 , 0 ,1.25, 0 ,,,0.8,0,2,0,
WSPro=,,,, 1 ,,,, 0 ,,,, 0 ,,,,-1 ,-1 ,-1 , 0 , 0 , 0 , 0 , 0
BC Design=,, 0 ,, 0 ,,,,,,
BC HTab HWMax=102.62
BC Use User HTab Curves=0
BC User HTab FreeFlow(D)= 0

Type RM Length L Ch R = 1 ,91923.0 ,99,100,111.9
BEGIN DESCRIPTION:
Downstream Section of Bridge/Culvert/Weir
Cross section spills into E117-00-00, therefore extending the right overbank to contain the floodplain is not possible.  Also levee added on the left overbank to prevent shortening the cross section (real levee not present).
END DESCRIPTION:
XS GIS Cut Line= 5
      3065622.53     13885875.12      3065691.52     13883866.68
      3065701.97     13883424.29      3065712.16     13882426.04
      3065747.23     13881456.83
#Sta/Elev= 30
  2804.4  103.29  3037.6  101.51  3078.3  101.19  3108.3   99.29  4398.3   93.59
  4637.6    95.6    4890   92.94    4934    90.5  4953.8   85.67  4962.1   85.19
  4969.8   85.92  4976.5   82.39  4985.5   76.22  4992.2   74.61    5005   73.59
  5012.5   75.19  5043.5   87.23  5067.5   95.26  5076.7   96.72  5084.5   96.41
  5133.3   95.31  5509.9   95.09  5549.9   94.69  5599.9   96.59  5679.9   95.59
  6206.3   95.82  6258.4   96.29  6298.4   94.59  6868.7   94.61  7224.7   94.59
#Mann= 9 ,-1 , 0
  2804.4     .12       0  3037.6     .08       0  4398.3     .04       0
    4890     .04       0  5067.5     .04       0  5084.5     .12       0
  5509.9     .08       0  6206.3     .12       0  6868.7     .08       0
Levee=-1,2808.3,103.29,0,,,,
#XS Ineff= 2 , 0
       0 4883.33    94.1 5074.17       0    93.7
Permanent Ineff=
       F       F
Bank Sta=4890,5067.5
XS Rating Curve= 0 ,0
Exp/Cntr=0.5,0.3

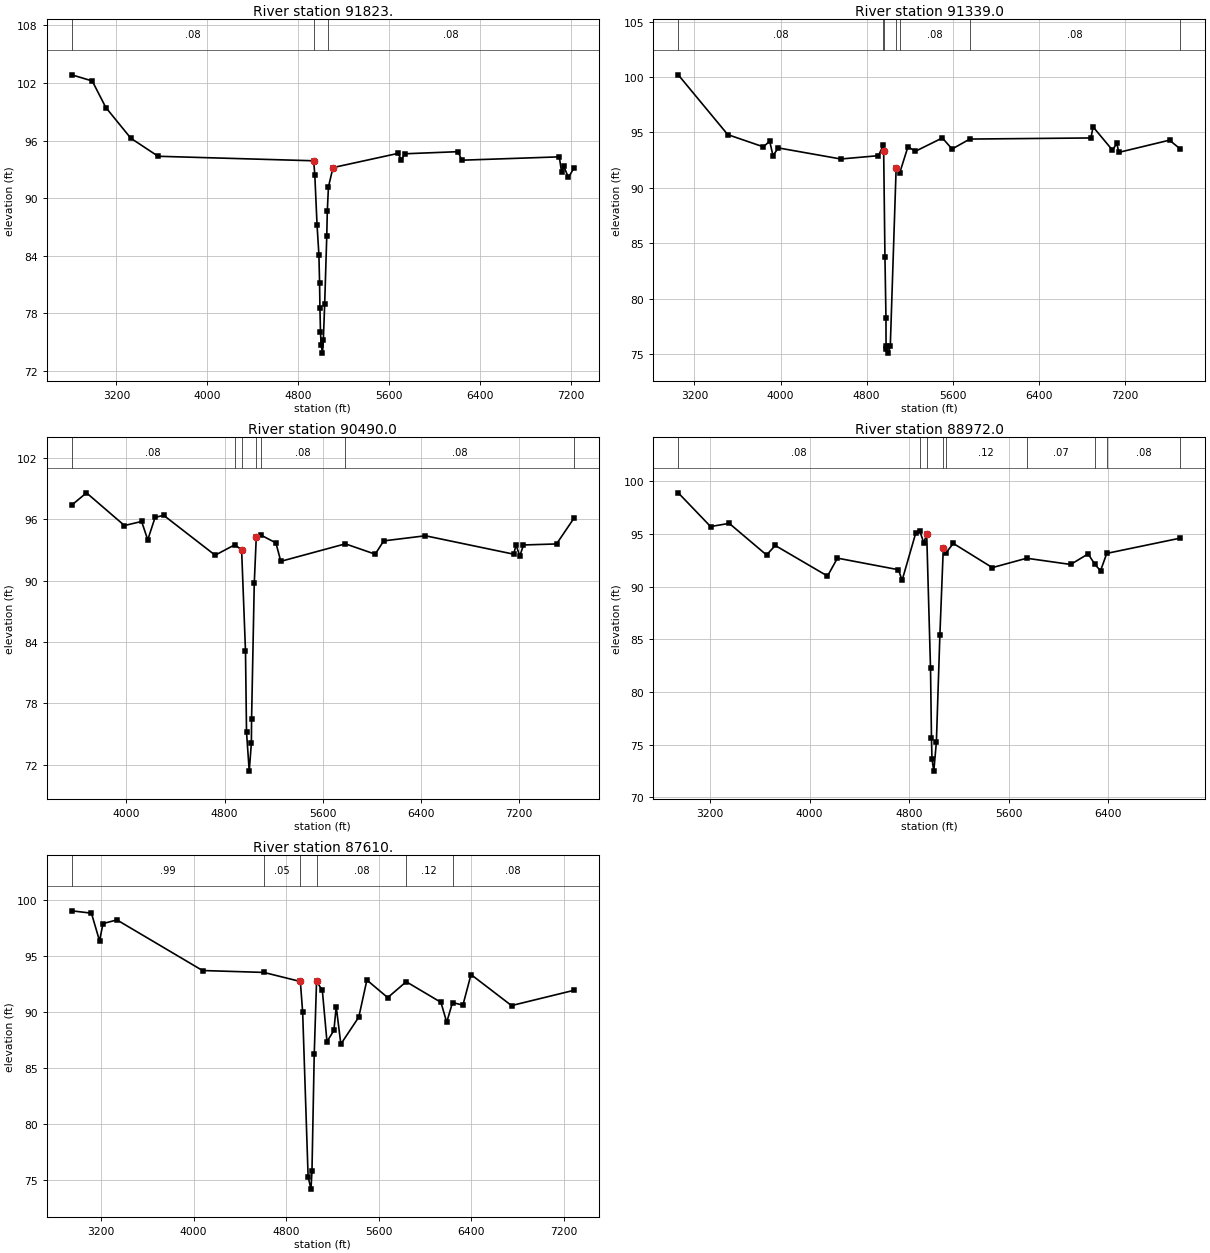
Type RM Length L Ch R = 1 ,91823.  ,468.9,484,521.4
BEGIN DESCRIPTION:
Winfern - D/S - XS 1
END DESCRIPTION:
XS GIS Cut Line= 4
      3065721.58     13885875.12      3065790.57     13883866.68
      3065801.02     13883424.29      3065846.28     13881456.83
#Sta/Elev= 30
  2807.4  102.85  2987.4  102.21  3107.4   99.44  3327.4   96.24  3567.4   94.36
    4937   93.89    4947    92.4    4967   87.15    4983    84.1 4988.99   81.17
 4992.11   78.55 4997.03   76.04 5003.01    74.7 5014.45   73.84 5022.15   75.22
 5033.86   78.93 5052.36   86.09    5057   88.63    5067   91.16    5107   93.18
  5679.5   94.66  5709.5   93.99  5739.5   94.62  6209.5   94.84  6239.5   93.95
  7099.5    94.3  7119.5   92.72  7139.5    93.3  7179.5   92.15  7227.5   93.11
#Mann= 3 ,-1 , 0
  2807.4     .08       0    4937     .04       0    5067     .08       0
Bank Sta=4937,5107
XS Rating Curve= 0 ,0
Exp/Cntr=0.3,0.1

Type RM Length L Ch R = 1 ,91339.0 ,953.4,849,650.3
BEGIN DESCRIPTION:
Cross Section E100-00-00-X65
Cross section spills into E117-00-00, therefore extending the right overbank to contain the floodplain is not possible.
END DESCRIPTION:
XS GIS Cut Line= 4
      3065909.82     13885633.97      3066272.57     13883797.92
      3066278.19     13883615.75      3066401.21     13880995.65
#Sta/Elev= 30
  3049.8   100.2  3509.8    94.8  3839.8    93.7  3899.8    94.2  3929.8    92.9
  3979.8    93.6  4559.8    92.6  4909.8    92.9  4954.4   93.83  4958.3   93.29
  4970.1   83.78  4979.6   78.24  4980.3   75.75  4980.6   75.41  5001.8   75.07
  5019.7    75.7  5074.1   91.77  5108.5   91.38  5183.6    93.7  5253.6    93.3
  5503.6    94.5  5593.6    93.5  5758.2    94.4  6883.6    94.5  6903.6    95.5
  7083.6    93.4  7123.6      94  7143.6    93.2  7613.6    94.3    7714    93.5
#Mann= 7 ,-1 , 0
  3049.8     .08       0  4954.4     .04       0  4958.3     .04       0
  5074.1     .04       0  5108.5     .08       0  5758.2     .08       0
    7714     .99       0
Bank Sta=4958.3,5074.1
XS Rating Curve= 0 ,0
Exp/Cntr=0.3,0.1

Type RM Length L Ch R = 1 ,90490.0 ,1238.2,1518,1519
BEGIN DESCRIPTION:
Cross Section E100-00-00-X64
Cross section spills into E117-00-00, therefore extending the right overbank to contain the floodplain is not possible.
END DESCRIPTION:
XS GIS Cut Line= 4
      3067725.73     13885005.98      3067140.86     13883852.33
      3067102.97     13883592.86      3066582.52     13881102.65
#Sta/Elev= 30
  3553.7    97.4  3673.7    98.6  3983.7    95.4  4123.7    95.8  4173.7      94
  4233.7    96.2  4303.7    96.4  4723.7    92.5  4884.3   93.52  4939.7   93.01
  4971.3    83.1  4979.6   75.21  5001.7   71.38  5019.3   74.12  5020.9   76.45
  5042.8   89.74  5059.3   94.29    5094   94.49  5219.4    93.7  5259.4    91.9
  5786.2   93.61  6029.4    92.6  6099.4    93.9  6439.4    94.4  7159.4    92.6
  7179.4    93.5  7209.4    92.4  7239.4    93.5  7509.4    93.6  7650.6    96.1
#Mann= 7 ,-1 , 0
  3553.7     .08       0  4884.3     .04       0  4939.7     .04       0
  5059.3     .04       0    5094     .08       0  5786.2     .08       0
  7650.6     .99       0
Bank Sta=4939.7,5059.3
XS Rating Curve= 0 ,0
Exp/Cntr=0.3,0.1

Type RM Length L Ch R = 1 ,88972.0 ,1361,1362,1431.1
BEGIN DESCRIPTION:
Cross Section E100-00-00-X63
Cross section spills into E117-00-00, therefore extending the right overbank to contain the floodplain is not possible.
END DESCRIPTION:
XS GIS Cut Line= 4
      3068268.19     13884906.99      3068246.48     13882995.84
      3068299.86     13882646.09      3067844.46      13880934.2
#Sta/Elev= 30
  2943.9    98.9  3203.9    95.7  3353.9      96  3653.9      93  3723.9    93.9
  4143.9      91  4223.9    92.7  4713.9    91.6  4743.9    90.6  4853.9    95.1
  4885.2    95.3  4918.4   94.14  4941.5   94.99  4972.2   82.23  4979.8   75.64
  4983.8   73.66  4998.6   72.48  5019.4   75.27  5047.3   85.36  5074.9   93.67
  5096.1   93.19  5155.2    94.1    5469    91.8  5745.1   92.69    6099    92.1
    6239    93.1  6294.3    92.1    6339    91.5  6389.1   93.15  6980.4    94.6
#Mann= 9 ,-1 , 0
  2943.9     .08       0  4885.2     .04       0  4941.5     .04       0
  5074.9     .04       0  5096.1     .12       0  5745.1     .07       0
  6294.3      .1       0  6389.1     .08       0  6980.4     .99       0
Bank Sta=4941.5,5074.9
XS Rating Curve= 0 ,0
Exp/Cntr=0.3,0.1

Type RM Length L Ch R = 1 ,87610.  ,101,102,110.5
BEGIN DESCRIPTION:
Fairbanks N-Houston SB - U/S - XS 4
END DESCRIPTION:
XS GIS Cut Line= 4
      3069504.06     13884903.61      3069570.36     13882999.07
      3069579.09     13882554.03      3069562.36     13880565.37
#Sta/Elev= 30
  2946.8   99.01  3116.8    98.8  3186.8   96.33  3216.8   97.87  3336.8    98.2
  4076.8   93.68  4606.8   93.51  4922.5    92.7  4942.5   89.94 4989.51   75.28
 5014.39   74.16  5022.9   75.77  5042.5    86.2  5062.5   92.71  5112.5   91.91
  5152.5   87.33  5212.5   88.33  5232.5   90.46  5272.5   87.11  5427.6   89.52
  5497.6   92.83  5677.6   91.26  5837.6   92.68  6137.6   90.84  6187.6   89.06
  6237.6   90.82  6327.6   90.59  6397.6   93.32  6747.6   90.55  7286.4   91.91
#Mann= 6 ,-1 , 0
  2946.8     .99       0  4606.8     .05       0  4922.5     .04       0
  5062.5     .08       0  5837.6     .12       0  6237.6     .08       0
Bank Sta=4922.5,5062.5
XS Rating Curve= 0 ,0
Exp/Cntr=0.5,0.3