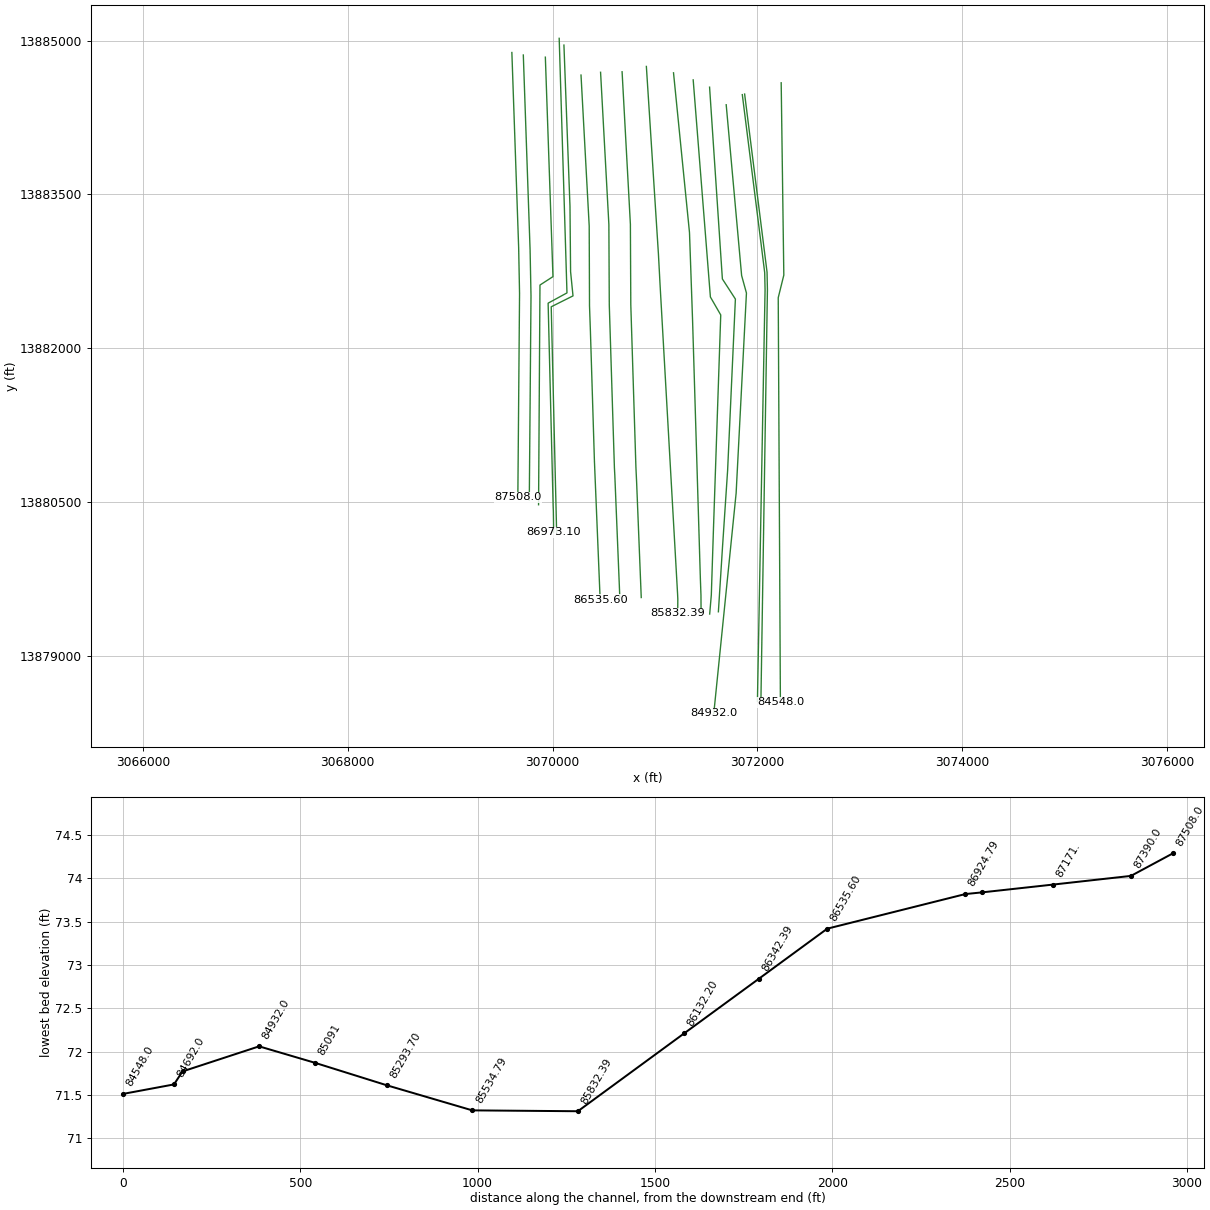
HEC-RAS study E100-00-00.prj: E100-00-00

--- E100-00-00.g02 (geometry) --- (continued)

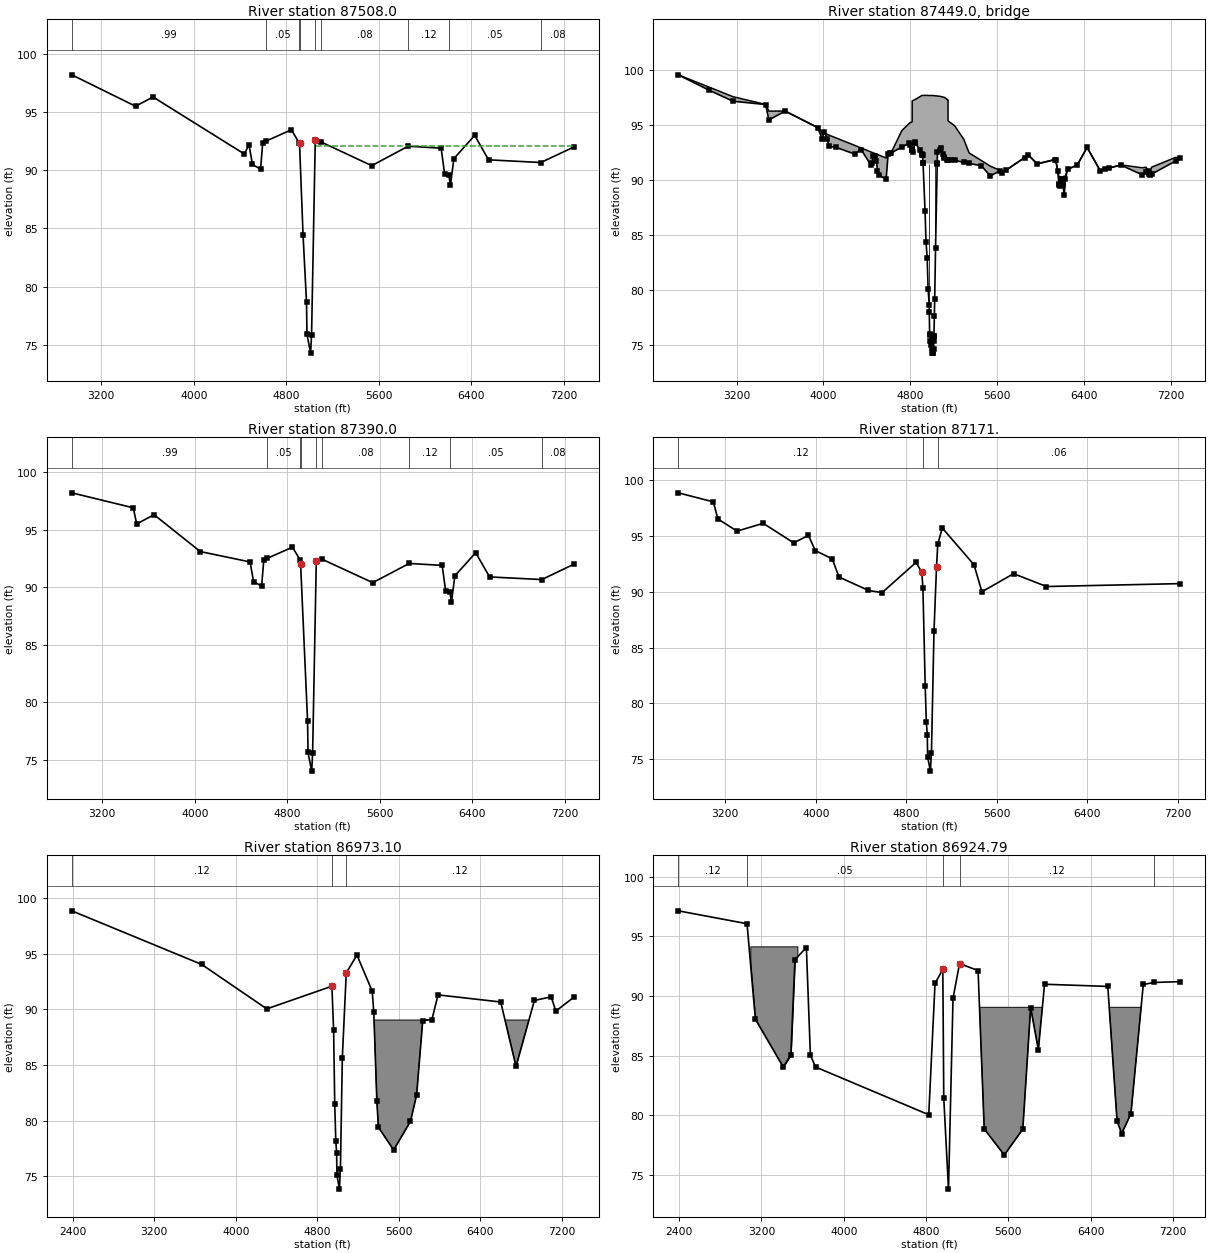
Type RM Length L Ch R = 1 ,87508.0 ,112.8,118,124.6
BEGIN DESCRIPTION:
Upstream Section of Bridge/Culvert/Weir
Cross section spills into E117-00-00, therefore extending the right overbank to contain the floodplain is not possible.
END DESCRIPTION:
XS GIS Cut Line= 4
      3069603.11      13884883.8      3069669.41     13882979.26
      3069678.13     13882534.22      3069661.41     13880545.56
#Sta/Elev= 30
  2945.6   98.19  3497.4   95.49  3647.4   96.29  4437.4   91.39  4477.4   92.19
  4507.4   90.49  4577.4   90.09    4596   92.35  4622.8   92.49  4843.8   93.47
  4912.3   92.33  4914.2    92.3  4944.8    84.4  4974.6   78.65  4978.5   75.91
  5010.2   74.29  5018.2   75.86  5050.1   92.56  5099.1   92.43  5538.2   90.39
  5853.1   92.06  6138.2   91.89  6168.2   89.69    6205   89.61  6218.2   88.69
  6248.2   90.99  6428.2   92.99  6548.2   90.89  6999.5   90.66  7285.2   91.99
#Mann= 9 ,-1 , 0
  2945.6     .99       0  4622.8     .05       0  4912.3     .04       0
  4914.2     .04       0  5050.1     .04       0  5099.1     .08       0
  5853.1     .12       0    6205     .05       0  6999.5     .08       0
#XS Ineff= 2 , 0
       0  4908.1    92.1  5057.8       0    92.1
Permanent Ineff=
       F       F
Bank Sta=4914.2,5050.1
XS Rating Curve= 0 ,0
Exp/Cntr=0.5,0.3

Type RM Length L Ch R = 3 ,87449.0 ,,,
BEGIN DESCRIPTION:
FAIRBANKS N-HOUSTON
Structure ID: E100-00-00-44
END DESCRIPTION:
Bridge Culvert--1,0,-1,-1, 0
Deck Dist Width WeirC Skew NumUp NumDn MinLoCord MaxHiCord MaxSubmerge Is_Ogee
10,98,2.6,0, 112, 112, , , 0.95, 0, ,,,
  2662.9  2947.4  3167.4  3467.4  3497.4  3647.4  3947.4  3987.4  4007.4  4037.4
  4047.4  4117.4  4287.4  4347.4  4437.4  4447.4  4457.4  4477.4  4487.4  4497.4
  4507.4  4577.4    4596  4612.9  4622.8  4722.4  4787.7  4793.7 4817.39  4817.5
 4817.61  4826.1  4842.7  4843.8  4885.1  4908.1  4912.3  4914.2 4917.31  4917.4
    4936  4944.8  4955.9  4963.9  4974.6  4974.9  4978.5  4983.1  4984.6    4991
  4997.2  5003.7  5007.7  5010.2  5014.1  5015.4  5016.4  5018.2  5021.7  5024.8
  5032.8 5047.99  5048.1  5050.1  5073.2  5084.1  5099.1  5108.8  5114.8    5139
 5147.69  5147.8 5147.91  5173.1  5208.6  5292.9    5342  5454.4  5538.2  5628.2
  5648.2    5682  5853.1  5888.2  5968.2    6132  6138.2  6158.2  6168.2    6172
  6178.2  6188.2  6198.2    6205  6218.2  6228.2  6248.2  6338.2  6428.2  6548.2
    6592    6632  6738.2  6938.2    6972  6988.2  6999.5    7002  7008.2    7022
  7244.9    7287
    99.6   98.48   97.61   96.91    96.3   96.31   94.81   94.37   94.41   94.17
   94.13   93.86   93.19   92.95   92.59   92.55   92.51   92.44    92.4   92.36
   92.32   92.04   92.37   92.46   92.51   94.53   95.16   95.22   95.33   97.23
   97.23   97.27   97.34   97.35   97.59   97.73   97.73   97.73   97.73   97.73
   97.73   97.73   97.73   97.72   97.72   97.72   97.72   97.72   97.72   97.72
   97.72   97.72   97.72   97.72   97.71   97.71   97.71   97.71   97.71    97.7
   97.69   97.68   97.68   97.67   97.65   97.62   97.59   97.56   97.55   97.37
   97.31   97.31   95.41   95.23   94.97   93.74    92.5   91.81   91.29   90.91
   90.71   90.94   92.08   92.31   91.51    91.9   91.91   90.91    90.4    90.3
   90.31   90.32   90.34   90.35   90.37   90.38   91.01   91.41   93.01   90.91
   91.03   91.13   91.41   91.15    91.2   90.91   90.68   90.63   90.65    91.2
    92.1      92
                                                                                
                                                                                
                                                                                
                                                                           91.57
   91.53   91.53   91.53   91.52   91.52   91.52   91.52   91.52   91.52   91.52
   91.52   91.52   91.52   91.52   91.51   91.51   91.51   91.51   91.51    91.5
   91.49   91.51
                                                                                
                                                                                
                                                                                
                                                                                
                
  2662.9  2947.4  3167.4  3467.4  3497.4  3647.4  3947.4  3987.4  4007.4  4037.4
  4047.4  4117.4  4287.4  4347.4  4437.4  4447.4  4457.4  4477.4  4487.4  4497.4
  4507.4  4577.4    4596  4612.9  4622.8  4722.4  4787.7  4793.7 4817.39  4817.5
 4817.61  4826.1  4842.7  4843.8  4885.1  4908.1  4912.3  4914.2 4917.31  4917.4
    4936  4944.8  4955.9  4963.9  4974.6  4974.9  4978.5  4983.1  4984.6    4991
  4997.2  5003.7  5007.7  5010.2  5014.1  5015.4  5016.4  5018.2  5021.7  5024.8
  5032.8 5047.99  5048.1  5050.1  5073.2  5084.1  5099.1  5108.8  5114.8    5139
 5147.69  5147.8 5147.91  5173.1  5208.6  5292.9    5342  5454.4  5538.2  5628.2
  5648.2    5682  5853.1  5888.2  5968.2    6132  6138.2  6158.2  6168.2    6172
  6178.2  6188.2  6198.2    6205  6218.2  6228.2  6248.2  6338.2  6428.2  6548.2
    6592    6632  6738.2  6938.2    6972  6988.2  6999.5    7002  7008.2    7022
  7244.9    7287
    99.6   98.48   97.61   96.91    96.3   96.31   94.81   94.37   94.41   94.17
   94.13   93.86   93.19   92.95   92.59   92.55   92.51   92.44    92.4   92.36
   92.32   92.04   92.37   92.46   92.51   94.53   95.16   95.22   95.33   97.23
   97.23   97.27   97.34   97.35   97.59   97.73   97.73   97.73   97.73   97.73
   97.73   97.73   97.73   97.72   97.72   97.72   97.72   97.72   97.72   97.72
   97.72   97.72   97.72   97.72   97.71   97.71   97.71   97.71   97.71    97.7
   97.69   97.68   97.68   97.67   97.65   97.62   97.59   97.56   97.55   97.37
   97.31   97.31   95.41   95.23   94.97   93.74    92.5   91.81   91.29   90.91
   90.71   90.94   92.08   92.31   91.51    91.9   91.91   90.91    90.4    90.3
   90.31   90.32   90.34   90.35   90.37   90.38   91.01   91.41   93.01   90.91
   91.03   91.13   91.41   91.15    91.2   90.91   90.68   90.63   90.65    91.2
    92.1      92
                                                                                
                                                                                
                                                                                
                                                                           91.57
   91.53   91.53   91.53   91.52   91.52   91.52   91.52   91.52   91.52   91.52
   91.52   91.52   91.52   91.52   91.51   91.51   91.51   91.51   91.51    91.5
   91.49   91.51
                                                                                
                                                                                
                                                                                
                                                                                
                
Pier Skew, UpSta & Num, DnSta & Num=  ,4974.9, 2 ,4974.9, 2 , 0 , 0 , 0 ,,
     1.5     1.5
   76.61   92.52
     1.5     1.5
   76.34   92.25
Pier Skew, UpSta & Num, DnSta & Num=  ,5029.8, 2 ,5029.8, 2 , 0 , 0 , 0 ,,
     1.5     1.5
   80.68   92.49
     1.5     1.5
   80.41   92.22
BR Coef= 1 , 1 , 0 ,1.25, 0 ,,,0.8,0,2,0,
WSPro=,,,, 1 ,,,, 0 ,,,, 0 ,,,,-1 ,-1 ,-1 , 0 , 0 , 0 , 0 , 0
BR U #Sta/Elev= 112
  2662.9    99.6  2947.4    98.2  3167.4    97.2  3467.4    96.9  3497.4    95.5
  3647.4    96.3  3947.4    94.8  3987.4    93.8  4007.4    94.4  4037.4    93.8
  4047.4    93.1  4117.4      93  4287.4    92.4  4347.4    92.8  4437.4    91.4
  4447.4    91.6  4457.4    92.2  4477.4    92.2  4487.4    91.8  4497.4    90.9
  4507.4    90.5  4577.4    90.1    4596   92.36  4612.9   92.45  4622.8    92.5
  4722.4   93.03  4787.7   93.37  4793.7   93.25 4817.39   92.79  4817.5   92.79
 4817.61   92.79  4826.1   92.62  4842.7   93.43  4843.8   93.48  4885.1   92.81
  4908.1   92.41  4912.3   92.34  4914.2   92.31 4917.31   91.59  4917.4   91.57
    4936   87.24  4944.8   84.41  4955.9   82.94  4963.9   80.17  4974.6   78.66
  4974.9   78.06  4978.5   75.92  4983.1   76.07  4984.6    75.4    4991   75.07
  4997.2   74.75  5003.7   74.32  5007.7   74.31  5010.2    74.3  5014.1   74.65
  5015.4   75.42  5016.4    75.9  5018.2   75.87  5021.7   77.72  5024.8   79.19
  5032.8   83.88 5047.99   91.51  5048.1   91.57  5050.1   92.57  5073.2   92.81
  5084.1   92.92  5099.1   92.44  5108.8   92.13  5114.8   92.07    5139   91.83
 5147.69   91.85  5147.8   91.85 5147.91   91.85  5173.1   91.89  5208.6   91.82
  5292.9   91.65    5342   91.55  5454.4   91.33  5538.2    90.4  5628.2    90.9
  5648.2    90.7    5682   90.93  5853.1   92.07  5888.2    92.3  5968.2    91.5
    6132   91.89  6138.2    91.9  6158.2    90.9  6168.2    89.7    6172   89.62
  6178.2    89.5  6188.2    90.1  6198.2    90.1    6205   89.62  6218.2    88.7
  6228.2    90.1  6248.2      91  6338.2    91.4  6428.2      93  6548.2    90.9
    6592   91.02    6632   91.12  6738.2    91.4  6938.2    90.5    6972   90.77
  6988.2    90.9  6999.5   90.67    7002   90.62  7008.2    90.5    7022   90.57
  7244.9   91.77    7287      92
BR U #Mann= 9
  2662.9     .99  4622.8     .05  4912.3     .04  4914.2     .04  5050.1     .04
  5099.1     .08  5853.1     .12    6205     .05  6999.5     .08
BR U Banks=4914.2,5050.1
BR D #Sta/Elev= 112
  2662.9    99.6  2947.4    98.2  3167.4    97.2  3467.4    96.9  3497.4    95.5
  3647.4    96.3  3947.4    94.8  3987.4    93.8  4007.4    94.4  4037.4    93.8
  4047.4    93.1  4117.4      93  4287.4    92.4  4347.4    92.8  4437.4    91.4
  4447.4    91.6  4457.4    92.2  4477.4    92.2  4487.4    91.8  4497.4    90.9
  4507.4    90.5  4577.4    90.1    4596   92.36  4612.9   92.45  4622.8    92.5
  4722.4   93.03  4787.7   93.37  4793.7   93.25 4817.39   92.79  4817.5   92.79
 4817.61   92.79  4826.1   92.62  4842.7   93.43  4843.8   93.48  4885.1   92.81
  4908.1   92.41  4912.3   92.34  4914.2   92.04 4917.31   91.32  4917.4    91.3
    4936   86.97  4944.8   84.14  4955.9   82.67  4963.9    79.9  4974.6   78.39
  4974.9   77.79  4978.5   75.65  4983.1    75.8  4984.6   75.13    4991    74.8
  4997.2   74.48  5003.7   74.05  5007.7   74.04  5010.2   74.03  5014.1   74.38
  5015.4   75.15  5016.4   75.63  5018.2    75.6  5021.7   77.45  5024.8   78.92
  5032.8   83.61 5047.99   91.24  5048.1    91.3  5050.1    92.3  5073.2   92.81
  5084.1   92.92  5099.1   92.44  5108.8   92.13  5114.8   92.07    5139   91.83
 5147.69   91.85  5147.8   91.85 5147.91   91.85  5173.1   91.89  5208.6   91.82
  5292.9   91.65    5342   91.55  5454.4   91.33  5538.2    90.4  5628.2    90.9
  5648.2    90.7    5682   90.93  5853.1   92.07  5888.2    92.3  5968.2    91.5
    6132   91.89  6138.2    91.9  6158.2    90.9  6168.2    89.7    6172   89.62
  6178.2    89.5  6188.2    90.1  6198.2    90.1    6205   89.62  6218.2    88.7
  6228.2    90.1  6248.2      91  6338.2    91.4  6428.2      93  6548.2    90.9
    6592   91.02    6632   91.12  6738.2    91.4  6938.2    90.5    6972   90.77
  6988.2    90.9  6999.5   90.67    7002   90.62  7008.2    90.5    7022   90.57
  7244.9   91.77    7287      92
BR D #Mann= 9
  2662.9     .99  4622.8     .05  4912.3     .04  4914.2     .04  5050.1     .04
  5099.1     .08  5853.1     .12    6205     .05  6999.5     .08
BR D Banks=4914.2,5050.1
BC Design=,, 0 ,, 0 ,,,,,,
BC HTab HWMax=99.59
BC Use User HTab Curves=0
BC User HTab FreeFlow(D)= 0

Type RM Length L Ch R = 1 ,87390.0 ,220,219,98.5
BEGIN DESCRIPTION:
Downstream Section of Bridge/Culvert/Weir
Cross section spills into E117-00-00, therefore extending the right overbank to contain the floodplain is not possible.
END DESCRIPTION:
XS GIS Cut Line= 4
      3069714.81     13884859.48      3069781.12     13882954.72
      3069789.86     13882509.02      3069773.12     13880519.94
#Sta/Elev= 30
  2935.9   98.19  3467.4   96.89  3497.4   95.49  3647.4   96.29  4047.4   93.09
  4477.4   92.19  4507.4   90.49  4577.4   90.09    4596   92.35  4622.8   92.49
  4843.8   93.47  4912.3   92.33  4914.2   92.04  4974.6   78.39  4978.5   75.65
  5010.2   74.03  5018.2    75.6  5050.1    92.3  5099.1   92.43  5538.2   90.39
  5853.1   92.06  6138.2   91.89  6168.2   89.69    6205   89.61  6218.2   88.69
  6248.2   90.99  6428.2   92.99  6548.2   90.89  6999.5   90.66  7276.7   91.99
#Mann= 9 ,-1 , 0
  2935.9     .99       0  4622.8     .05       0  4912.3     .04       0
  4914.2     .04       0  5050.1     .04       0  5099.1     .08       0
  5853.1     .12       0    6205     .05       0  6999.5     .08       0
#XS Ineff= 2 , 0
       0  4908.1    91.4  5057.8       0    91.4
Permanent Ineff=
       F       F
Bank Sta=4914.2,5050.1
XS Rating Curve= 0 ,0
Exp/Cntr=0.5,0.3

Type RM Length L Ch R = 1 ,87171.  ,143.5,199.8,126
BEGIN DESCRIPTION:
Fairbanks N-Houston SB - D/S - XS 1
END DESCRIPTION:
XS GIS Cut Line= 4
      3069929.89     13884838.36      3070004.27     13882698.69
      3069877.42     13882616.67      3069863.68     13880474.66
#Sta/Elev= 30
    2786   98.85    3096   98.04    3136   96.51    3306   95.42    3536   96.12
    3806   94.37    3936   95.04    3996   93.68    4146   92.94    4206   91.31
    4466   90.11    4586   89.91    4886   92.62    4937   91.74    4947   90.33
    4967   81.55 4977.31    78.3 4985.55   77.18 4988.55    75.2 5012.95   73.93
 5022.29   75.58 5044.77   86.49    5067   92.19    5078   94.26    5118    95.7
    5398   92.41    5468   89.99    5748   91.61    6038   90.46  7220.1   90.72
#Mann= 3 ,-1 , 0
    2786     .12       0    4947     .04       0    5078     .06       0
Bank Sta=4937,5067
XS Rating Curve= 0 ,0
Exp/Cntr=0.6,0.4

Type RM Length L Ch R = 1 ,86973.10,55.7,48.2,34.7
BEGIN DESCRIPTION:
PBS&J Add XS using 1994 topo points
-E500-02-00 blocked below 89.05 ft (2001 adj.)
END DESCRIPTION:
XS GIS Cut Line= 6
        3070065.       13885022.        3070141.       13882540.
 3069957.0000001       13882440.        3070006.       13880460.
        3070008.       13880415.        3070011.       13880208.
#Sta/Elev= 30
    2391   98.87    3666   94.05    4305   90.05 4944.01   92.09 4961.01   88.12
    4972   81.46 4982.31   78.21 4990.55   77.09 4993.55   75.11 5017.95   73.84
 5027.78   75.69 5046.51   85.66 5084.98   93.29 5190.08   94.89 5340.18   91.63
 5355.21   89.73 5385.21   81.79 5400.24   79.41 5550.38   77.36 5715.51   79.94
 5775.54   82.31 5835.61      89 5925.67   89.09 5985.71   91.31 6601.24   90.67
 6751.37   84.87  6931.5   90.81 7096.64   91.13 7141.67   89.85 7318.72    91.1
#Mann= 3 ,-1 , 0
    2391     .12       0 4944.01     .04       0 5084.98     .12       0
#Block Obstruct= 1 ,-1
 5181.77 7309.17   89.05
Bank Sta=4944.01,5084.98
XS Rating Curve= 0 ,0
Exp/Cntr=0.6,0.4

Type RM Length L Ch R = 1 ,86924.79,179.1,389.2,453.6
BEGIN DESCRIPTION:
PBS&J Add XS using 1994 topo points
-E500-02-00 blocked below 89.05 ft (2001 adj.)
-E500-01-00 Cell between 3093-3553 ignored
END DESCRIPTION:
XS GIS Cut Line= 6
 3070111.292827813884956.1474061 3070170.354623513883385.1036369
 3070176.260803213882747.2362419 3070199.885521413882510.9890586
 3069987.263056513882404.6778261 3070040.418672713880189.8604824
#Sta/Elev= 30
    2391   97.13    3060   96.05    3141   88.05    3412   84.05    3486   85.05
    3526   93.05    3637   94.05    3676   85.05    3726   84.05    4827   80.05
    4888   91.05 4963.65   92.23    4973   81.44 5018.95   73.82    5063   89.81
 5126.51   92.71 5306.54   92.13 5366.55   78.86 5561.59   76.68 5741.62   78.84
 5817.78   89.03  5892.8    85.5 5952.82   90.98 6567.97    90.8 6657.99   79.53
    6703   78.47 6793.02   80.14 6913.05   90.96 7018.08   91.13 7273.14    91.2
#Mann= 5 ,-1 , 0
    2391     .12       0    3060     .05       0 4963.65     .04       0
 5126.51     .12       0 7018.08     .08       0
#XS Ineff= 1 ,-1
 3643.01 4920.54   90.05
Permanent Ineff=
       T
#Block Obstruct= 2 ,-1
 3092.18 3549.4794.15445 5181.75 7309.19   89.05
Bank Sta=4963.65,5126.51
XS Rating Curve= 0 ,0
Exp/Cntr=0.6,0.4

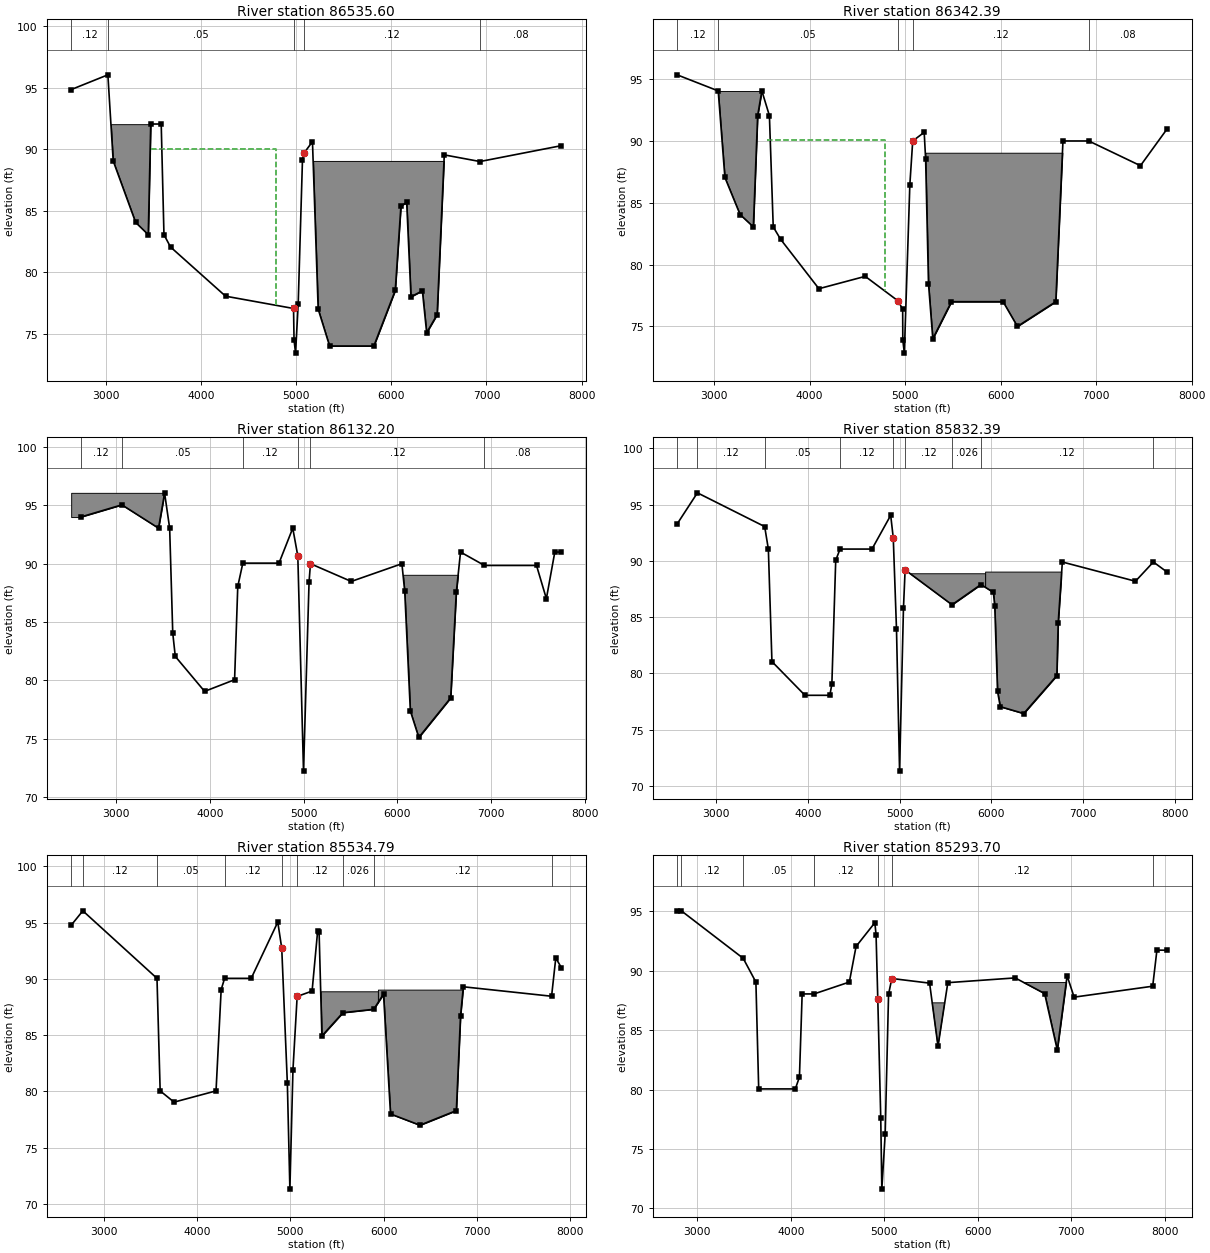
Type RM Length L Ch R = 1 ,86535.60,195.2,193.2,229.4
BEGIN DESCRIPTION:
PBS&J Add XS using 1994 topo points
-E500-02-00 blocked below 89.05 ft (2001 adj.)
-E500-01-00 Cell between 3054-3465 ignored
END DESCRIPTION:
XS GIS Cut Line= 6
        3070278.       13884664. 3070358.0000001       13883192.
        3070361.       13882414. 3070370.0000001       13882159.
        3070409.       13880899.        3070465.       13879546.
#Sta/Elev= 30
    2632   94.85    3018   96.05    3074   89.05    3310   84.05    3443   83.05
    3469   92.05    3579   92.05    3608   83.05    3677   82.05    4256   78.05
    4971   77.05  4976.3   74.49  4992.3   73.42 5019.93   77.41 5064.96   89.14
 5079.99   89.67 5170.09   90.62 5230.13      77 5350.26      74 5815.76      74
 6040.99   78.52 6101.06    85.4 6161.12   85.67 6206.16      78 6326.29   78.49
 6371.32   75.08 6481.48   76.55 6556.58   89.54 6932.08      89 7788.33   90.29
#Mann= 5 ,-1 , 0
    2632     .12       0    3018     .05       0    4971     .04       0
 5079.99     .12       0 6932.08     .08       0
#XS Ineff= 1 ,-1
 3473.02  4786.2   90.05
Permanent Ineff=
       T
#Block Obstruct= 2 ,-1
  2552.9 3501.71  92.038 5169.99    6646   89.05
Bank Sta=4971,5079.99
XS Rating Curve= 0 ,0
Exp/Cntr=0.6,0.4

Type RM Length L Ch R = 1 ,86342.39,212.5,210.2,250.8
BEGIN DESCRIPTION:
PBS&J Add XS using 1994 topo points
-E500-02-00 blocked below 89.05 ft (2001 adj.)
-E500-01-00 Cell between 3044-3501 ignored
END DESCRIPTION:
XS GIS Cut Line= 6
        3070469.       13884691.        3070550.       13883207.
        3070554.       13882423.        3070604.       13880837.
        3070608.       13880762.        3070657.       13879566.
#Sta/Elev= 30
    2614   95.35    3044   94.05    3114   87.05    3273   84.05    3412   83.05
    3457   92.05    3501   94.05    3580   92.05    3620   83.05    3697   82.05
    4098   78.05    4583   79.05    4929   77.05 4974.93   76.38  4976.3   73.91
  4992.3   72.84 5050.03   86.47 5080.07      90 5200.17    90.7  5215.2   88.53
 5245.23   78.46 5290.27      74 5485.46      77 6026.03      77  6176.2      75
 6577.66      77 6652.76      90 6923.12      90 7463.86      88 7745.25      91
#Mann= 5 ,-1 , 0
    2614     .12       0    3044     .05       0    4929     .04       0
 5080.07     .12       0 6923.12     .08       0
#XS Ineff= 1 ,-1
 3556.09 4786.49   90.05
Permanent Ineff=
       T
#Block Obstruct= 2 ,-1
 3031.83 3492.48   94.04 5153.58 6682.79   89.05
Bank Sta=4929,5080.07
XS Rating Curve= 0 ,0
Exp/Cntr=0.6,0.4

Type RM Length L Ch R = 1 ,86132.20,256.2,299.7,400.3
BEGIN DESCRIPTION:
PBS&J Add XS using 1994 topo points
-E500-02-00 blocked below 89.05 ft (2001 adj.)
END DESCRIPTION:
XS GIS Cut Line= 6
        3070679.       13884696.        3070760.       13883210.
        3070764.       13882425.        3070814.       13880840.
        3070821.       13880690.        3070866.       13879570.
#Sta/Elev= 30
    2619      94    3060   95.05    3451   93.05    3516   96.05    3570   93.05
    3603   84.05    3630   82.05    3943   79.05    4263   80.05    4297   88.05
    4351   90.05    4737   90.05    4884   93.05  4937.9   90.66  4998.7   72.21
 5058.03   88.45 5073.03      90 5508.49   88.48 6049.02      90 6079.06   87.62
 6139.12   77.37 6229.22    75.1 6569.62   78.49 6629.72   87.55 6674.76      91
 6930.12   89.85 7485.85   89.85 7591.02      87 7681.12      91 7751.22      91
#Mann= 6 ,-1 , 0
    2619     .12       0    3060     .05       0    4351     .12       0
  4937.9     .04       0 5073.03     .12       0 6930.12     .08       0
#XS Ineff= 1 ,-1
 3570.58 4873.33   90.05
Permanent Ineff=
       T
#Block Obstruct= 2 ,-1
 2518.77 3501.71   96.08 6047.78 6662.12   89.05
Bank Sta=4937.9,5073.03
XS Rating Curve= 0 ,0
Exp/Cntr=0.6,0.4

Type RM Length L Ch R = 1 ,85832.39,309.4,297.6,311.1
BEGIN DESCRIPTION:
PBS&J Add XS using 1994 topo points
-E500-02-00 blocked below 89.05 ft (2001 adj.)
-Wetlands near E500-02-00 blocked below (88.9 ft (2001 adj.)
END DESCRIPTION:
XS GIS Cut Line= 6
        3070916.       13884748.        3071034.       13882914.
        3071050.       13882614.        3071221.       13879599.
        3071223.       13879554.        3071222.       13879417.
#Sta/Elev= 30
    2576   93.28    2797   96.05    3530   93.05    3570   91.05    3609   81.05
    3969   78.05    4240   78.05    4262   79.05    4304   90.05    4351   91.05
    4699   91.05    4903   94.05    4931   92.05  4966.1   83.96  4999.7   71.31
    5042   85.77 5060.12    89.2 5571.08    86.1 5886.68    87.9 6021.91    87.2
 6036.95   85.95 6067.01    78.4 6097.05   77.04 6352.54   76.43 6713.21    79.8
 6728.24    84.5 6773.31    89.9  7569.8   88.19 7765.17    89.9  7917.2   88.99
#Mann= 9 ,-1 , 0
    2576     .08       0    2797     .12       0    3530     .05       0
    4351     .12       0    4931     .04       0 5060.12     .12       0
 5571.08    .026       0 5886.68     .12       0 7765.17     .08       0
#XS Ineff= 1 ,-1
 3531.09 4909.51   90.05
Permanent Ineff=
       T
#Block Obstruct= 2 ,-1
 5931.75    6761   89.05 5098.98 5931.75    88.9
Bank Sta=4931,5060.12
XS Rating Curve= 0 ,0
Exp/Cntr=0.3,0.1

Type RM Length L Ch R = 1 ,85534.79,162.2,241.1,200.1
BEGIN DESCRIPTION:
PBS&J Add XS using 1994 topo points
-E500-02-00 blocked below 89.05 ft (2001 adj.)
-Wetlands near E500-02-00 blocked below (88.9 ft (2001 adj.)
END DESCRIPTION:
XS GIS Cut Line= 6
        3071181.       13884686.        3071337.       13883128.
        3071367.       13882273.        3071443.       13879758.
        3071449.       13879593.        3071450.       13879417.
#Sta/Elev= 30
    2650   94.77    2775   96.05    3570   90.05    3604   80.05    3753   79.05
    4203   80.05    4258   89.05    4295   90.05    4580   90.05    4865   95.05
 4907.44   92.73  4967.5   80.75  4994.7   71.32 5027.57   81.91 5072.64   88.44
  5232.8   88.92 5292.84    94.3 5307.87   94.17  5337.9   84.93 5563.14      87
 5893.47    87.3 5998.57   88.65 6073.63      78 6388.97      77 6779.36    78.3
  6824.4   86.72 6854.43    89.3 7800.36   88.46 7845.36   91.86 7905.36      91
#Mann= 9 ,-1 , 0
    2650     .08       0    2775     .12       0    3570     .05       0
    4295     .12       0 4907.44     .04       0 5072.64     .12       0
 5563.14    .026       0 5893.47     .12       0 7800.36     .08       0
#XS Ineff= 1 ,-1
 3184.91  4866.1   90.05
Permanent Ineff=
       T
#Block Obstruct= 2 ,-1
  5290.1  5938.5    88.9  5938.5    6868   89.05
Bank Sta=4907.44,5072.64
XS Rating Curve= 0 ,0
Exp/Cntr=0.3,0.1

Type RM Length L Ch R = 1 ,85293.70,141.8,202.7,126.3
BEGIN DESCRIPTION:
PBS&J Add XS using 1994 topo points
-E500-02-00 blocked below 89.05 ft (2001 adj.)
END DESCRIPTION:
XS GIS Cut Line= 6
        3071373.       13884617.        3071541.       13882500.
        3071642.       13882325.        3071571.       13880240.
        3071550.       13879595.        3071534.       13879409.
#Sta/Elev= 30
    2784      95    2829   95.05    3491   91.05    3627   89.05    3657   80.05
    4049   80.05    4093   81.05    4122   88.05    4249   88.05    4627   89.05
    4699   92.05    4900   94.05    4913   93.05  4931.5   87.61  4963.2    77.6
  4974.7   71.61  5010.5   76.23 5046.84   88.03 5081.83   89.35 5485.92   88.96
 5576.02   83.64 5681.12      89 6401.95    89.4 6717.28   88.08 6852.45   83.33
 6957.55   89.58 7032.65   87.78 7873.65    88.7 7918.82   91.74 8030.23   91.73
#Mann= 7 ,-1 , 0
    2784     .08       0    2829     .12       0    3491     .05       0
    4249     .12       0  4931.5     .04       0 5081.83     .12       0
 7873.65     .08       0
#XS Ineff= 1 ,-1
 3422.62  4895.6   90.05
Permanent Ineff=
       T
#Block Obstruct= 2 ,-1
 5260.74 6754.71    87.3 6405.62 6958.41   89.05
Bank Sta=4931.5,5081.83
XS Rating Curve= 0 ,0
Exp/Cntr=0.3,0.1

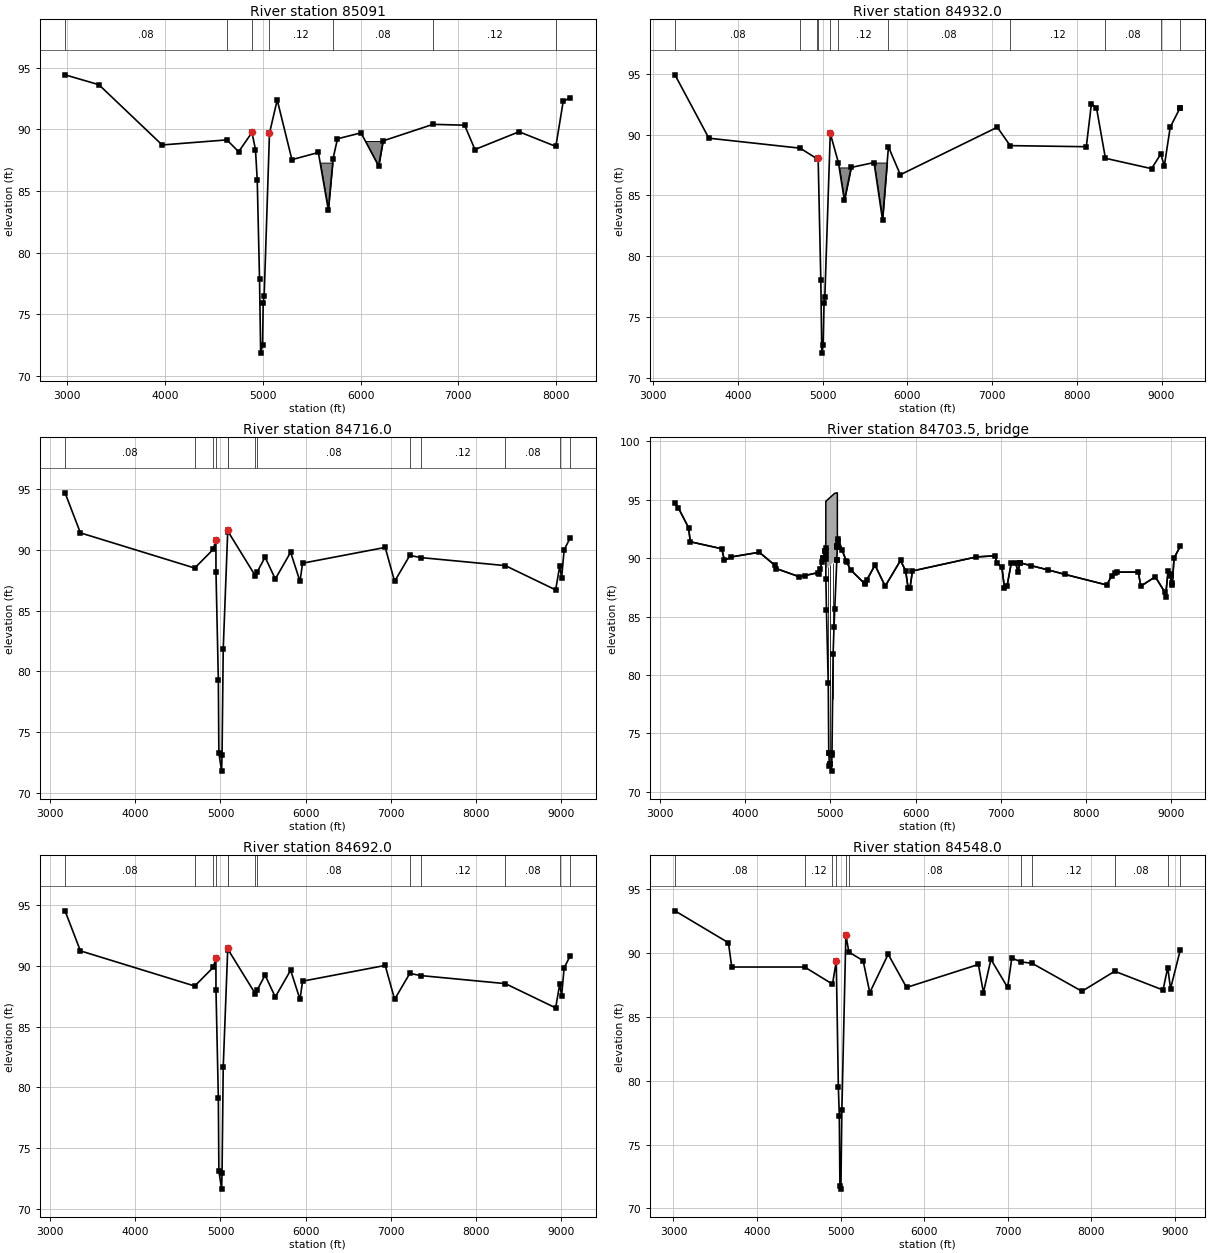
Type RM Length L Ch R = 1 ,85091   ,174.2,157.3,106.7
BEGIN DESCRIPTION:
PBS&J Add XS
END DESCRIPTION:
XS GIS Cut Line= 6
        3071533.       13884546.        3071658.       13882676.
        3071785.       13882480.        3071709.       13880808.
        3071658.       13880043.        3071619.       13879431.
#Sta/Elev= 30
    2981   94.41 3326.77   93.61  3973.2   88.73 4634.66   89.14 4754.93   88.18
  4890.7   89.74 4926.76   88.36 4944.78   85.89  4968.2   77.86  4979.7   71.87
    4999   72.51  5005.8   75.97  5015.5   76.49 5069.91   89.68 5148.88   92.38
 5299.11   87.54 5569.51   88.12 5671.22   83.47 5719.74   87.63 5764.81   89.23
 6005.17   89.71 6185.44   87.02  6230.5   89.06 6741.27    90.4 7063.95   90.33
 7169.19   88.36 7620.17    89.8 7995.92   88.61 8071.07   92.25 8143.22   92.57
#Mann= 7 ,-1 , 0
    2981     .08       0 4634.66     .12       0  4890.7     .04       0
 5069.91     .12       0 5719.74     .08       0 6741.27     .12       0
 7995.92     .08       0
#Block Obstruct= 2 ,-1
 5265.07 5742.89    87.3 6053.47 6459.61   89.05
Bank Sta=4890.7,5069.91
XS Rating Curve= 0 ,0
Exp/Cntr=0.3,0.1

Type RM Length L Ch R = 1 ,84932.0 ,209.4,216,223.3
BEGIN DESCRIPTION:
Cross Section E100-00-00-X60A
END DESCRIPTION:
XS GIS Cut Line= 5
      3071695.27     13884374.65      3071845.88      13882709.1
      3071892.89     13882538.69      3071792.19     13880587.12
      3071574.12     13878440.49
#Sta/Elev= 30
  3259.2    94.9  3659.2    89.7  4736.5   88.88  4940.3   87.99  4948.5   88.06
  4980.2   78.05  4991.7   72.06  5008.6   72.72  5017.8   76.16  5027.5   76.68
  5091.8   90.09  5188.2   87.68  5258.3    84.6  5338.3    87.3  5608.3    87.7
  5708.3      83  5778.1   88.99  5918.3    86.7  7062.5    90.6  7213.9   89.09
  8112.5      89  8172.5    92.5  8232.5    92.2    8338   88.05  8882.5    87.2
    8992   88.41  9032.5    87.4  9102.5    90.6  9219.7    92.2  9219.8    92.2
#Mann= 11 ,-1 , 0
  3259.2     .08       0  4736.5     .12       0  4940.3     .04       0
  4948.5     .04       0  5091.8     .08       0  5188.2     .12       0
  5778.1     .08       0  7213.9     .12       0    8338     .08       0
    8992     .05       0  9219.7     .99       0
#XS Ineff= 2 , 0
       0  4948.5   88.06  5091.8       0   90.09
Permanent Ineff=
       F       F
#Block Obstruct= 2 ,-1
    5193  5338.3    87.3  5608.3  5765.3    87.7
Bank Sta=4948.5,5091.8
XS Rating Curve= 0 ,0
Exp/Cntr=0.5,0.3

Type RM Length L Ch R = 1 ,84716.0 ,23.3,24,26.7
BEGIN DESCRIPTION:
Upstream Section of Bridge/Culvert/Weir
Cross section spills into E117-00-00, therefore extending the right overbank to contain the floodplain is not possible.
END DESCRIPTION:
XS GIS Cut Line= 4
      3071852.45     13884473.09      3072071.06     13882737.92
      3072074.67     13882569.51      3072000.11      13878558.2
#Sta/Elev= 30
  3176.2   94.71  3356.2   91.41  4697.9   88.51  4916.7   90.06  4946.5   90.85
  4947.4   88.21  4975.1    79.3  4981.3   73.28  5013.5   71.77  5018.6   73.13
  5032.4   81.83  5085.6   91.61  5092.6   91.48  5408.5   87.88  5429.5   88.16
  5523.5   89.41  5643.5   87.61  5823.5   89.81  5933.5   87.41  5963.5   88.91
  6933.5   90.21  7043.5   87.41  7222.1   89.55  7354.1   89.37  8343.1   88.71
  8933.5   86.71  8981.6   88.67  9003.5   87.71  9033.5   90.01    9105   91.01
#Mann= 13 ,-1 , 0
  3176.2     .08       0  4697.9     .12       0  4916.7     .04       0
  4946.5     .04       0  5085.6     .04       0  5092.6     .08       0
  5408.5     .12       0  5429.5     .08       0  7222.1     .07       0
  7354.1     .12       0  8343.1     .08       0  8981.6     .07       0
    9105     .99       0
#XS Ineff= 2 , 0
       0  4946.4      89  5085.6       0      89
Permanent Ineff=
       F       F
Bank Sta=4946.5,5085.6
XS Rating Curve= 0 ,0
Exp/Cntr=0.5,0.3

Type RM Length L Ch R = 3 ,84703.5 ,,,
BEGIN DESCRIPTION:
GOLF CART BRIDGE
Structure ID: E100-00-00-43a
END DESCRIPTION:
Bridge Culvert--1,0,-1,-1, 0
Deck Dist Width WeirC Skew NumUp NumDn MinLoCord MaxHiCord MaxSubmerge Is_Ogee
10,5,2.6,0, 60, 60, , , 0.95, 0, ,,,
  3176.2  3216.2  3336.2  3356.2  3726.2  3756.2  3836.2  4166.2  4346.2  4366.2
  4636.2  4858.8  4862.6  4916.7 4936.91  4946.5 4946.59  4946.7 4946.81  4947.4
  5051.5 5075.49  5082.1 5082.21  5085.6  5092.6  5190.6  5237.8  5403.5  5523.5
  5643.5  5823.5  5883.5  5913.5  5933.5  5963.5  6713.5  6933.5  6953.5  7013.5
  7043.5  7073.5  7123.5  7173.5  7203.5  7223.5  8243.5  8303.5  8363.5  8613.5
  8643.5  8813.5  8923.5  8933.5  8963.5  8993.5  9003.5  9013.5  9033.5    9105
    94.7    94.3    92.6    91.4    90.8    89.8    90.1    90.5    89.4    89.1
    88.4   88.76   88.62   90.06   90.74   91.27   91.27   94.87   94.87   94.87
   95.55   95.58   95.59   91.99   91.88   91.66   89.68      89    87.8    89.4
    87.6    89.8    88.9    87.4    87.4    88.9    90.1    90.2    89.6    89.2
    87.4    87.6    89.6    89.6    88.8    89.6    87.7    88.5    88.8    88.8
    87.6    88.4    87.1    86.7    88.9    88.5    87.7    87.9      90      91
    94.7    94.3    92.6    91.4    90.8    89.8    90.1    90.5    89.4    89.1
    88.4   88.76   88.62   90.05   90.59   90.84   90.58   90.25   89.93   89.07
   89.75   89.83   90.99   91.01    91.6   91.47   89.68      89    87.8    89.4
    87.6    89.8    88.9    87.4    87.4    88.9    90.1    90.2    89.6    89.2
    87.4    87.6    89.6    89.6    88.8    89.6    87.7    88.5    88.8    88.8
    87.6    88.4    87.1    86.7    88.9    88.5    87.7    87.9      90      91
  3176.2  3216.2  3336.2  3356.2  3726.2  3756.2  3836.2  4166.2  4346.2  4366.2
  4636.2  4858.8  4862.6  4916.7 4936.91  4946.5 4946.59  4946.7 4946.81  4947.4
  5051.5 5075.49  5082.1 5082.21  5085.6  5092.6  5190.6  5237.8  5403.5  5523.5
  5643.5  5823.5  5883.5  5913.5  5933.5  5963.5  6713.5  6933.5  6953.5  7013.5
  7043.5  7073.5  7123.5  7173.5  7203.5  7223.5  8243.5  8303.5  8363.5  8613.5
  8643.5  8813.5  8923.5  8933.5  8963.5  8993.5  9003.5  9013.5  9033.5    9105
    94.7    94.3    92.6    91.4    90.8    89.8    90.1    90.5    89.4    89.1
    88.4   88.76   88.62   90.06   90.74   91.27   91.27   94.87   94.87   94.87
   95.55   95.58   95.59   91.99   91.88   91.66   89.68      89    87.8    89.4
    87.6    89.8    88.9    87.4    87.4    88.9    90.1    90.2    89.6    89.2
    87.4    87.6    89.6    89.6    88.8    89.6    87.7    88.5    88.8    88.8
    87.6    88.4    87.1    86.7    88.9    88.5    87.7    87.9      90      91
   94.57   94.17   92.47   91.27   90.67   89.67   89.97   90.37   89.27   88.97
   88.27   88.63   88.49   89.92   90.46   90.71   90.45   90.12    89.8   88.94
   89.62    89.7   90.86   90.88   91.47   91.34   89.55   88.87   87.67   89.27
   87.47   89.67   88.77   87.27   87.27   88.77   89.97   90.07   89.47   89.07
   87.27   87.47   89.47   89.47   88.67   89.47   87.57   88.37   88.67   88.67
   87.47   88.27   86.97   86.57   88.77   88.37   87.57   87.77   89.87   90.87
Pier Skew, UpSta & Num, DnSta & Num=  ,4973, 2 ,4973, 2 , 0 , 0 , 0 ,,
       1       1
   78.77   90.24
       1       1
   78.64   90.11
Pier Skew, UpSta & Num, DnSta & Num=  ,4999.1, 2 ,4999.1, 2 , 0 , 0 , 0 ,,
       1       1
   71.37   90.41
       1       1
   71.24   90.28
Pier Skew, UpSta & Num, DnSta & Num=  ,5026.3, 2 ,5026.3, 2 , 0 , 0 , 0 ,,
       1       1
   76.64   90.59
       1       1
   76.51   90.46
BR Coef= 1 , 1 , 0 ,1.25, 0 ,,,0.8,-1,2,0,
WSPro=,,,, 1 ,,,, 0 ,,,, 0 ,,,,-1 ,-1 ,-1 , 0 , 0 , 0 , 0 , 0
BR U #Sta/Elev= 91
  3176.2    94.7  3216.2    94.3  3336.2    92.6  3356.2    91.4  3726.2    90.8
  3756.2    89.8  3836.2    90.1  4166.2    90.5  4346.2    89.4  4366.2    89.1
  4636.2    88.4  4697.9    88.5  4858.8   88.76  4862.6   88.62  4880.9    89.1
  4900.9   89.63  4910.9    89.9  4915.7   90.03  4916.7   90.05 4936.91   90.59
    4937   90.59  4946.5   90.84 4946.59   90.58  4946.7   90.25 4946.81   89.93
  4947.4    88.2    4954   85.56  4975.1   79.29  4981.3   73.27  4981.4   73.28
  4989.6   72.22  4997.8   72.36  4999.5   72.39  5013.5   71.76  5018.6   73.12
  5018.9   73.28  5032.4   81.82  5042.5   84.06  5051.5   85.63 5075.49   89.83
  5075.6   89.85 5081.99   90.97  5082.1   90.99 5082.21   91.01  5082.3   91.02
  5085.6    91.6  5092.6   91.47  5134.8    90.7  5186.8   89.75  5190.6   89.68
  5237.8      89  5403.5    87.8  5408.5   87.87  5429.5   88.15  5523.5    89.4
  5643.5    87.6  5823.5    89.8  5883.5    88.9  5913.5    87.4  5933.5    87.4
  5963.5    88.9  6713.5    90.1  6933.5    90.2  6953.5    89.6  7013.5    89.2
  7043.5    87.4  7073.5    87.6  7123.5    89.6  7173.5    89.6  7203.5    88.8
  7222.1   89.54  7223.5    89.6  7354.1   89.36  7553.5      89  7753.5    88.6
  8243.5    87.7  8303.5    88.5  8343.1    88.7  8363.5    88.8  8613.5    88.8
  8643.5    87.6  8813.5    88.4  8923.5    87.1  8933.5    86.7  8963.5    88.9
  8981.6   88.66  8993.5    88.5  9003.5    87.7  9013.5    87.9  9033.5      90
    9105      91
BR U #Mann= 14
  3176.2     .99  3176.2     .08  4697.9     .12  4916.7     .04  4946.5     .04
  5085.6     .04  5092.6     .08  5408.5     .12  5429.5     .08  7222.1     .07
  7354.1     .12  8343.1     .08  8981.6     .07    9105     .99
BR U Banks=4946.5,5085.6
BR D #Sta/Elev= 91
  3176.2   94.57  3216.2   94.17  3336.2   92.47  3356.2   91.27  3726.2   90.67
  3756.2   89.67  3836.2   89.97  4166.2   90.37  4346.2   89.27  4366.2   88.97
  4636.2   88.27  4697.9   88.37  4858.8   88.63  4862.6   88.49  4880.9   88.97
  4900.9    89.5  4910.9   89.77  4915.7    89.9  4916.7   89.92 4936.91   90.46
    4937   90.46  4946.5   90.71 4946.59   90.45  4946.7   90.12 4946.81    89.8
  4947.4   88.07    4954   85.43  4975.1   79.16  4981.3   73.14  4981.4   73.15
  4989.6   72.09  4997.8   72.23  4999.5   72.26  5013.5   71.63  5018.6   72.99
  5018.9   73.15  5032.4   81.69  5042.5   83.93  5051.5    85.5 5075.49    89.7
  5075.6   89.72 5081.99   90.84  5082.1   90.86 5082.21   90.88  5082.3   90.89
  5085.6   91.47  5092.6   91.34  5134.8   90.57  5186.8   89.62  5190.6   89.55
  5237.8   88.87  5403.5   87.67  5408.5   87.74  5429.5   88.02  5523.5   89.27
  5643.5   87.47  5823.5   89.67  5883.5   88.77  5913.5   87.27  5933.5   87.27
  5963.5   88.77  6713.5   89.97  6933.5   90.07  6953.5   89.47  7013.5   89.07
  7043.5   87.27  7073.5   87.47  7123.5   89.47  7173.5   89.47  7203.5   88.67
  7222.1   89.41  7223.5   89.47  7354.1   89.23  7553.5   88.87  7753.5   88.47
  8243.5   87.57  8303.5   88.37  8343.1   88.57  8363.5   88.67  8613.5   88.67
  8643.5   87.47  8813.5   88.27  8923.5   86.97  8933.5   86.57  8963.5   88.77
  8981.6   88.53  8993.5   88.37  9003.5   87.57  9013.5   87.77  9033.5   89.87
    9105   90.87
BR D #Mann= 14
  3176.2     .99  3176.2     .08  4697.9     .12  4916.7     .04  4946.5     .04
  5085.6     .04  5092.6     .08  5408.5     .12  5429.5     .08  7222.1     .07
  7354.1     .12  8343.1     .08  8981.6     .07    9105     .99
BR D Banks=4946.5,5085.6
BC Design=,, 0 ,, 0 ,,,,,,
BC HTab HWMax=94.71
BC Use User HTab Curves=0
BC User HTab FreeFlow(D)= 0

Type RM Length L Ch R = 1 ,84692.0 ,219.5,144,134
BEGIN DESCRIPTION:
Downstream Section of Bridge/Culvert/Weir
Cross section spills into E117-00-00, therefore extending the right overbank to contain the floodplain is not possible.
END DESCRIPTION:
XS GIS Cut Line= 4
      3071875.24     13884478.74      3072094.04     13882742.02
       3072097.7      13882571.5      3072034.09     13878559.98
#Sta/Elev= 30
  3176.2   94.56  3356.2   91.26  4697.9   88.36  4916.7   89.91  4946.5    90.7
  4947.4   88.06  4975.1   79.15  4981.3   73.13  5013.5   71.62  5018.6   72.98
  5032.4   81.68  5085.6   91.46  5092.6   91.33  5408.5   87.73  5429.5   88.01
  5523.5   89.26  5643.5   87.46  5823.5   89.66  5933.5   87.26  5963.5   88.76
  6933.5   90.06  7043.5   87.26  7222.1    89.4  7354.1   89.22  8343.1   88.56
  8933.5   86.56  8981.6   88.52  9003.5   87.56  9033.5   89.86    9105   90.86
#Mann= 13 ,-1 , 0
  3176.2     .08       0  4697.9     .12       0  4916.7     .04       0
  4946.5     .04       0  5085.6     .04       0  5092.6     .08       0
  5408.5     .12       0  5429.5     .08       0  7222.1     .07       0
  7354.1     .12       0  8343.1     .08       0  8981.6     .07       0
    9105     .99       0
#XS Ineff= 2 , 0
       0  4946.4      89  5077.3       0      89
Permanent Ineff=
       F       F
Bank Sta=4946.5,5085.6
XS Rating Curve= 0 ,0
Exp/Cntr=0.5,0.3

Type RM Length L Ch R = 1 ,84548.0 ,533.7,733,790.3
BEGIN DESCRIPTION:
Cross Section E100-00-00-X60B
Cross section spills into E117-00-00, therefore extending the right overbank to contain the floodplain is not possible.
END DESCRIPTION:
XS GIS Cut Line= 4
      3072232.06     13884588.69      3072257.75     13882713.59
      3072203.21     13882493.12      3072224.32     13878546.99
#Sta/Elev= 30
  3018.2    93.3  3658.2    90.8  3698.2    88.9  4570.9    88.9  4904.1   87.56
  4949.1   89.35  4974.4   79.47  4985.6   77.23  4992.8   71.78  5004.4   71.51
  5016.3    77.7  5064.2   91.43    5100   90.07  5270.6    89.4  5350.6    86.9
  5570.6    89.9  5790.6    87.3  6650.6    89.1  6710.6    86.9  6800.6    89.5
  7000.6    87.3  7050.6    89.6  7162.6    89.3  7294.1   89.19  7890.6      87
  8282.5   88.57  8860.6    87.1  8917.5   88.86  8950.6    87.2  9065.9    90.2
#Mann= 11 ,-1 , 0
  3018.2     .08       0  4570.9     .12       0  4904.1     .04       0
  4949.1     .04       0  5064.2     .04       0    5100     .08       0
  7162.6     .07       0  7294.1     .12       0  8282.5     .08       0
  8917.5     .07       0  9065.9     .99       0
#XS Ineff= 2 , 0
       0  4949.1   89.35  5064.2       0    89.2
Permanent Ineff=
       F       F
Bank Sta=4949.1,5064.2
XS Rating Curve= 0 ,0
Exp/Cntr=0.3,0.1