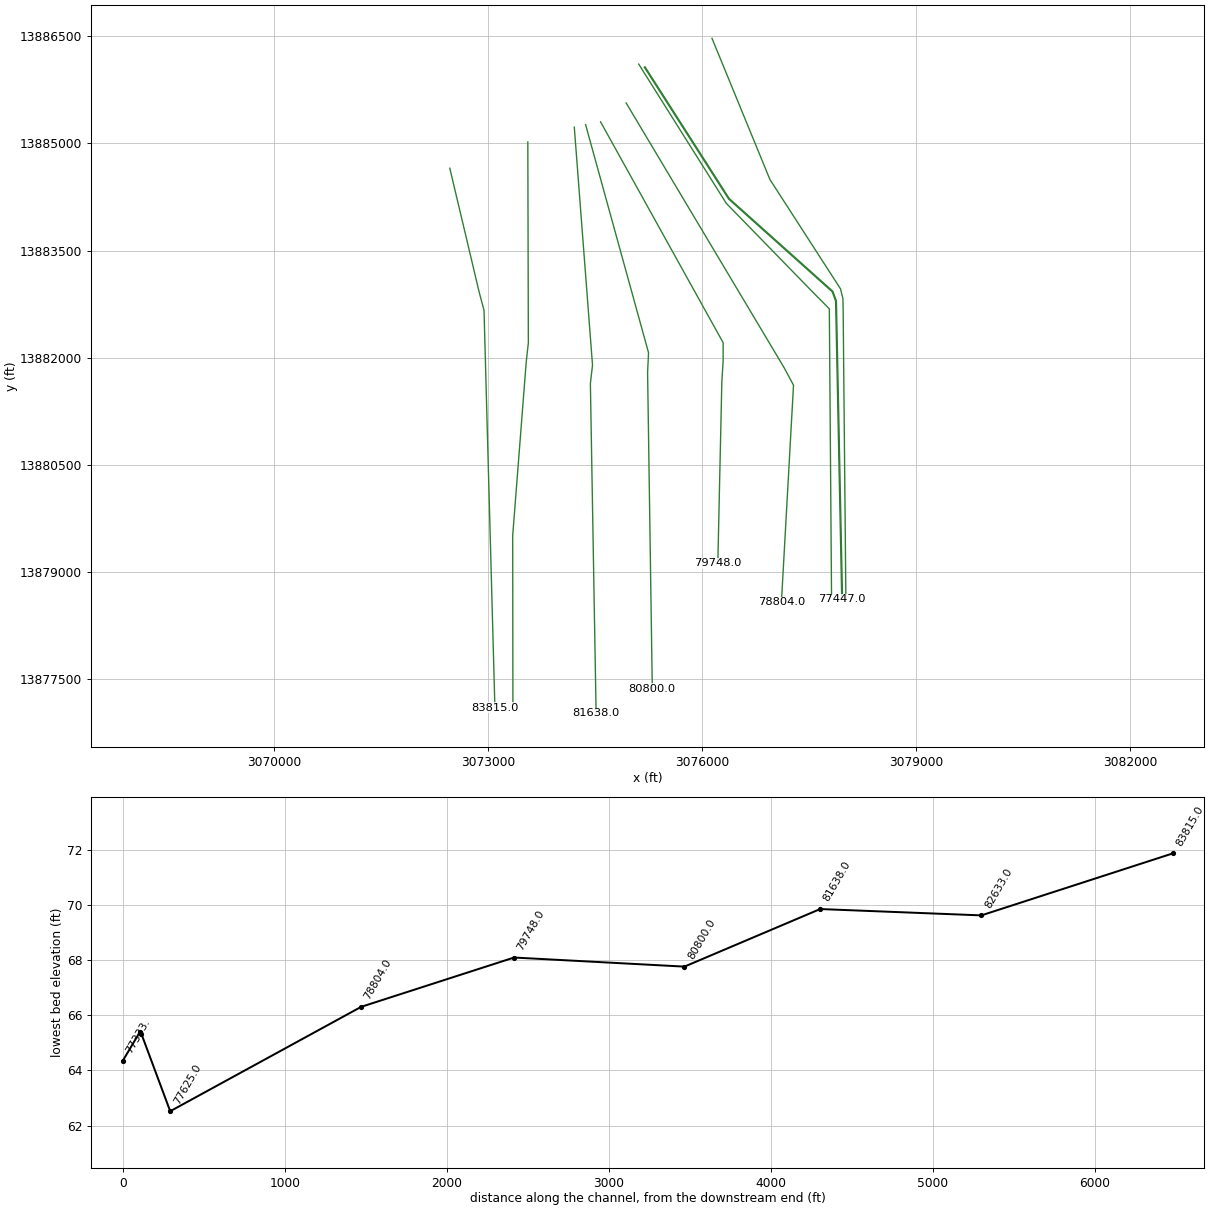
HEC-RAS study E100-00-00.prj: E100-00-00

--- E100-00-00.g02 (geometry) --- (continued)

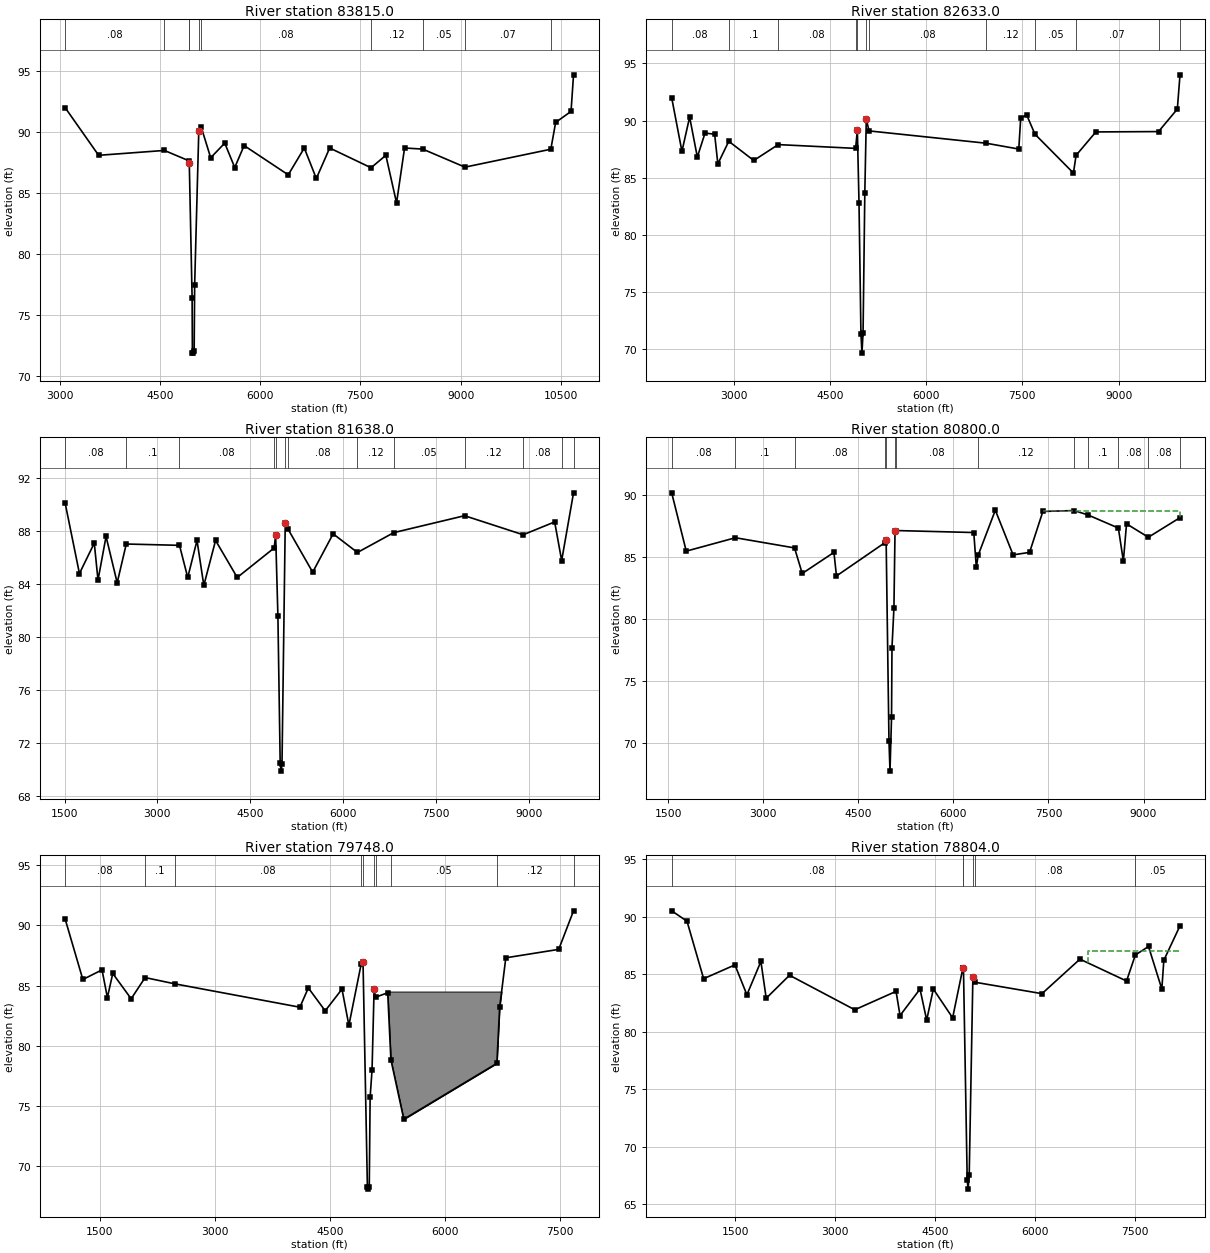
Type RM Length L Ch R = 1 ,83815.0 ,1183,1182,495.1
BEGIN DESCRIPTION:
Cross Section E100-00-00-X60
END DESCRIPTION:
XS GIS Cut Line= 4
      3072466.48     13884653.24       3072879.8     13882911.41
      3072946.06     13882664.34      3073098.74     13877100.84
#Sta/Elev= 30
  3084.9      92  3584.9    88.1  4568.5    88.5  4931.3   87.66  4940.9   87.44
    4983    76.4    4987   71.92  4998.8   71.88  5013.7   72.05  5021.1   77.48
  5082.9    90.1  5118.9   90.42  5260.9    87.9  5470.9    89.1  5620.9    87.1
  5760.9    88.9  6420.9    86.5  6660.9    88.7  6840.9    86.2  7040.9    88.7
  7659.5   87.08  7880.9    88.1  8040.9    84.2  8160.9    88.7  8432.6   88.61
  9064.4   87.13 10348.6    88.6 10420.9    90.8 10650.9    91.7 10688.2    94.7
#Mann= 10 ,-1 , 0
  3084.9     .08       0  4568.5     .12       0  4931.3     .04       0
  4940.9     .04       0  5082.9     .04       0  5118.9     .08       0
  7659.5     .12       0  8432.6     .05       0  9064.4     .07       0
 10348.6     .08       0
#XS Ineff= 2 , 0
       0  4940.9   87.44  5082.9       0      88
Permanent Ineff=
       F       F
Bank Sta=4940.9,5082.9
XS Rating Curve= 0 ,0
Exp/Cntr=0.3,0.1

Type RM Length L Ch R = 1 ,82633.0 ,821.9,995,996.7
BEGIN DESCRIPTION:
Cross Section E100-00-00-X59
END DESCRIPTION:
XS GIS Cut Line= 5
      3073560.07     13885021.21      3073567.41     13882207.82
      3073537.23     13881935.04      3073348.05     13879510.24
      3073350.98     13877128.86
#Sta/Elev= 30
    2032      92    2192    87.3    2312    90.3    2432    86.8    2552    88.9
    2702    88.8    2752    86.2  2922.3   88.18    3312    86.5  3693.6   87.89
  4899.7   87.56  4927.2   89.17  4952.9   82.76  4982.9   71.33  4998.8   69.63
  5016.1   71.43  5043.5   83.69  5066.3   90.12  5109.2   89.09  6936.6   88.01
  7443.9    87.5  7473.9    90.2  7566.1    90.5  7696.4    88.8  8296.1    85.4
  8337.2   86.95  8646.1      89  9622.6   89.03  9916.1      91  9957.7      94
#Mann= 12 ,-1 , 0
    2032     .08       0  2922.3      .1       0  3693.6     .08       0
  4899.7     .04       0  4927.2     .04       0  5066.3     .04       0
  5109.2     .08       0  6936.6     .12       0  7696.4     .05       0
  8337.2     .07       0  9622.6     .08       0  9957.7     .99       0
#XS Ineff= 2 , 0
       0  4927.2      88  5066.3       0      88
Permanent Ineff=
       F       F
Bank Sta=4927.2,5066.3
XS Rating Curve= 0 ,0
Exp/Cntr=0.3,0.1

Type RM Length L Ch R = 1 ,81638.0 ,602.5,838,839
BEGIN DESCRIPTION:
Cross Section E100-00-00-X58
END DESCRIPTION:
XS GIS Cut Line= 4
      3074211.48     13885227.72      3074466.96     13881896.61
      3074437.05     13881639.66       3074517.4     13877020.79
#Sta/Elev= 30
  1511.4    90.1  1741.4    84.8  1981.4    87.1  2041.4    84.3  2171.4    87.6
  2351.4    84.1  2498.1   87.03  3358.2   86.93  3491.4    84.5  3641.4    87.3
  3751.4    83.9  3941.4    87.3  4291.4    84.5  4888.1   86.73  4912.2    87.7
  4948.6    81.6  4985.4   70.48  5000.9   69.86  5014.7   70.38  5067.3   88.61
  5108.1   88.19    5511    84.9    5841    87.8  6233.9   86.39  6820.4   87.89
  7965.1   89.17  8912.1   87.73    9421    88.7  9534.4   85.78  9726.1    90.9
#Mann= 13 ,-1 , 0
  1511.4     .08       0  2498.1      .1       0  3358.2     .08       0
  4888.1     .04       0  4912.2     .04       0  5067.3     .04       0
  5108.1     .08       0  6233.9     .12       0  6820.4     .05       0
  7965.1     .12       0  8912.1     .08       0  9534.4     .08       0
  9726.1     .99       0
#XS Ineff= 2 , 0
       0  4912.2      86  5067.3       0      86
Permanent Ineff=
       F       F
Bank Sta=4912.2,5067.3
XS Rating Curve= 0 ,0
Exp/Cntr=0.3,0.1

Type RM Length L Ch R = 1 ,80800.0 ,859.3,1052,1053
BEGIN DESCRIPTION:
Cross Section E100-00-00-X57
END DESCRIPTION:
XS GIS Cut Line= 4
      3074369.86     13885263.35      3075252.27     13882069.96
       3075238.9     13881796.99      3075304.93     13877362.37
#Sta/Elev= 30
  1555.3    90.2  1785.3    85.5  2561.4   86.58  3493.6   85.76  3615.3    83.7
  4115.3    85.4  4155.3    83.5  4918.2   86.18  4938.8   86.39  4983.6   70.22
  4999.9   67.77  5024.1    72.1    5031   77.73  5061.7   80.89  5079.2   87.14
  5096.4   87.16  6321.7      87  6361.7    84.2  6390.8   85.17  6661.7    88.8
  6941.7    85.2  7201.7    85.4  7411.7    88.7  7904.8   88.77  8122.5   88.42
  8602.8   87.36  8681.7    84.7  8731.7    87.7  9075.7   86.62  9575.2    88.2
#Mann= 13 ,-1 , 0
  1555.3     .08       0  2561.4      .1       0  3493.6     .08       0
  4918.2     .04       0  4938.8     .04       0  5079.2     .04       0
  5096.4     .08       0  6390.8     .12       0  7904.8     .08       0
  8122.5      .1       0  8602.8     .08       0  9075.7     .08       0
  9575.2     .99       0
#XS Ineff= 3 ,-1
  1555.3  4938.8   86.39  5079.2 7338.07   86.39  7411.7  9575.2    88.7
Permanent Ineff=
       F       F       F
Bank Sta=4938.8,5079.2
XS Rating Curve= 0 ,0
Exp/Cntr=0.3,0.1

Type RM Length L Ch R = 1 ,79748.0 ,563.1,944,991.1
BEGIN DESCRIPTION:
Cross Section E100-00-00-X56
END DESCRIPTION:
XS GIS Cut Line= 5
      3074579.57     13885302.66      3076298.03     13882210.53
      3076297.82      13881950.6      3076279.77     13881665.07
      3076223.41     13879122.59
#Sta/Elev= 30
  1047.5    90.5  1277.5    85.5  1527.5    86.3  1597.5      84  1667.5      86
  1907.5    83.9  2089.4   85.66  2476.3   85.14  4107.5    83.2  4217.5    84.8
  4437.5    82.9  4656.4    84.7  4746.4    81.7  4907.2    86.8  4930.7   86.96
  4987.8   68.28  5001.1    68.1  5012.1   68.26  5023.4   75.74  5048.4   77.99
  5074.9   84.67  5095.1   84.03  5252.5    84.4  5294.2   78.84  5462.5    73.9
    6676   78.54  6712.5    83.2  6792.5    87.3  7482.5      88  7675.6    91.2
#Mann= 10 ,-1 , 0
  1047.5     .08       0  2089.4      .1       0  2476.3     .08       0
  4907.2     .04       0  4930.7     .04       0  5074.9     .04       0
  5095.1     .12       0  5294.2     .05       0    6676     .12       0
  7675.6     .99       0
#XS Ineff= 2 , 0
       0  4930.7   84.67  5074.9       0   84.67
Permanent Ineff=
       F       F
#Block Obstruct= 2 ,-1
  5242.5    6750    84.5    6751    6752      70
Bank Sta=4930.7,5074.9
XS Rating Curve= 0 ,0
Exp/Cntr=0.3,0.1

Type RM Length L Ch R = 1 ,78804.0 ,719,1179,1180
BEGIN DESCRIPTION:
Cross Section E100-00-00-X55
END DESCRIPTION:
XS GIS Cut Line= 4
      3074938.15     13885567.15      3077151.91     13881861.81
      3077284.46     13881615.97      3077114.83     13878574.98
#Sta/Elev= 30
   546.2    90.5   776.2    89.6  1026.2    84.6  1496.2    85.8  1676.2    83.2
  1886.2    86.1  1966.2    82.9  2316.2    84.9  3296.2    81.9  3916.2    83.5
  3976.2    81.4  4276.2    83.7  4376.2      81  4476.2    83.7  4766.2    81.2
  4918.8   85.49  4928.5   85.55    4985   67.12  4997.9   66.31  5015.1   67.56
  5070.1   84.71  5104.2   84.29  6108.1    83.3  6678.1    86.3  7378.1    84.4
  7510.2   86.66  7708.1    87.4  7908.1    83.7  7938.1    86.2    8181    89.2
#Mann= 6 ,-1 , 0
   546.2     .08       0  4918.8     .04       0  4928.5     .04       0
  5070.1     .04       0  5104.2     .08       0  7510.2     .05       0
#XS Ineff= 3 ,-1
   546.2  4928.5   84.71  5070.1    6800   84.71    6800    8181      87
Permanent Ineff=
       F       F       F
Bank Sta=4928.5,5070.1
XS Rating Curve= 0 ,0
Exp/Cntr=0.3,0.1

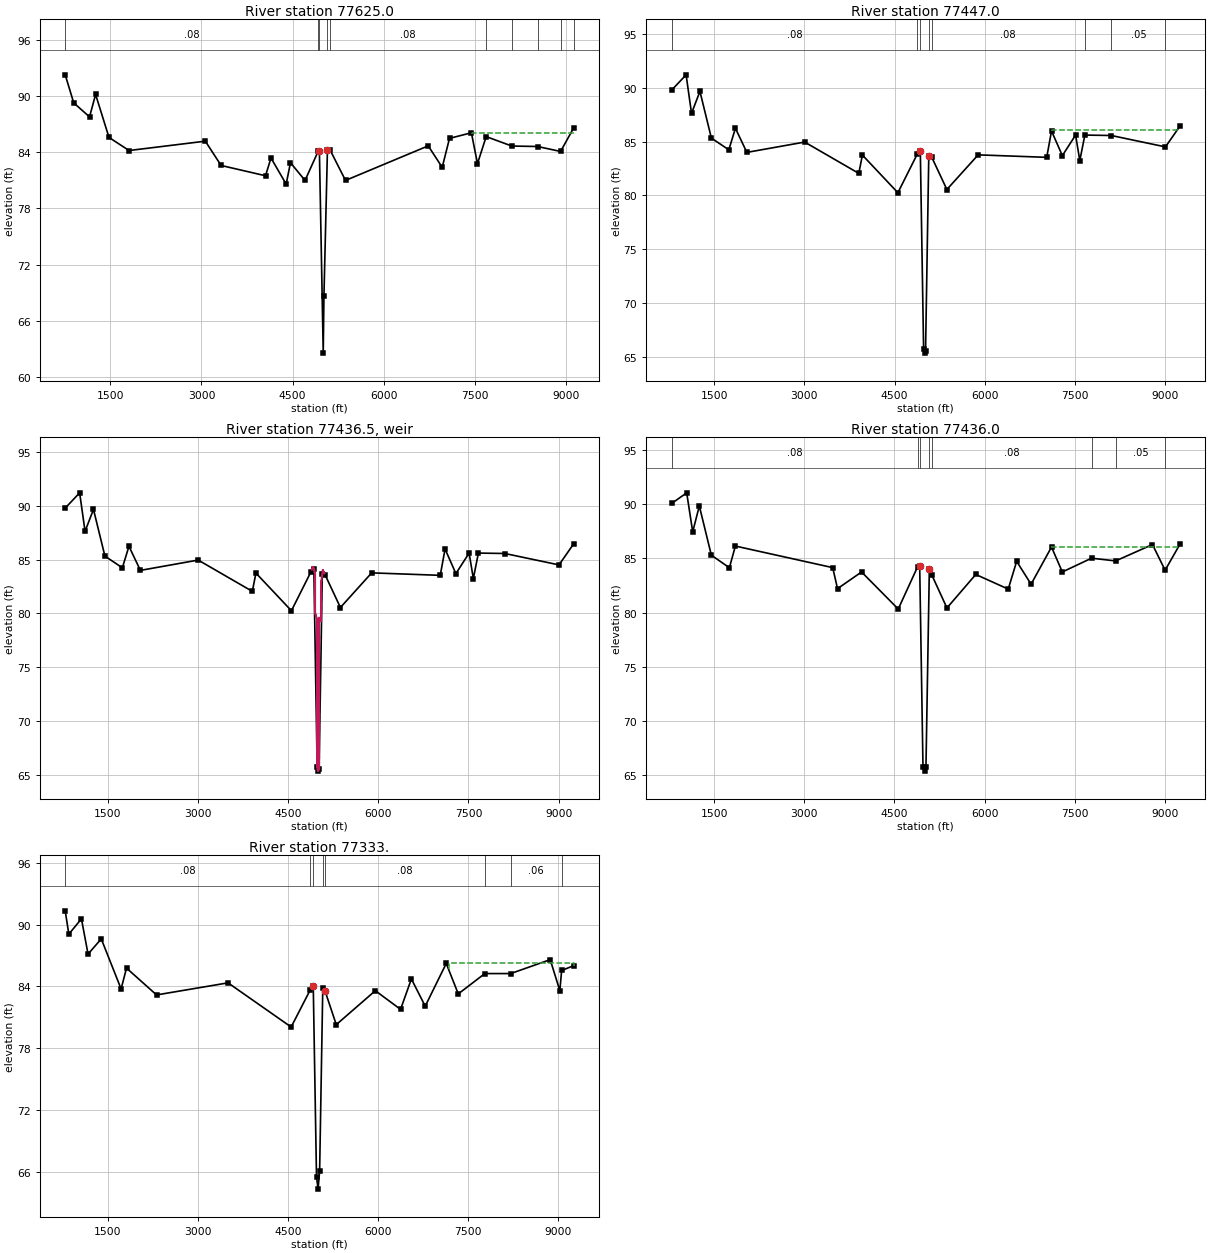
Type RM Length L Ch R = 1 ,77625.0 ,179,178,132.4
BEGIN DESCRIPTION:
Cross Section E100-00-00-X54
END DESCRIPTION:
XS GIS Cut Line= 5
      3075114.22      13886111.3      3076342.15     13884161.76
      3077571.28     13882901.25      3077786.35     13882685.04
       3077817.3     13878684.16
#Sta/Elev= 30
   759.5    92.3   899.5    89.3  1159.5    87.8  1259.5    90.2  1479.5    85.6
  1809.5    84.2  3063.5    85.2  3323.5    82.6  4053.5    81.5  4143.5    83.4
  4393.5    80.6  4463.5    82.9  4703.5      81  4923.5   84.18  4939.6   84.15
  5002.7   62.52  5014.1   68.58  5071.8   84.25  5114.9   84.26  5369.1      81
  6729.1    84.7  6959.1    82.4  7079.1    85.5  7439.1    86.1  7539.1    82.8
  7682.4   85.69  8103.9   84.68  8527.2   84.63  8905.9    84.1  9118.7    86.6
#Mann= 10 ,-1 , 0
   759.5     .08       0  4923.5     .04       0  4939.6     .04       0
  5071.8     .04       0  5114.9     .08       0  7682.4      .1       0
  8103.9     .05       0  8527.2      .1       0  8905.9     .08       0
  9118.7     .99       0
#XS Ineff= 2 , 0
       0                    7443       0   86.07
Permanent Ineff=
       F       F
Bank Sta=4939.6,5071.8
XS Rating Curve= 0 ,0
Exp/Cntr=0.7,0.5

Type RM Length L Ch R = 1 ,77447.0 ,10,11,14.1
BEGIN DESCRIPTION:
Upstream Section of Bridge/Culvert/Weir
END DESCRIPTION:
XS GIS Cut Line= 5
      3075193.89     13886066.65       3076375.3     13884221.31
      3077826.62     13882923.68      3077874.49     13882794.53
      3077960.47      13878619.4
#Sta/Elev= 30
   795.1   89.78  1035.1    91.2  1125.1   87.62  1265.1   89.66  1455.1   85.32
  1745.1   84.23  1855.1   86.23  2045.1   83.99  3006.2   84.95  3906.2   82.04
  3966.2   83.74  4556.2   80.24 4881.95   83.87 4929.01   84.15 4983.79   65.72
 4999.23   65.33  5016.2   65.54 5069.74   83.62    5116   83.58  5370.8   80.54
  5890.8   83.76  7030.8   83.53  7110.8   85.98  7290.8   83.69  7510.8    85.6
  7580.8   83.23    7665    85.6    8105   85.56    9005    84.5  9246.8   86.44
#Mann= 8 ,-1 , 0
   795.1     .08       0 4881.95     .04       0 4929.01    .015       0
 5069.74     .04       0    5116     .08       0    7665      .1       0
    8105     .05       0    9005     .08       0
#XS Ineff= 2 , 0
       0                    7112       0   86.07
Permanent Ineff=
       F       F
Bank Sta=4929.01,5069.74
XS Rating Curve= 0 ,0
Exp/Cntr=0.7,0.5

Type RM Length L Ch R = 5 ,77436.5 ,,,
BEGIN DESCRIPTION:
E100_Control Structure US of Houston-Rosslyn
Structure ID: E100_Control Structure US Houston-Rosslyn
END DESCRIPTION:
IW Pilot Flow=0
#Inline Weir SE= 13
 4894.39   84.08 4920.32   84.32 4948.68    83.7 4948.79   80.08  4981.8   79.46
 4983.41   65.66 4999.91   65.33 5016.58   65.57 5017.01    79.6 5050.14   79.26
 5050.14   82.88 5078.54   84.03 5103.77   83.73
IW Dist,WD,Coef,Skew,MaxSub,Min_El,Is_Ogee,SpillHt,DesHd
10,1,3,0,0.95,, 0 ,,,0,0,

Type RM Length L Ch R = 1 ,77436.0 ,102,103,124.5
BEGIN DESCRIPTION:
Cross Section FIELD_DS
Located At: E100_Control Structure US of Houston-Rosslyn
END DESCRIPTION:
XS GIS Cut Line= 5
      3075203.16     13886072.58      3076383.75     13884228.51
      3077835.98     13882930.06      3077885.45     13882796.61
      3077971.47     13878619.63
#Sta/Elev= 30
     793   90.07    1043   91.05    1143   87.45    1253   89.84    1453    85.3
    1753   84.14    1853   86.14  3472.6   84.15  3552.6   82.21  3952.6   83.75
  4562.6   80.33    4885   84.23 4919.75   84.27 4974.54   65.78 5000.89   65.38
 5024.04    65.8 5080.25      84    5120   83.49    5373   80.43    5853   83.52
    6393   82.17    6533   84.73    6773   82.62    7113   86.05    7293   83.75
    7779   85.02    8180   84.77    8793   86.28    9003   83.91  9250.9   86.32
#Mann= 8 ,-1 , 0
     793     .08       0    4885     .04       0 4919.75    .015       0
 5080.25     .04       0    5120     .08       0    7779      .1       0
    8180     .05       0    9003     .08       0
#XS Ineff= 2 , 0
       0                    7112       0   86.07
Permanent Ineff=
       F       F
Bank Sta=4919.75,5080.25
XS Rating Curve= 0 ,0
Exp/Cntr=0.7,0.5

Type RM Length L Ch R = 1 ,77333.  ,867.5,204,203
BEGIN DESCRIPTION:
E100_Control Structure US Houston-Rosslyn-XS -XS 1
END DESCRIPTION:
XS GIS Cut Line= 6
 3076141.640977213886471.7670684 3076953.773380713884495.3537636
 3077943.054848613882964.3440821 3077977.0350552 13882826.829394
 3077980.063809713882684.6630476 3078018.544690613878617.3787622
#Sta/Elev= 30
   792.8   91.33   852.8   89.07  1062.8   90.55  1172.8   87.14  1392.8   88.61
  1722.8   83.76  1812.8   85.78  2312.8   83.18  3502.4   84.35  4552.4   80.07
 4871.85   83.69 4919.97   84.08 4973.98   65.57 4999.95   64.36 5026.11   66.12
 5078.42   83.84    5117   83.55  5302.8    80.3  5952.8   83.59  6372.8   81.78
  6552.8   84.73  6782.8   82.09  7132.8   86.23  7332.8   83.28    7775   85.25
    8205   85.25  8862.8    86.6  9022.8   83.59  9052.8   85.55  9250.7   86.01
#Mann= 8 ,-1 , 0
   792.8     .08       0 4871.85     .04       0 4919.97    .015       0
 5078.42     .04       0    5117     .08       0    7775      .1       0
    8205     .06       0  9052.8     .08       0
#XS Ineff= 2 , 0
       0                    7171       0   86.27
Permanent Ineff=
       F       F
Bank Sta=4919.97,5117
XS Rating Curve= 0 ,0
Exp/Cntr=0.3,0.1