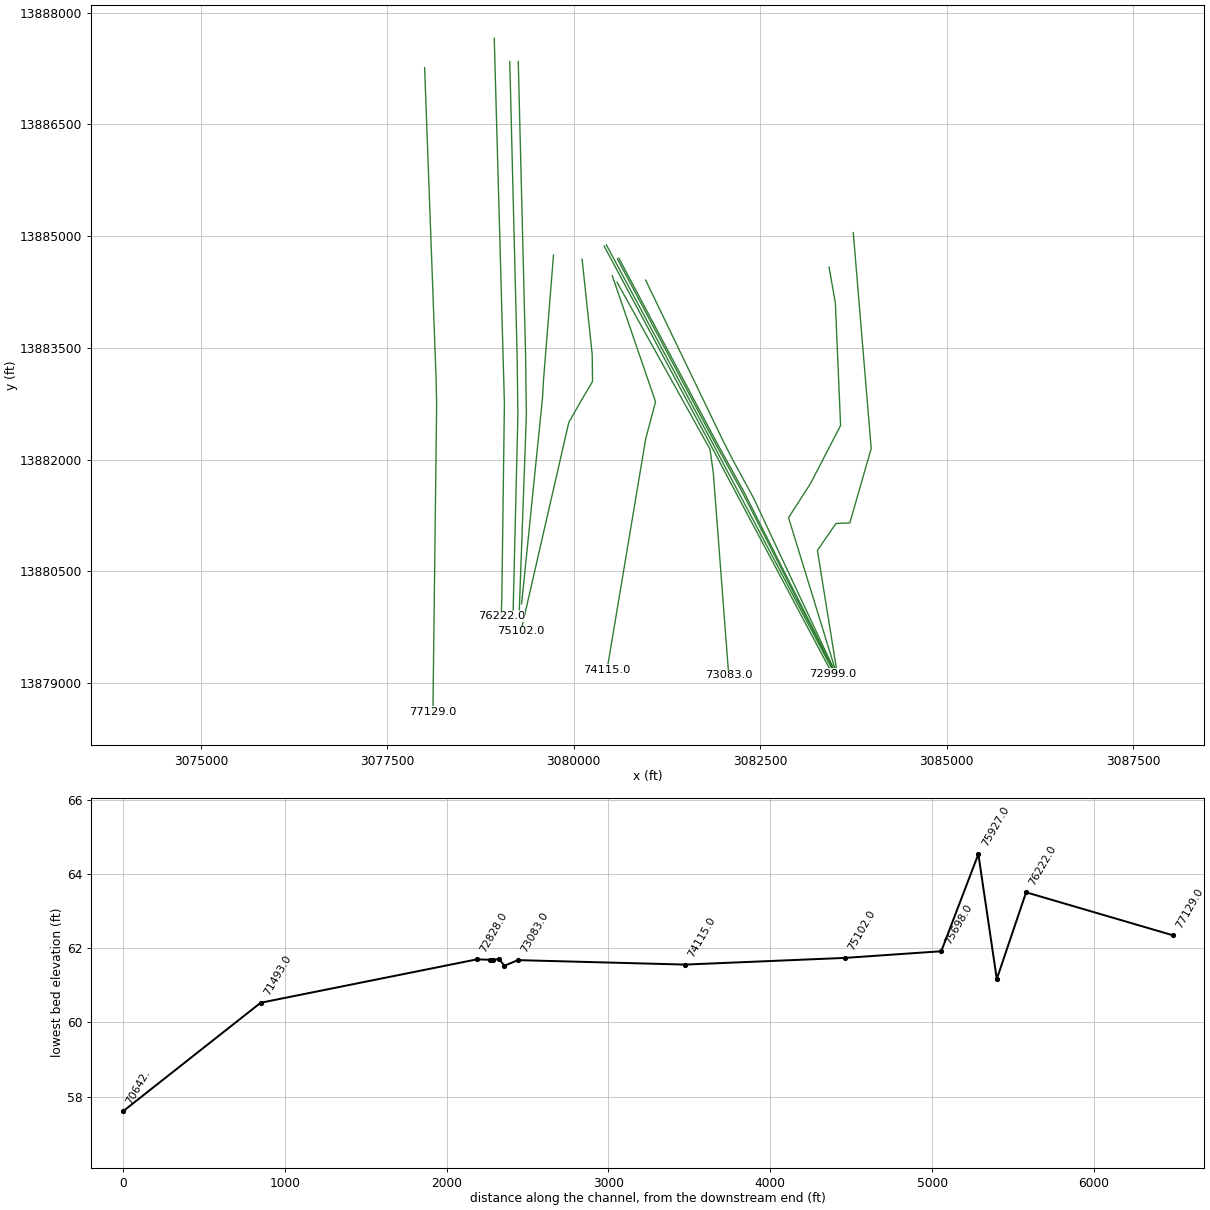
HEC-RAS study E100-00-00.prj: E100-00-00

--- E100-00-00.g02 (geometry) --- (continued)

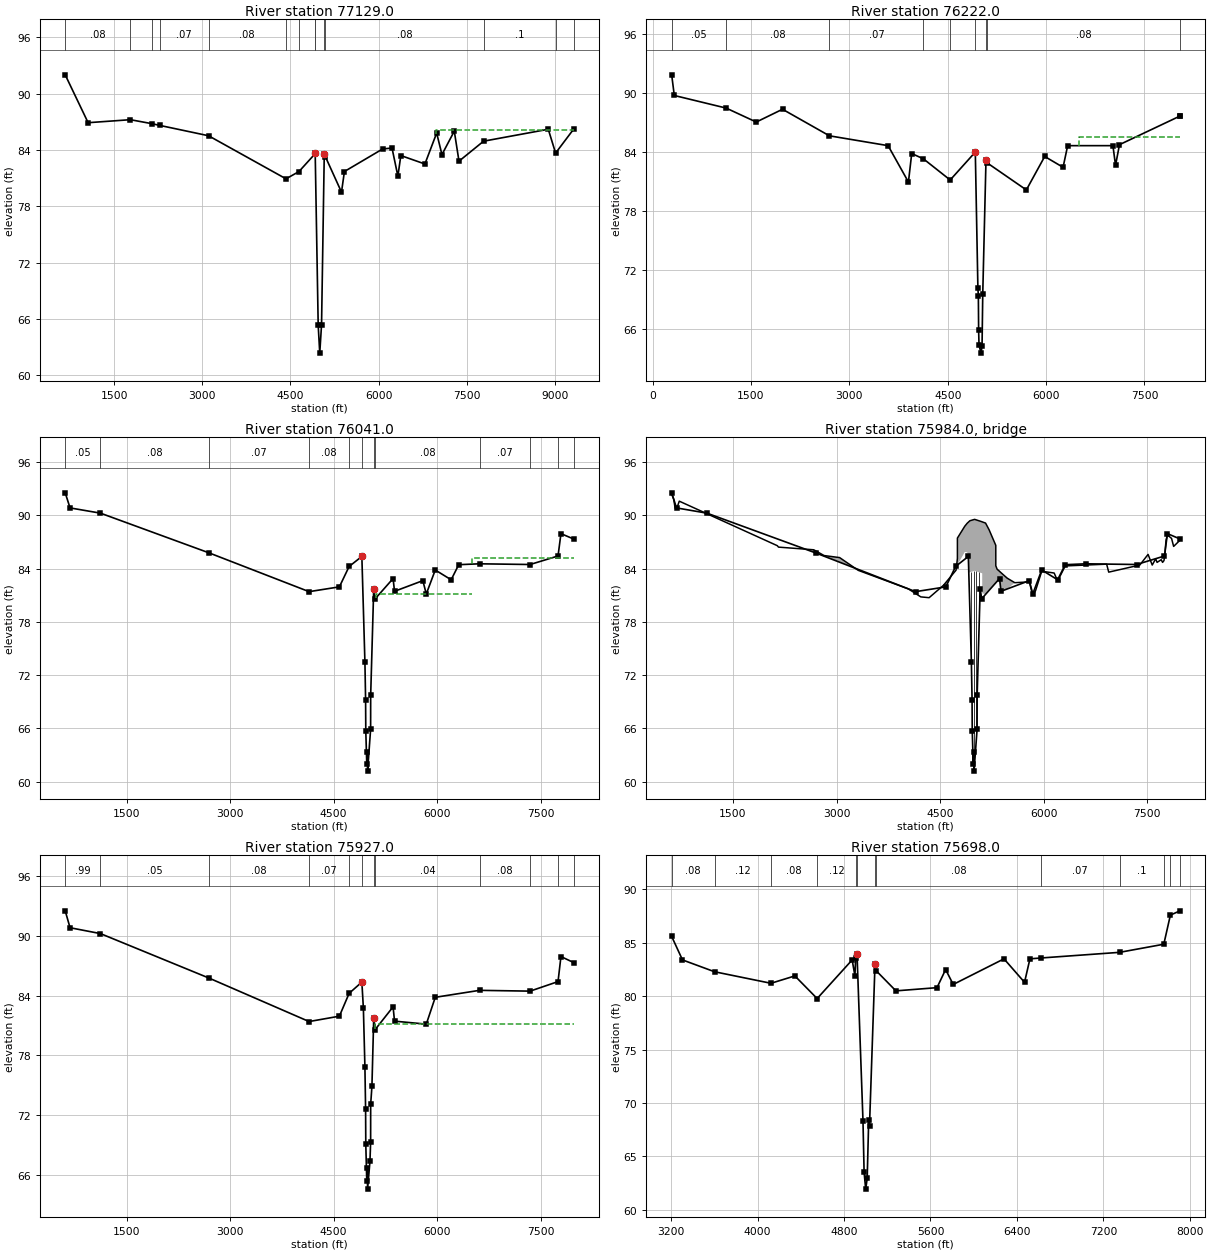
Type RM Length L Ch R = 1 ,77129.0 ,906,907,1034.1
BEGIN DESCRIPTION:
Cross Section E100-00-00-X53
END DESCRIPTION:
XS GIS Cut Line= 4
      3078000.38     13887262.39      3078153.66     13883096.86
       3078161.7     13882742.36      3078111.78     13878612.92
#Sta/Elev= 30
   665.2      92  1055.2    86.9  1774.1   87.22  2137.6    86.8  2275.7   86.61
  3104.8   85.51  4423.7   80.92  4643.3   81.69  4911.3   83.54  4920.4   83.69
  4971.6    65.3  4998.1   62.35  5028.6   65.37  5074.8   83.53  5094.8   83.27
  5368.1    79.5  5418.1    81.7  6068.1    84.1  6228.1    84.2  6328.1    81.2
  6378.1    83.4  6788.1    82.5  6988.1    85.8  7078.1    83.5  7288.1      86
  7368.1    82.8  7786.9   84.93  8888.1    86.2  9012.5   83.66  9317.9    86.2
#Mann= 14 ,-1 , 0
   665.2     .08       0  1774.1     .05       0  2137.6     .08       0
  2275.7     .07       0  3104.8     .08       0  4423.7     .12       0
  4643.3     .08       0  4911.3     .04       0  4920.4     .04       0
  5074.8     .04       0  5094.8     .08       0  7786.9      .1       0
  9012.5     .08       0  9317.9     .99       0
#XS Ineff= 3 ,-1
   665.2  4920.4   83.69  5074.8    6982   83.53    6982  9317.9    86.1
Permanent Ineff=
       F       F       F
Bank Sta=4920.4,5074.8
XS Rating Curve= 0 ,0
Exp/Cntr=0.3,0.1

Type RM Length L Ch R = 1 ,76222.0 ,191.8,181,180
BEGIN DESCRIPTION:
Cross Section E100-00-00-X52B
END DESCRIPTION:
XS GIS Cut Line= 5
       3078934.3     13887656.21      3079060.19     13883120.45
       3079070.4     13882750.21      3079035.57     13880128.57
      3079028.57     13879893.81
#Sta/Elev= 30
   291.1    91.8   331.1    89.7  1121.5   88.42  1581.1      87  1981.1    88.3
  2696.5    85.6  3591.1    84.6  3901.1    80.9  3951.1    83.8  4129.3   83.26
  4537.7   81.11  4920.8   83.95  4960.4    70.1  4967.4   69.31  4971.4   65.87
  4977.5   64.33  5008.2   63.51  5023.6   64.23  5034.3   69.53  5083.9   83.18
  5099.1   82.86    5699    80.1    5979    83.5    6259    82.4    6329    84.6
    7019    84.6    7059    82.6    7119    84.7  8041.8   87.61  8041.9    87.6
#Mann= 9 ,-1 , 0
   291.1     .05       0  1121.5     .08       0  2696.5     .07       0
  4129.3     .08       0  4537.7     .12       0  4920.8     .04       0
  5083.9     .04       0  5099.1     .08       0  8041.8     .99       0
#XS Ineff= 3 ,-1
   291.1  4920.8   83.95  5083.9    6500   83.18    6500  8041.9    85.5
Permanent Ineff=
       F       F       F
Bank Sta=4920.8,5083.9
XS Rating Curve= 0 ,0
Exp/Cntr=0.5,0.3

Type RM Length L Ch R = 1 ,76041.0 ,113,114,116
BEGIN DESCRIPTION:
Upstream Section of Bridge/Culvert/Weir
END DESCRIPTION:
XS GIS Cut Line= 4
       3079142.4     13887341.59      3079240.71     13883402.53
      3079251.32     13882594.14      3079187.63     13879979.98
#Sta/Elev= 30
   612.3   92.54   682.3   90.84  1122.2   90.25  2699.2   85.76  4143.7    81.4
  4582.6   81.94  4723.7   84.24    4908   85.37  4952.3   73.46  4962.1   69.24
  4964.9   65.69  4979.1   61.98  4987.3   63.31  4990.7   61.17    5035    65.9
  5035.7   69.71  5079.7   81.72  5101.5    80.6  5360.2   82.88    5381   81.44
    5791   82.64    5841   81.14    5971   83.84    6201   82.74    6311   84.44
  6611.9   84.54  7344.4   84.46  7748.7   85.42    7791   87.94  7973.2   87.34
#Mann= 12 ,-1 , 0
   612.3     .05       0  1122.2     .08       0  2699.2     .07       0
  4143.7     .08       0  4723.7     .12       0    4908     .04       0
  5079.7     .04       0  5101.5     .08       0  6611.9     .07       0
  7344.4      .1       0  7748.7     .08       0  7973.2     .99       0
#XS Ineff= 3 ,-1
   612.3    4898   80.94 5112.73    6500   81.18    6500  7973.2    85.2
Permanent Ineff=
       F       F       F
Bank Sta=4908,5079.7
XS Rating Curve= 0 ,0
Exp/Cntr=0.5,0.3

Type RM Length L Ch R = 3 ,75984.0 ,,,
BEGIN DESCRIPTION:
N.HOUSTON ROSSLYN
Structure ID: E100-00-00-43
END DESCRIPTION:
Bridge Culvert--1,0,-1,-1, 0
Deck Dist Width WeirC Skew NumUp NumDn MinLoCord MaxHiCord MaxSubmerge Is_Ogee
10,94,2.6,0, 60, 60, , , 0.95, 0, ,,,
   612.3   642.3   662.3   682.3   722.3  2142.3 2159.18  2669.3 2819.34 3044.39
 3314.46 4040.01 4220.15 4340.25 4549.89 4729.93 4749.79  4749.9  4856.9  4891.4
    4908 4914.91    4930  4999.1 5109.09  5109.2  5111.3  5157.7  5208.5  5305.8
 5305.91  5324.9  5360.2    5361    5381    5471    5581    5791    5841    5881
    5971    6151    6201    6311    6911    6941    7391    7511    7571    7621
    7641    7701    7721    7741    7751    7771    7791    7851    7881  7973.2
    92.4    91.8    90.8    90.7    91.6   86.58   86.42   86.12   85.47   85.24
    83.8   81.71   80.81   80.72   82.13   83.82   85.14   87.44   88.78   89.11
   89.23   89.28   89.39   89.55   89.27   89.27   89.26   89.13   88.38   86.62
   84.32   83.93   83.69   83.68   83.54   82.92   82.41    82.5      81    81.5
    83.7    83.5    82.6    84.3    84.5    83.6    84.4    85.6    84.4    85.1
    84.7      85    84.7    84.9    85.4    87.2    87.8    87.4    86.5    87.2
    92.4    91.8    90.8    90.7    91.6    86.3   81.42   81.12   80.47   80.24
    78.8   76.71   75.81   75.72   77.13   78.82   84.19   84.19   85.88   85.83
   85.23   83.35   83.59   83.75   83.47   81.06   81.22   80.81   80.55   81.93
   81.93   82.21   82.74    81.7    81.3    81.4    82.4    82.5      81    81.5
    83.7    83.5    82.6    84.3    84.5    83.6    84.4    85.6    84.4    85.1
    84.7      85    84.7    84.9    85.4    87.2    87.8    87.4    86.5    87.2
   612.3   642.3   662.3   682.3   722.3  2142.3 2159.18  2669.3 2819.34 3044.39
 3314.46 4040.01 4220.15 4340.25 4549.89 4729.93 4749.79  4749.9  4856.9  4891.4
    4908 4914.91    4930  4999.1 5109.09  5109.2  5111.3  5157.7  5208.5  5305.8
 5305.91  5324.9  5360.2    5361    5381    5471    5581    5791    5841    5881
    5971    6151    6201    6311    6911    6941    7391    7511    7571    7621
    7641    7701    7721    7741    7751    7771    7791    7851    7881  7973.2
    92.4    91.8    90.8    90.7    91.6   86.58   86.42   86.12   85.47   85.24
    83.8   81.71   80.81   80.72   82.13   83.82   85.14   87.44   88.78   89.11
   89.23   89.28   89.39   89.55   89.27   89.27   89.26   89.13   88.38   86.62
   84.32   83.93   83.69   83.68   83.54   82.92   82.41    82.5      81    81.5
    83.7    83.5    82.6    84.3    84.5    83.6    84.4    85.6    84.4    85.1
    84.7      85    84.7    84.9    85.4    87.2    87.8    87.4    86.5    87.2
    92.4    91.8    90.8    90.7    91.6    86.3   81.42   81.12   80.47   80.24
    78.8   76.71   75.81   75.72   77.13   78.82   84.19   84.19   85.88   85.83
   85.23   83.35   83.59   83.75   83.47   81.06   81.22   80.81   80.55   81.93
   81.93   82.21   82.74    81.7    81.3    81.4    82.4    82.5      81    81.5
    83.7    83.5    82.6    84.3    84.5    83.6    84.4    85.6    84.4    85.1
    84.7      85    84.7    84.9    85.4    87.2    87.8    87.4    86.5    87.2
Pier Skew, UpSta & Num, DnSta & Num=  ,4952.3, 2 ,4952.3, 2 , 0 , 0 , 0 ,,
     1.4     1.4
   72.01   84.64
     1.4     1.4
   75.64   88.27
Pier Skew, UpSta & Num, DnSta & Num=  ,4987.3, 2 ,4987.3, 2 , 0 , 0 , 0 ,,
     1.4     1.4
   61.73   84.72
     1.4     1.4
   65.36   88.35
Pier Skew, UpSta & Num, DnSta & Num=  ,5022, 2 ,5022, 2 , 0 , 0 , 0 ,,
     1.4     1.4
    62.6   84.69
     1.4     1.4
   66.23   88.32
Pier Skew, UpSta & Num, DnSta & Num=  ,5067.7, 2 ,5067.7, 2 , 0 , 0 , 0 ,,
     1.4     1.4
   77.96   84.57
     1.4     1.4
   81.59    88.2
BR Coef= 1 , 1 , 0 ,1.25, 0 ,,,0.8,-1,2,0,
WSPro=,,,, 1 ,,,, 0 ,,,, 0 ,,,,-1 ,-1 ,-1 , 0 , 0 , 0 , 0 , 0
BR D #Sta/Elev= 112
   612.3   92.54   642.3   91.94   662.3   90.94   682.3   90.84   722.3   91.74
    1120   90.26  1122.2   90.25  2142.3   86.44  2442.3   86.34  2682.3   85.84
  2699.2   85.76  2802.3   85.24    2940   84.96  3052.3   84.74  3112.3   84.04
  3552.3   82.84  3592.3   83.44  3862.3   81.94  3882.3   81.24  3912.3   81.54
  3922.3   81.24  4002.3   82.34  4143.7    81.4  4212.3   80.94  4362.3   81.64
  4422.3   81.54  4582.6   81.94  4658.5   84.01  4707.1   84.18  4723.7   84.24
 4749.79   84.33  4749.9   84.33 4750.01   84.33  4750.7   84.33    4789   85.04
  4795.2   85.15  4856.9   86.02  4879.4   85.99  4891.4   85.97    4908   85.37
 4914.91   83.49    4915   83.46    4930   82.75  4931.8   82.26  4949.8    77.2
  4952.3   76.83    4960   73.37  4962.1   72.61  4964.9   69.06    4965   69.33
  4979.1   65.35  4987.3   66.68  4990.7   64.54  4999.1   65.19  5006.7   65.78
    5022   67.17  5025.3   67.33    5035   69.27  5035.7   73.08  5039.3   73.47
  5053.7   74.87  5057.3   76.06  5067.7   79.32  5071.9   80.34  5079.7   81.72
  5095.9   80.16  5101.5    80.6 5109.09   81.19  5109.2    81.2  5109.3    81.2
  5111.3   81.36  5157.2   80.95  5157.7   80.95  5208.5   80.69  5212.6   80.67
  5261.8   81.41 5305.69   82.06  5305.8   82.07 5305.91   82.07  5324.9   82.35
  5360.2   82.88    5361   81.84    5381   81.44    5471   81.54    5581   82.54
  5736.1   82.61    5791   82.64    5841   81.14    5881   81.64    5971   83.84
    6151   83.64    6201   82.74    6311   84.44  6611.9   84.54    6911   84.64
    6941   83.74  7344.4   84.46    7391   84.54    7511   85.74    7571   84.54
    7621   85.24    7641   84.84    7701   85.14    7721   84.84    7741   85.04
  7748.7   85.42    7751   85.54    7771   87.34    7791   87.94    7851   87.54
    7881   86.64  7973.2   87.34
BR D #Mann= 11
   612.3     .99  1122.2     .05  2699.2     .08  4143.7     .07  4723.7     .08
    4908     .04  5079.7     .04  5101.5     .04  6611.9     .08  7344.4     .07
  7748.7      .1
BC Design=,, 0 ,, 0 ,,,,,,
BC HTab HWMax=92.54
BC Use User HTab Curves=0
BC User HTab FreeFlow(D)= 0

Type RM Length L Ch R = 1 ,75927.0 ,278.5,229,179.1
BEGIN DESCRIPTION:
Downstream Section of Bridge/Culvert/Weir
END DESCRIPTION:
XS GIS Cut Line= 4
      3079256.04     13887345.44      3079354.35      13883406.2
      3079364.97     13882597.07      3079270.38     13879981.73
#Sta/Elev= 30
   612.3   92.54   682.3   90.84  1122.2   90.25  2699.2   85.76  4143.7    81.4
  4582.6   81.94  4723.7   84.24    4908   85.37    4930   82.75  4952.3   76.83
  4962.1   72.61  4964.9   69.06  4979.1   65.35  4987.3   66.68  4990.7   64.54
  5025.3   67.33    5035   69.27  5035.7   73.08  5053.7   74.87  5079.7   81.72
  5101.5    80.6  5360.2   82.88    5381   81.44    5841   81.14    5971   83.84
  6611.9   84.54  7344.4   84.46  7748.7   85.42    7791   87.94  7973.2   87.34
#Mann= 12 ,-1 , 0
   612.3     .99       0  1122.2     .05       0  2699.2     .08       0
  4143.7     .07       0  4723.7     .08       0    4908     .04       0
  5079.7     .04       0  5101.5     .04       0  6611.9     .08       0
  7344.4     .07       0  7748.7      .1       0  7973.2     .08       0
#XS Ineff= 2 , 0
       0 4901.33   80.94 5105.45       0   81.18
Permanent Ineff=
       F       F
Bank Sta=4908,5079.7
XS Rating Curve= 0 ,0
Exp/Cntr=0.5,0.3

Type RM Length L Ch R = 1 ,75698.0 ,644.6,596,348.2
BEGIN DESCRIPTION:
Cross Section E100-00-00-X52A
END DESCRIPTION:
XS GIS Cut Line= 4
      3079728.73     13884745.05      3079594.35     13883062.35
       3079582.1     13882835.85      3079301.41     13880063.93
#Sta/Elev= 30
  3205.2    85.6  3305.2    83.4  3602.1   82.29  4123.9   81.21  4345.2    81.9
  4551.1   79.78  4875.2    83.4  4900.7   81.91  4907.5   83.54  4920.1   83.96
  4975.3   68.33  4985.6   63.51  5000.4   61.92  5014.3   62.92  5028.3   68.42
  5035.7   67.87  5086.7   83.02  5099.8   82.36  5280.1    80.5  5660.1    80.8
  5740.1    82.5  5810.1    81.1  6280.1    83.5  6470.1    81.3  6520.1    83.5
  6621.2   83.58    7350   84.11  7758.7   84.87  7819.6    87.6  7908.6      88
#Mann= 13 ,-1 , 0
  3205.2     .08       0  3602.1     .12       0  4123.9     .08       0
  4551.1     .12       0  4907.5     .04       0  4920.1     .04       0
  5086.7     .04       0  5099.8     .08       0  6621.2     .07       0
    7350      .1       0  7758.7     .12       0  7819.6     .08       0
  7908.6     .99       0
#XS Ineff= 2 , 0
       0 4818.18   80.94 5087.43       0   81.37
Permanent Ineff=
       F       F
Bank Sta=4920.1,5086.7
XS Rating Curve= 0 ,0
Exp/Cntr=0.6,0.4

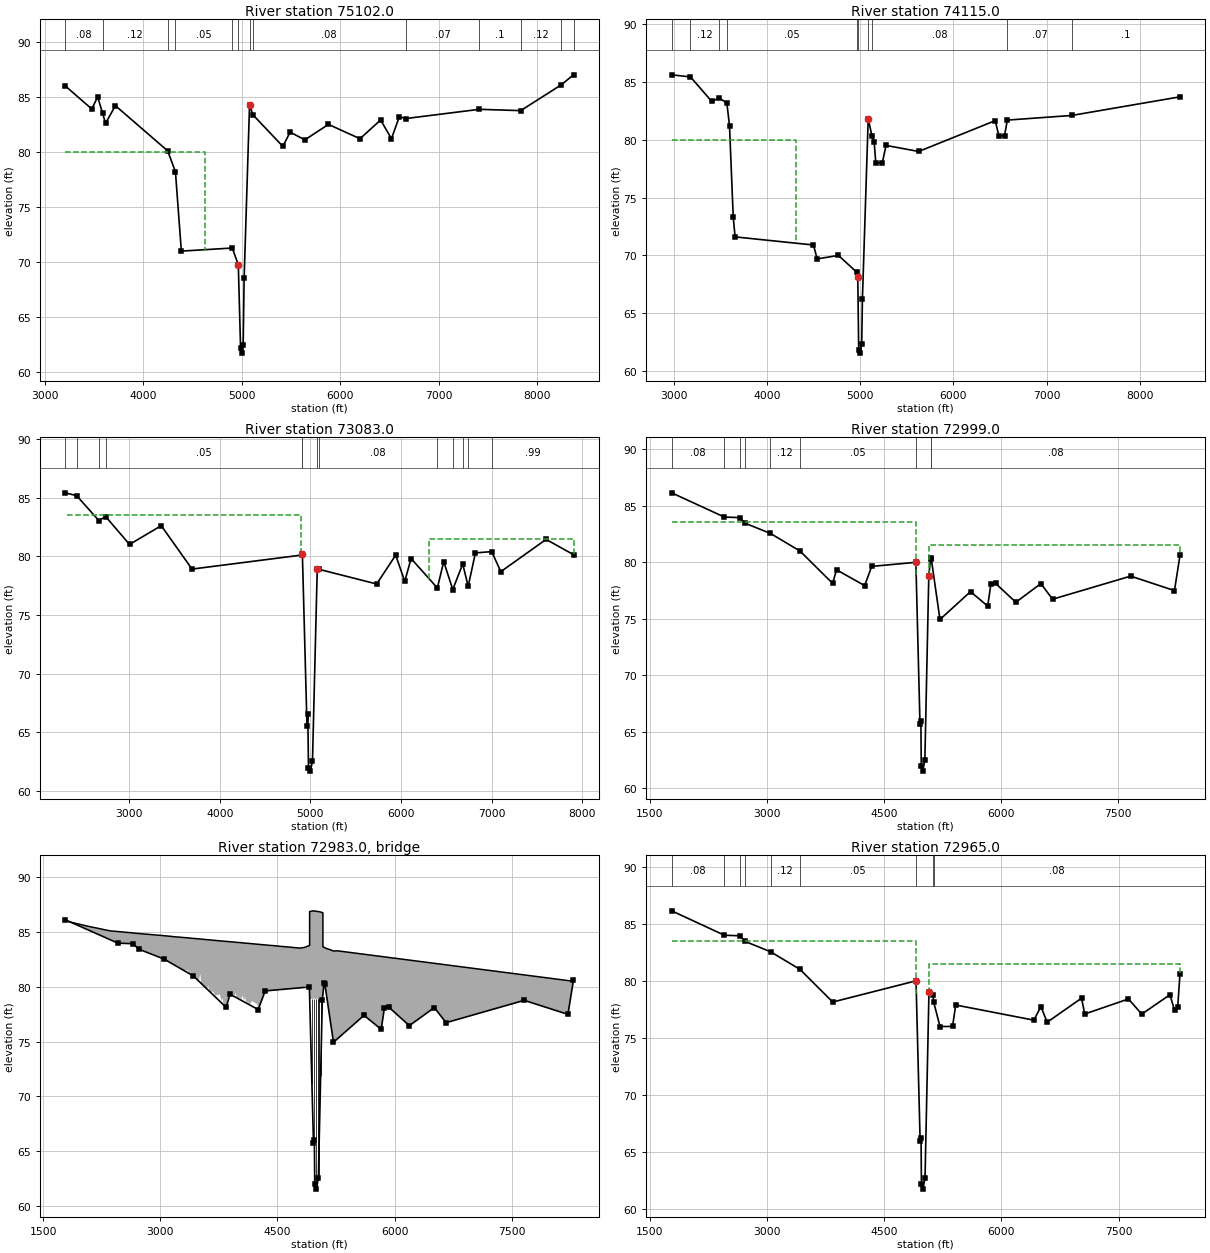
Type RM Length L Ch R = 1 ,75102.0 ,924.3,987,988
BEGIN DESCRIPTION:
Cross Section E100-00-00-X52
END DESCRIPTION:
XS GIS Cut Line= 6
      3080112.38     13884689.72      3080247.65     13883414.32
      3080252.48     13883047.16       3080103.2      13882796.1
      3079933.74     13882497.89      3079291.47     13879691.67
#Sta/Elev= 30
  3205.7      86  3475.7    83.9  3535.7      85    3586   83.49  3615.7    82.6
  3715.7    84.2  4246.8    80.1  4325.7    78.2  4385.7      71  4903.3   71.28
  4964.5   69.75  4987.6   62.17  4998.2   61.74  5013.8   62.49  5023.6   68.53
  5078.7   84.28  5111.9   83.38  5417.5    80.5  5490.5    81.8  5640.5    81.1
  5880.5    82.5  6200.5    81.2  6410.5    82.9  6520.5    81.2  6600.5    83.2
  6663.7   83.03  7414.6   83.87  7833.6   83.75  8243.9   86.08  8370.5      87
#Mann= 13 ,-1 , 0
  3205.7     .08       0    3586     .12       0  4246.8     .04       0
  4325.7     .05       0  4903.3     .04       0  4964.5     .04       0
  5078.7     .04       0  5111.9     .08       0  6663.7     .07       0
  7414.6      .1       0  7833.6     .12       0  8243.9     .08       0
  8370.5     .99       0
#XS Ineff= 2 , 0
       0  4628.3      80               0
Permanent Ineff=
       F       F
Bank Sta=4964.5,5078.7
XS Rating Curve= 0 ,0
Exp/Cntr=0.6,0.4

Type RM Length L Ch R = 1 ,74115.0 ,714.2,1032,999
BEGIN DESCRIPTION:
Cross Section E100-00-00-X51
END DESCRIPTION:
XS GIS Cut Line= 4
      3080517.47      13884466.2      3081097.15     13882774.77
       3080965.8     13882281.63      3080446.44     13879173.49
#Sta/Elev= 30
  2979.6    85.6  3181.1   85.42  3409.6    83.3  3488.8    83.6  3571.5   83.16
  3599.6    81.2  3639.6    73.3  3659.6    71.6  4499.6    70.9  4539.6    69.7
  4767.7      70    4962   68.56  4974.8   68.14  4984.7   61.79  4998.9   61.56
  5016.8   62.35  5024.5   66.23  5086.6   81.81  5126.3   80.34  5150.6   79.79
  5167.7      78  5237.7      78  5277.7    79.5    5628   78.98    6448   81.64
    6488   80.32    6548   80.33    6578   81.69    7268   82.09  8429.3    83.7
#Mann= 10 ,-1 , 0
  2979.6     .08       0  3181.1     .12       0  3488.8     .04       0
  3571.5     .05       0    4962     .04       0  4974.8     .04       0
  5086.6     .04       0  5126.3     .08       0    6578     .07       0
    7268      .1       0
#XS Ineff= 2 , 0
       0  4313.4      80               0
Permanent Ineff=
       F       F
Bank Sta=4974.8,5086.6
XS Rating Curve= 0 ,0
Exp/Cntr=0.3,0.1

Type RM Length L Ch R = 1 ,73083.0 ,47.9,84,225.5
BEGIN DESCRIPTION:
Cross Section E100-00-00-X50B
END DESCRIPTION:
XS GIS Cut Line= 4
        3080581.      13884380.5       3081827.6     13882136.96
      3081871.97     13881819.07      3082078.38     13879104.04
#Sta/Elev= 30
  2293.8    85.4  2419.4   85.16  2664.8   83.04    2740   83.38  3003.8      81
  3353.8    82.6  3693.8    78.9  4908.4    80.1  4911.5   80.19  4962.3   65.55
    4971   66.55  4978.9   61.98  4998.6   61.68    5023   62.51  5075.7   78.95
  5089.7   78.89  5731.4   77.63  5941.4   80.09  6041.4   77.85  6111.4    79.8
  6401.4   77.29  6471.4   79.54  6571.4   77.16  6681.4   79.34  6741.4   77.43
  6821.4   80.28  7001.4   80.39  7101.4   78.68  7601.4   81.43  7904.3   80.13
#Mann= 13 ,-1 , 0
  2293.8     .08       0  2419.4     .12       0  2664.8     .04       0
    2740     .05       0  4908.4     .04       0  4911.5    .015       0
  5075.7     .04       0  5089.7     .08       0  6401.4      .1       0
  6571.4     .12       0  6681.4     .07       0  6741.4     .12       0
  7001.4     .99       0
#XS Ineff= 2 ,-1
 2308.65 4893.46    83.5    6310  7904.3    81.5
Permanent Ineff=
       F       F
Bank Sta=4911.5,5075.7
XS Rating Curve= 0 ,0
Exp/Cntr=0.5,0.3

Type RM Length L Ch R = 1 ,72999.0 ,39,34,40.7
BEGIN DESCRIPTION:
Upstream Section of Bridge/Culvert/Weir
END DESCRIPTION:
XS GIS Cut Line= 4
      3080407.54      13884865.8      3081829.81     13882208.23
      3082039.83     13881808.85        3083467.     13879123.62
#Sta/Elev= 30
  1783.2   86.12  2457.1   83.98  2652.4   83.93  2724.7   83.43    3048   82.53
  3425.2   80.98  3843.2   78.12  3893.2   79.32  4253.2   77.92  4343.2   79.62
  4908.6   79.98  4961.3   65.72  4972.9      66  4977.6      62  4997.3   61.53
  5023.8   62.53  5074.1    78.8    5097   80.34    5107   80.24    5217   74.93
  5608.2   77.39  5828.2   76.11  5868.2   78.03  5928.2   78.12  6188.2   76.45
  6508.2    78.1  6658.2   76.72  7658.2   78.76  8218.2   77.48  8289.2    80.6
#Mann= 9 ,-1 , 0
  1783.2     .08       0  2457.1     .12       0  2652.4     .04       0
  2724.7     .05       0    3048     .12       0  3425.2     .05       0
  4908.6    .015       0    5097     .04       0    5107     .08       0
#XS Ineff= 2 , 0
       0    4913    83.5    5074       0    81.5
Permanent Ineff=
       F       F
Bank Sta=4908.6,5074.1
XS Rating Curve= 0 ,0
Exp/Cntr=0.5,0.3

Type RM Length L Ch R = 3 ,72983.0 ,,,
BEGIN DESCRIPTION:
BURLINGTON NORTHERN R.R.
Structure ID: E100-00-00-42
END DESCRIPTION:
Bridge Culvert--1,0,-1,-1, 0
Deck Dist Width WeirC Skew NumUp NumDn MinLoCord MaxHiCord MaxSubmerge Is_Ogee
10,12,3,0, 126, 126, 82.5, , 0.95, 0, 4,4,,
  1783.2  1819.5  2113.2  2143.2  2173.2  2283.2  2323.2  2359.5  2373.2  2457.1
  2473.2  2573.2  2583.2  2643.2  2652.4  2693.2  2724.7    3048  3123.2  3173.2
  3223.2  3243.2  3303.2  3323.2  3353.2  3373.2  3383.2  3425.2  3493.2  3513.2
  3523.2  3553.2  3593.2  3613.2  3633.2  3653.2  3673.2  3703.2  3763.2  3783.2
  3793.2  3813.2  3833.2  3843.2  3893.2  3943.2  3963.2  3983.2  4023.2  4033.2
  4053.2  4073.2  4083.2  4103.2  4123.2  4143.2  4173.2  4243.2  4253.2  4323.2
  4343.2  4413.2  4423.2  4453.2  4473.2  4513.2  4523.2  4553.2  4603.2  4653.2
  4724.5  4791.2  4809.2  4841.2  4852.3  4896.4  4908.6 4911.59  4911.7 4911.81
  4912.7 4913.01  4913.1  4913.2  4931.8  4941.2  4946.6  4961.3    4965  4969.1
  4969.5  4972.9    4976  4976.1  4977.6  4997.3  4998.1  5004.6  5021.5  5023.8
  5023.9  5024.8  5047.3  5052.6    5054  5058.3  5068.2  5074.1  5080.6 5080.69
  5080.8  5081.6 5081.89    5082 5082.11  5091.2  5095.8  5129.6  5132.8    5175
  5177.4  5220.1  5220.8  5266.5  5268.7    8290
    86.1   85.95   85.46   85.42   85.38   85.21   85.15    85.1   85.09   85.04
   85.03   84.96   84.96   84.92   84.91   84.88   84.86   84.66   84.61   84.57
   84.54   84.53   84.49   84.48   84.46   84.45   84.44   84.41   84.37   84.36
   84.35   84.33    84.3   84.29   84.28   84.26   84.25   84.23   84.19   84.18
   84.17   84.16   84.15   84.14   84.11   84.08   84.06   84.05   84.03   84.02
   84.01   83.99   83.99   83.97   83.96   83.95   83.93   83.88   83.88   83.83
   83.82   83.77   83.77   83.75   83.74   83.71    83.7   83.68   83.65   83.62
   83.57   83.53   83.55   83.58   83.61   83.73   83.76   83.77   86.87   86.87
   86.87   86.87   86.87   86.87   86.89    86.9   86.91   86.93   86.93   86.92
   86.92   86.92   86.92   86.92   86.91   86.89   86.89   86.88   86.86   86.86
   86.86   86.86   86.83   86.82   86.82   86.81   86.78   86.77   86.75   86.75
   86.75   86.75   86.75   86.75   83.65   83.62    83.6   83.49   83.48   83.38
   83.37   83.26   83.26   83.28   83.28    80.5
    86.1   85.94    84.6    84.1    84.8    83.7    84.5   84.35    84.3   83.96
    83.9    83.9    83.5      84   83.91    83.5   83.41   82.51    82.3    81.5
    81.9    81.3    81.2    81.5    81.5    80.8    81.3   80.96    80.4    81.2
    80.3    79.5    79.6    80.1    79.5    79.2    79.6    79.2    79.3    78.7
      79    78.2    78.4    78.1    79.3    78.7    79.4    78.7      79    78.7
    79.2    78.7    79.1    78.5    78.6    78.3    78.7    78.4    77.9      79
    79.6      79    79.2    78.1      79    78.9    79.4    78.9    79.3    79.2
      10      10   79.79   80.01   80.09   79.43   79.96   79.17   79.14   79.11
   78.87   78.79   78.87   78.87   78.89    78.9   78.91   78.93   78.93   78.92
   78.92   78.92   78.92   78.92   78.91   78.89   78.89   78.88   78.86   78.86
   78.86   78.86   78.83   78.82   78.82   78.81   78.78   78.78
                                                                                
                                                
  1783.2  1819.5  2113.2  2143.2  2173.2  2283.2  2323.2  2359.5  2373.2  2457.1
  2473.2  2573.2  2583.2  2643.2  2652.4  2693.2  2724.7    3048  3123.2  3173.2
  3223.2  3243.2  3303.2  3323.2  3353.2  3373.2  3383.2  3425.2  3493.2  3513.2
  3523.2  3553.2  3593.2  3613.2  3633.2  3653.2  3673.2  3703.2  3763.2  3783.2
  3793.2  3813.2  3833.2  3843.2  3893.2  3943.2  3963.2  3983.2  4023.2  4033.2
  4053.2  4073.2  4083.2  4103.2  4123.2  4143.2  4173.2  4243.2  4253.2  4323.2
  4343.2  4413.2  4423.2  4453.2  4473.2  4513.2  4523.2  4553.2  4603.2  4653.2
  4724.5  4791.2  4809.2  4841.2  4852.3  4896.4  4908.6 4911.59  4911.7 4911.81
  4912.7 4913.01  4913.1  4913.2  4931.8  4941.2  4946.6  4961.3    4965  4969.1
  4969.5  4972.9    4976  4976.1  4977.6  4997.3  4998.1  5004.6  5021.5  5023.8
  5023.9  5024.8  5047.3  5052.6    5054  5058.3  5068.2  5074.1  5080.6 5080.69
  5080.8  5081.6 5081.89    5082 5082.11  5091.2  5095.8  5129.6  5132.8    5175
  5177.4  5220.1  5220.8  5266.5  5268.7    8290
    86.1   85.95   85.46   85.42   85.38   85.21   85.15    85.1   85.09   85.04
   85.03   84.96   84.96   84.92   84.91   84.88   84.86   84.66   84.61   84.57
   84.54   84.53   84.49   84.48   84.46   84.45   84.44   84.41   84.37   84.36
   84.35   84.33    84.3   84.29   84.28   84.26   84.25   84.23   84.19   84.18
   84.17   84.16   84.15   84.14   84.11   84.08   84.06   84.05   84.03   84.02
   84.01   83.99   83.99   83.97   83.96   83.95   83.93   83.88   83.88   83.83
   83.82   83.77   83.77   83.75   83.74   83.71    83.7   83.68   83.65   83.62
   83.57   83.53   83.55   83.58   83.61   83.73   83.76   83.77   86.87   86.87
   86.87   86.87   86.87   86.87   86.89    86.9   86.91   86.93   86.93   86.92
   86.92   86.92   86.92   86.92   86.91   86.89   86.89   86.88   86.86   86.86
   86.86   86.86   86.83   86.82   86.82   86.81   86.78   86.77   86.75   86.75
   86.75   86.75   86.75   86.75   83.65   83.62    83.6   83.49   83.48   83.38
   83.37   83.26   83.26   83.28   83.28    80.5
    86.1   85.94    84.6    84.1    84.8    83.7    84.5   84.35    84.3   83.96
    83.9    83.9    83.5      84   83.91    83.5   83.41   82.51    82.3    81.5
    81.9    81.3    81.2    81.5    81.5    80.8    81.3   80.96    80.4    81.2
    80.3    79.5    79.6    80.1    79.5    79.2    79.6    79.2    79.3    78.7
      79    78.2    78.4    78.1    79.3    78.7    79.4    78.7      79    78.7
    79.2    78.7    79.1    78.5    78.6    78.3    78.7    78.4    77.9      79
    79.6      79    79.2    78.1      79    78.9    79.4    78.9    79.3    79.2
      10      10   79.79   80.01   80.09   79.43   79.96   79.17   79.14   79.11
   78.87   78.79   78.87   78.87   78.89    78.9   78.91   78.93   78.93   78.92
   78.92   78.92   78.92   78.92   78.91   78.89   78.89   78.88   78.86   78.86
   78.86   78.86   78.83   78.82   78.82   78.81   78.78   78.78
                                                                                
                                                
Pier Skew, UpSta & Num, DnSta & Num=  ,4941.2, 2 ,4941.2, 2 , 0 , 0 , 0 ,,
     1.4     1.4
   70.84    79.9
     1.4     1.4
   71.04    80.1
Pier Skew, UpSta & Num, DnSta & Num=  ,4969.5, 2 ,4969.5, 2 , 0 , 0 , 0 ,,
     1.4     1.4
   64.85   79.92
     1.4     1.4
   65.05   80.12
Pier Skew, UpSta & Num, DnSta & Num=  ,4997.3, 2 ,4997.3, 2 , 0 , 0 , 0 ,,
     1.4     1.4
   60.53   79.89
     1.4     1.4
   60.73   80.09
Pier Skew, UpSta & Num, DnSta & Num=  ,5024.8, 2 ,5024.8, 2 , 0 , 0 , 0 ,,
     1.4     1.4
   61.63   79.86
     1.4     1.4
   61.83   80.06
Pier Skew, UpSta & Num, DnSta & Num=  ,5052.6, 2 ,5052.6, 2 , 0 , 0 , 0 ,,
     1.4     1.4
   70.73   79.82
     1.4     1.4
   70.93   80.02
Abutment Skew #Up #Dn= , 2 , 2
  4912.9  4976.1
   78.87   62.53
  4912.9  4976.1
   79.07   62.73
Abutment Skew #Up #Dn= , 2 , 2
  5023.9 5080.89
   62.55   78.75
  5023.9 5080.89
   62.75   78.95
BR Coef= 1 , 1 , 0 ,1.25, 0 ,,,0.8,0,1.2,0,
WSPro=,,,, 1 ,,,, 0 ,,,, 0 ,,,,-1 ,-1 ,-1 , 0 , 0 , 0 , 0 , 0
BC Design=,, 0 ,, 0 ,,,,,,
BC HTab HWMax=86.12
BC Use User HTab Curves=0
BC User HTab FreeFlow(D)= 0

Type RM Length L Ch R = 1 ,72965.0 ,36.6,34,58
BEGIN DESCRIPTION:
Downstream Section of Bridge/Culvert/Weir
END DESCRIPTION:
XS GIS Cut Line= 4
      3080437.65      13884881.6      3081859.98     13882223.86
      3082079.04     13881807.26      3083490.14     13879138.34
#Sta/Elev= 30
  1783.2   86.12  2457.1   83.98  2652.4   83.93  2724.7   83.43    3048   82.53
  3425.2   80.98  3843.2   78.12  4908.6   79.98  4961.3    65.9  4972.9   66.18
  4977.6   62.18  4997.3   61.71  5023.8   62.71  5074.1   78.98  5125.3   78.76
  5135.3   78.09  5215.3   75.97    5376   75.98    5416   77.86    6416   76.53
    6506   77.72    6586   76.35    7026   78.46    7066   77.07    7626   78.39
    7796   77.06    8156   78.76    8216   77.38    8256   77.71    8285   80.62
#Mann= 9 ,-1 , 0
  1783.2     .08       0  2457.1     .12       0  2652.4     .04       0
  2724.7     .05       0    3048     .12       0  3425.2     .05       0
  4908.6    .015       0  5125.3     .04       0  5135.3     .08       0
#XS Ineff= 2 , 0
       0    4913    83.5    5074       0    81.5
Permanent Ineff=
       F       F
Bank Sta=4908.6,5074.1
XS Rating Curve= 0 ,0
Exp/Cntr=0.5,0.3

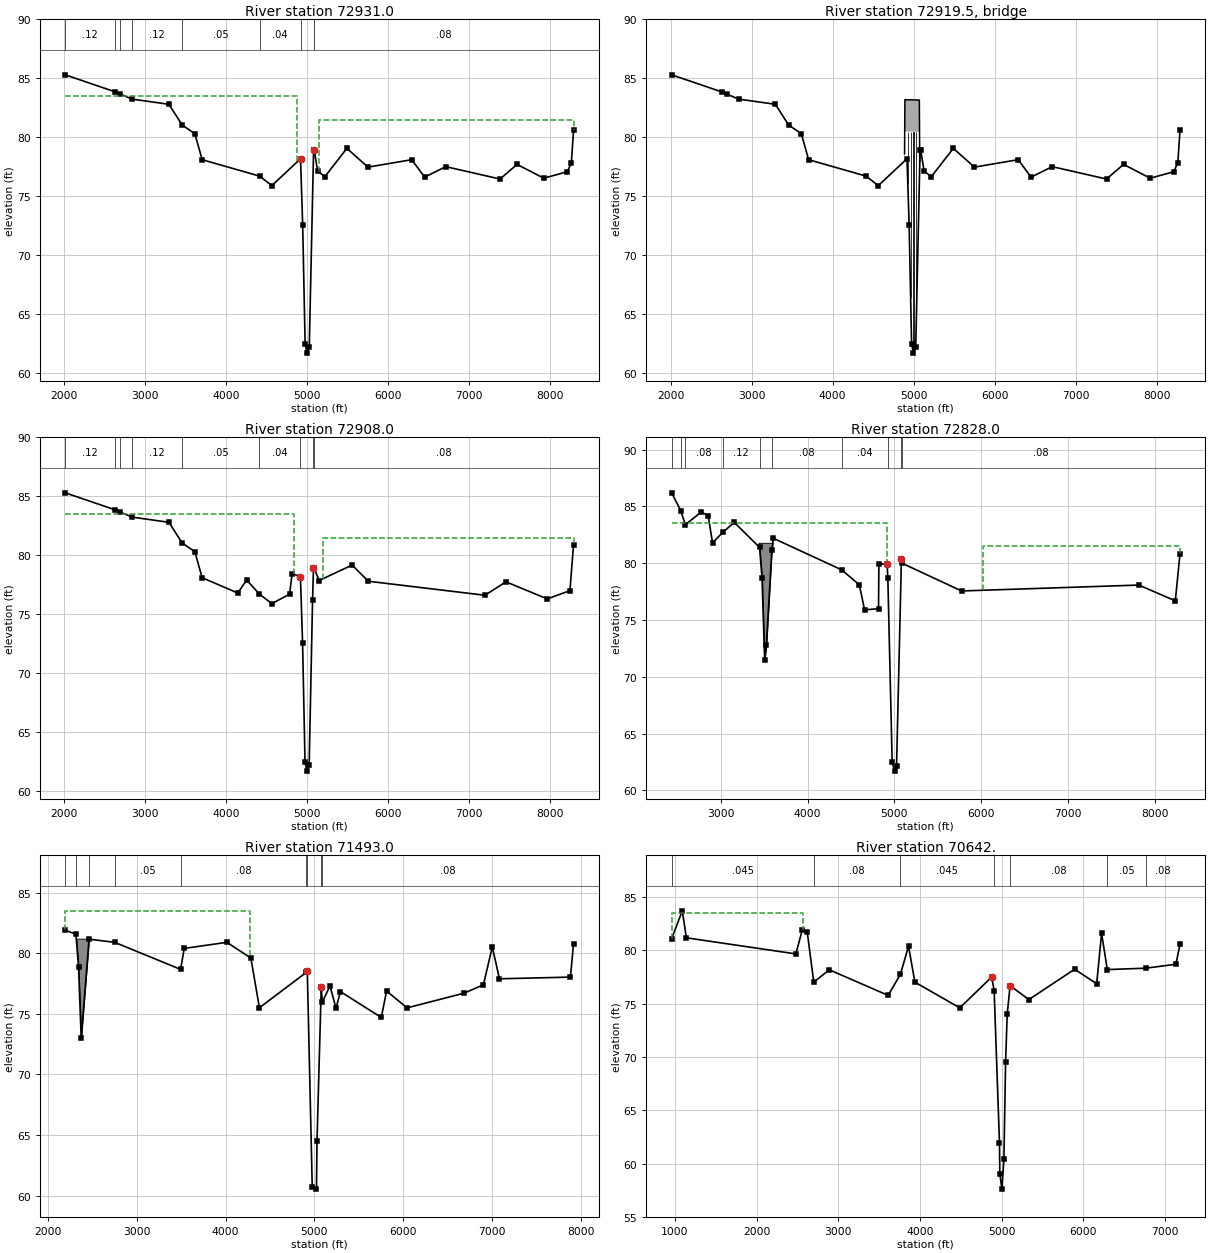
Type RM Length L Ch R = 1 ,72931.0 ,25,23,44.3
BEGIN DESCRIPTION:
Upstream Section of Bridge/Culvert/Weir
END DESCRIPTION:
XS GIS Cut Line= 4
      3080585.45      13884694.3      3081894.44     13882224.58
      3082247.35      13881584.8      3083498.55      13879139.4
#Sta/Elev= 30
  2013.7    85.3  2632.5   83.85  2695.4   83.66  2839.5   83.24  3293.7    82.8
  3456.3   81.05  3613.7    80.3  3703.7    78.1  4411.6   76.71  4563.7    75.9
  4917.7   78.18  4944.2   72.56  4974.3   62.48  4997.6   61.69  5025.4    62.2
    5079   78.91  5085.9   78.95  5129.2   77.12  5219.2   76.67  5489.2   79.06
  5749.8   77.47  6289.8    78.1  6449.8   76.62  6709.8   77.51  7379.8   76.46
  7589.8    77.7  7919.8   76.53  8209.8   77.08  8259.8   77.84  8286.7    80.6
#Mann= 9 ,-1 , 0
  2013.7     .12       0  2632.5     .04       0  2695.4     .08       0
  2839.5     .12       0  3456.3     .05       0  4411.6     .04       0
  4917.7    .015       0    5079     .04       0  5085.9     .08       0
#XS Ineff= 2 , 0
       0 4872.75    83.5  5147.4       0    81.5
Permanent Ineff=
       F       F
Bank Sta=4917.7,5079
XS Rating Curve= 0 ,0
Exp/Cntr=0.5,0.3

Type RM Length L Ch R = 3 ,72919.5 ,,,
BEGIN DESCRIPTION:
65FT DS BURLINGTON NORTHERN R.R.
Structure ID: E100-00-00-41b
END DESCRIPTION:
Bridge Culvert--1,0,-1,-1, 0
Deck Dist Width WeirC Skew NumUp NumDn MinLoCord MaxHiCord MaxSubmerge Is_Ogee
10,3,2.6,0, 27, 27, , , 0.95, 0, ,,,
  4887.4  4891.9 4892.24 4892.33  4892.9  4911.4  4912.8  4917.7  4927.6  4944.2
  4950.8  4962.7  4966.3  4974.3  4978.2  4997.6  4998.4  5025.4  5025.8  5032.4
  5050.4  5064.9  5067.4 5069.89    5070  5070.1  5074.8
   78.59   83.19   83.19   83.19   83.19   83.19   83.19   83.19   83.18   83.18
   83.18   83.18   83.18   83.18   83.18   83.17   83.17   83.17   83.17   83.17
   83.16   83.16   83.16   83.16   83.16   83.16   77.92
   78.42    78.4    78.4   80.49   80.49   80.49   80.49   80.49   80.48   80.48
   80.48   80.48   80.48   80.48   80.48   80.47   80.47   80.47   80.47   80.47
   80.46   80.46   80.46   80.46   76.79   76.82      74
  4887.4  4891.9 4892.24 4892.33  4892.9  4911.4  4912.8  4917.7  4927.6  4944.2
  4950.8  4962.7  4966.3  4974.3  4978.2  4997.6  4998.4  5025.4  5025.8  5032.4
  5050.4  5064.9  5067.4 5069.89    5070  5070.1  5074.8
   78.59   83.19   83.19   83.19   83.19   83.19   83.19   83.19   83.18   83.18
   83.18   83.18   83.18   83.18   83.18   83.17   83.17   83.17   83.17   83.17
   83.16   83.16   83.16   83.16   83.16   83.16   77.92
   78.42    78.4    78.4   80.49   80.49   80.49   80.49   80.49   80.48   80.48
   80.48   80.48   80.48   80.48   80.48   80.47   80.47   80.47   80.47   80.47
   80.46   80.46   80.46   80.46   76.79   76.82      74
Pier Skew, UpSta & Num, DnSta & Num=  ,4927.6, 2 ,4927.6, 2 , 0 , 0 , 0 ,,
     1.4     1.4
   75.03   81.48
     1.4     1.4
   75.03   81.48
Pier Skew, UpSta & Num, DnSta & Num=  ,4962.7, 2 ,4962.7, 2 , 0 , 0 , 0 ,,
     1.4     1.4
   65.23   81.48
     1.4     1.4
   65.23   81.48
Pier Skew, UpSta & Num, DnSta & Num=  ,4998.4, 2 ,4998.4, 2 , 0 , 0 , 0 ,,
     1.4     1.4
   60.69   81.47
     1.4     1.4
   60.69   81.47
Pier Skew, UpSta & Num, DnSta & Num=  ,5032.4, 2 ,5032.4, 2 , 0 , 0 , 0 ,,
     1.4     1.4
   63.35   81.47
     1.4     1.4
   63.35   81.47
BR Coef= 1 , 1 , 0 ,1.25, 0 ,,,0.8,-1,2,0,
WSPro=,,,, 1 ,,,, 0 ,,,, 0 ,,,,-1 ,-1 ,-1 , 0 , 0 , 0 , 0 , 0
BC Design=,, 0 ,, 0 ,,,,,,
BC HTab HWMax=85.7
BC Use User HTab Curves=0
BC User HTab FreeFlow(D)= 0

Type RM Length L Ch R = 1 ,72908.0 ,109.4,80,148.7
BEGIN DESCRIPTION:
Downstream Section of Bridge/Culvert/Weir
END DESCRIPTION:
XS GIS Cut Line= 4
      3080604.63      13884704.6      3081913.51     13882235.19
       3082274.9     13881580.02      3083505.91     13879138.34
#Sta/Elev= 30
  2012.8    85.3  2632.5   83.85  2695.4   83.66  2839.5   83.24  3293.7    82.8
  3456.3   81.05  3613.7    80.3  3703.7    78.1  4143.7    76.8  4253.7    77.9
  4411.6   76.71  4563.7    75.9  4783.7    76.7  4815.3   78.45  4917.7   78.18
  4944.2   72.56  4974.3   62.48  4997.6   61.69  5025.4    62.2  5067.4   76.18
    5079   78.91  5085.9   78.95  5147.7   77.86    5556   79.17    5756    77.8
    7196   76.61    7456   77.75    7966    76.3    8246      77  8290.4   80.88
#Mann= 9 ,-1 , 0
  2012.8     .12       0  2632.5     .04       0  2695.4     .08       0
  2839.5     .12       0  3456.3     .05       0  4411.6     .04       0
  4917.7    .015       0    5079     .04       0  5085.9     .08       0
#XS Ineff= 2 , 0
       0 4843.05    83.5 5199.36       0    81.5
Permanent Ineff=
       F       F
Bank Sta=4917.7,5079
XS Rating Curve= 0 ,0
Exp/Cntr=0.5,0.3

Type RM Length L Ch R = 1 ,72828.0 ,1604.2,1335,780.8
BEGIN DESCRIPTION:
Cross Section E100-00-00-X50A
END DESCRIPTION:
XS GIS Cut Line= 5
      3080964.11      13884409.2      3081996.19     13882263.97
      3082131.47     13881998.29      3082411.97     13881481.89
      3083509.06     13879142.55
#Sta/Elev= 30
  2436.5    86.2  2541.3   84.63  2593.1    83.4  2776.5    84.5  2856.5    84.2
  2906.5    81.8  3025.1   82.72  3156.5    83.6  3447.8    81.4  3476.5    78.7
  3506.5    71.5  3526.5    72.8    3589   81.15  3606.5    82.2  4392.8   79.42
  4596.5    78.1  4656.5    75.9  4817.2      76  4821.3   79.94  4916.2   79.92
  4924.3    78.7  4974.4   62.46  5003.7    61.7  5024.4   62.12  5080.7   80.37
  5091.1   79.99    5773   77.56    7813   78.08    8233   76.69  8286.8   80.85
#Mann= 10 ,-1 , 0
  2436.5     .12       0  2541.3     .04       0  2593.1     .08       0
  3025.1     .12       0  3447.8     .04       0    3589     .08       0
  4392.8     .04       0  4924.3    .015       0  5080.7     .04       0
  5091.1     .08       0
#XS Ineff= 2 , 0
       0  4916.2    83.5 6023.33       0    81.5
Permanent Ineff=
       F       F
#Block Obstruct= 1 ,-1
  3436.5  3601.9    81.8
Bank Sta=4916.2,5080.7
XS Rating Curve= 0 ,0
Exp/Cntr=0.3,0.1

Type RM Length L Ch R = 1 ,71493.0 ,549.7,851,780.4
BEGIN DESCRIPTION:
Cross Section E100-00-00-X49
END DESCRIPTION:
XS GIS Cut Line= 6
      3083423.88      13884584.3      3083508.58     13884101.28
      3083578.58     13882456.63       3083172.9     13881673.35
      3082880.53     13881219.46       3083516.2     13879150.16
#Sta/Elev= 30
  2194.4    81.9  2314.7   81.57  2344.4    78.9  2374.4      73  2463.1   81.16
  2751.1    80.9  3493.4   78.67  3534.9    80.4  4014.9    80.9  4284.9    79.6
    4381    75.5  4910.9   78.43  4920.3   78.52    4976    60.7  5023.6   60.53
  5029.5    64.5  5077.5   77.21  5089.3   75.98  5176.1    77.3  5243.4   75.46
  5293.4   76.83  5753.3    74.7  5813.3   76.88  6043.3   75.49  6683.3    76.7
  6903.3   77.39  7003.3   80.53  7083.3   77.89  7883.3   78.03    7918    80.8
#Mann= 9 ,-1 , 0
  2194.4     .08       0  2314.7     .04       0  2463.1     .08       0
  2751.1     .05       0  3493.4     .08       0  4910.9     .04       0
  4920.3     .04       0  5077.5     .04       0  5089.3     .08       0
#XS Ineff= 2 , 0
       0  4279.5    83.5               0
Permanent Ineff=
       F       F
#Block Obstruct= 2 ,-1
  2316.2  2464.4    81.2  2464.5  2464.6      70
Bank Sta=4920.3,5077.5
XS Rating Curve= 0 ,0
Exp/Cntr=0.3,0.1

Type RM Length L Ch R = 1 ,70642.  ,50,170,227.6
BEGIN DESCRIPTION:
PL_41a - U/S - XS 4
END DESCRIPTION:
XS GIS Cut Line= 6
      3083748.61      13885046.7       3083989.2     13882148.66
      3083702.63     13881148.59      3083517.21     13881141.58
      3083267.62     13880779.39      3083530.01     13879150.16
#Sta/Elev= 30
   960.7    81.1  1090.7    83.7  1140.7   81.17  2480.7   79.66  2560.7   81.92
  2620.7    81.7  2700.7   77.01  2890.7   78.17  3610.7   75.77  3760.7   77.73
  3860.7   80.38  3938.8   77.01  4488.8    74.6  4878.8   77.49  4909.1    76.2
 4974.52   61.92 4978.44   59.05 5004.75    57.6 5028.81   60.47  5049.1   69.51
  5069.1   74.02  5104.6   76.67  5334.7   75.38  5894.5   78.22  6164.5   76.86
  6224.5   81.59  6294.5   78.19  6764.5   78.32  7134.5   78.69  7184.7   80.55
#Mann= 7 ,-1 , 0
   960.7    .045       0  2700.7     .08       0  3760.7    .045       0
  4909.1     .04       0  5104.6     .08       0  6294.5     .05       0
  6764.5     .08       0
#XS Ineff= 2 , 0
       0    2570    83.5               0
Permanent Ineff=
       F       F
Bank Sta=4878.8,5104.6
XS Rating Curve= 0 ,0
Exp/Cntr=0.5,0.3