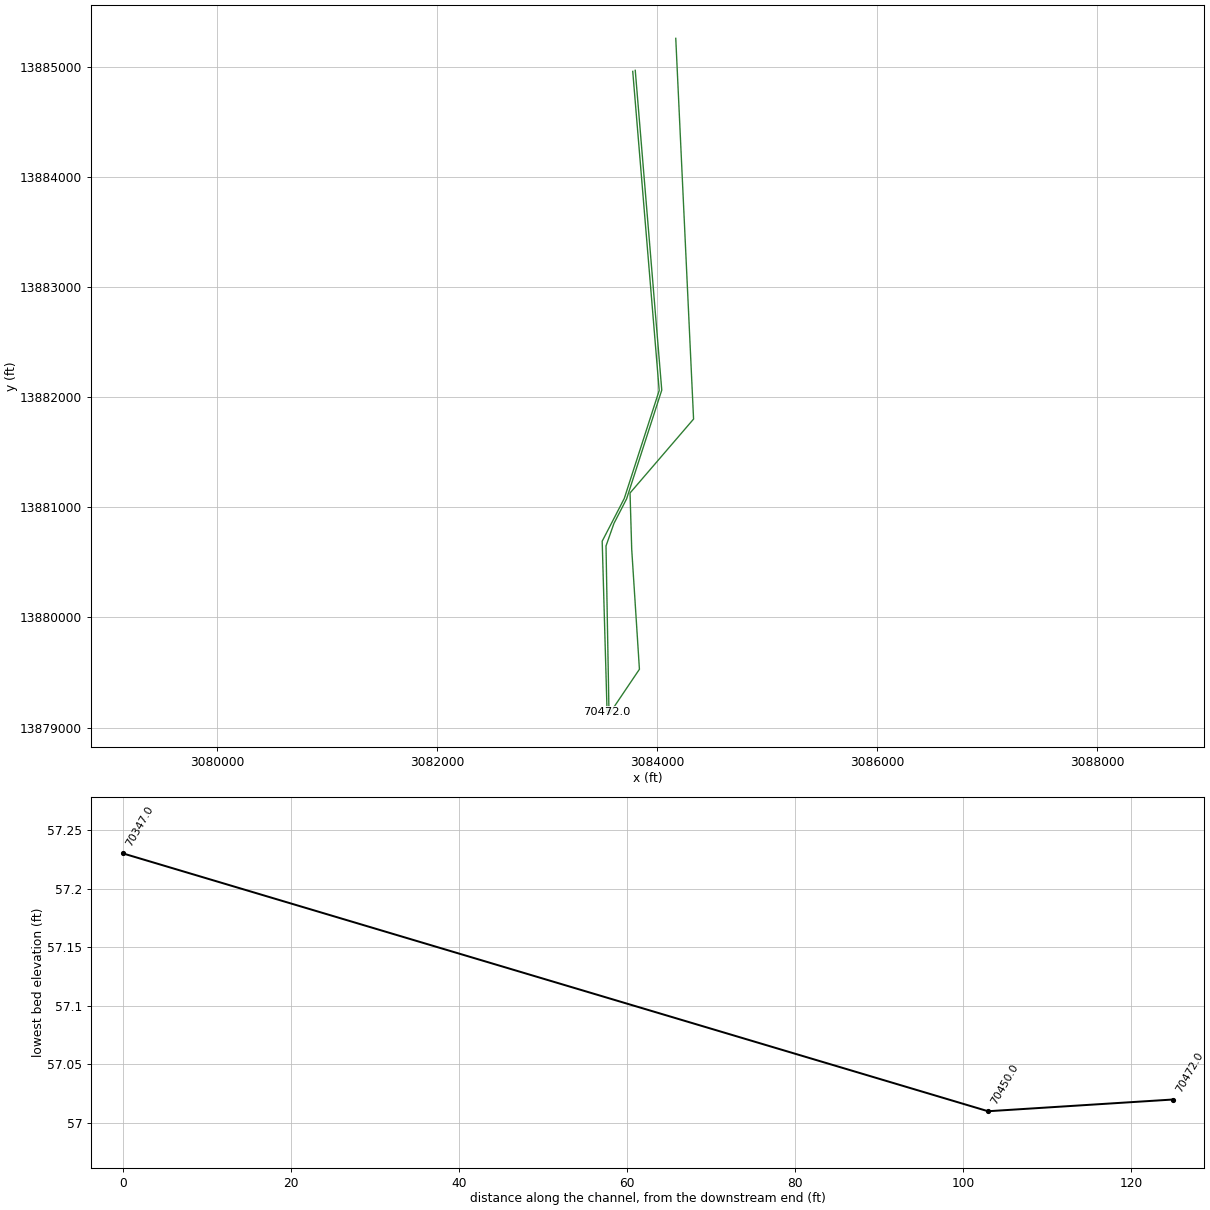
HEC-RAS study E100-00-00.prj: E100-00-00

--- E100-00-00.g02 (geometry) --- (continued)

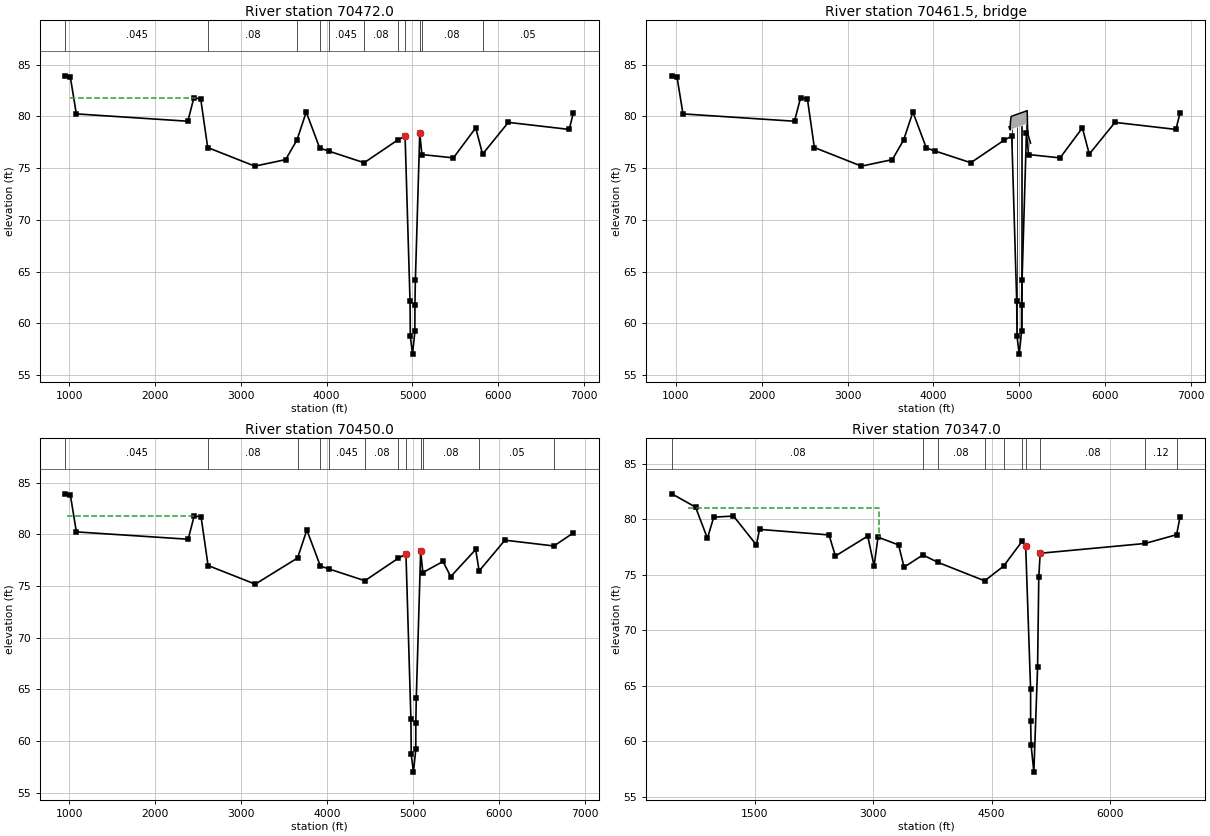
Type RM Length L Ch R = 1 ,70472.0 ,21.8,22,36.3
BEGIN DESCRIPTION:
Upstream Section of Bridge/Culvert/Weir
END DESCRIPTION:
XS GIS Cut Line= 6
      3083779.74       13884959.      3084020.33     13882060.93
      3083702.98       13881081.      3083591.38     13880864.55
      3083501.99     13880692.58      3083546.33     13879145.14
#Sta/Elev= 30
     952   83.92  1011.7   83.81  1081.7   80.24  2381.7   79.53  2451.7   81.79
  2531.7   81.69  2613.1   76.99  3161.7   75.19  3521.7   75.82    3654   77.72
  3761.7   80.42  3918.7   76.94  4022.1   76.65  4436.9   75.52  4827.1   77.71
 4914.18   78.09 4971.68   62.18 4975.48   58.74 5000.98   57.02 5028.38   59.22
 5028.78    61.8 5034.08   64.15 5085.18   78.39  5110.3   76.31  5477.5   75.99
  5737.5   78.89  5817.5   76.35  6117.5   79.42  6827.5   78.74  6875.5   80.32
#Mann= 11 ,-1 , 0
     952    .045       0  2613.1     .08       0    3654    .045       0
  3918.7     .08       0  4022.1    .045       0  4436.9     .08       0
  4827.1     .04       0 4914.18     .04       0 5085.18     .04       0
  5110.3     .08       0  5817.5     .05       0
#XS Ineff= 3 ,-1
  1007.1  2477.8   81.79 5085.18  8000.3   78.39  2477.8 4914.18    76.4
Permanent Ineff=
       F       F       F
Bank Sta=4914.18,5085.18
XS Rating Curve= 0 ,0
Exp/Cntr=0.5,0.3

Type RM Length L Ch R = 3 ,70461.5 ,,,
BEGIN DESCRIPTION:
PL1_E100-00-00-41a
END DESCRIPTION:
Bridge Culvert--1,0,-1,-1, 0
Deck Dist Width WeirC Skew NumUp NumDn MinLoCord MaxHiCord MaxSubmerge Is_Ogee
10,1,2.6,0, 35, 35, , , 0.95, 0, ,,,
  4882.8  4892.8 4895.08 4895.19 4895.28 4899.18 4906.68 4914.18 4920.78 4936.48
 4958.68 4971.68 4972.78 4973.88 4975.48 5000.98 5026.58 5027.28 5028.38 5028.78
 5034.08 5056.88 5075.38 5083.58 5085.18 5093.88 5100.07 5100.18 5100.28 5100.38
  5110.3 5112.48 5116.98  5133.3  5133.8
      79   78.71   78.89   78.91   78.92    79.5      80   80.02   80.04   80.09
   80.15   80.19   80.19    80.2    80.2   80.28   80.35   80.35   80.36   80.36
   80.37   80.44    80.5   80.52   80.52   80.55    78.4   78.36   78.36   78.35
   78.07   78.01   77.88   77.43   77.42
      79    78.7   78.63   78.63   78.62   78.51   78.75   78.77   78.79   78.84
    78.9   78.94   78.94   78.95   78.95   79.03    79.1    79.1   79.11   79.11
   79.12   79.19   79.25   79.27   79.27    79.3   77.85   77.84   77.84   77.82
   76.28   75.94   76.82   77.42   77.42
  4882.8  4892.8 4895.08 4895.19 4895.28 4899.18 4906.68 4914.18 4920.78 4936.48
 4958.68 4971.68 4972.78 4973.88 4975.48 5000.98 5026.58 5027.28 5028.38 5028.78
 5034.08 5056.88 5075.38 5083.58 5085.18 5093.88 5100.07 5100.18 5100.28 5100.38
  5110.3 5112.48 5116.98  5133.3  5133.8
      79   78.71   78.89   78.91   78.92    79.5      80   80.02   80.04   80.09
   80.15   80.19   80.19    80.2    80.2   80.28   80.35   80.35   80.36   80.36
   80.37   80.44    80.5   80.52   80.52   80.55    78.4   78.36   78.36   78.35
   78.07   78.01   77.88   77.43   77.42
      79    78.7   78.63   78.63   78.62   78.51   78.75   78.77   78.79   78.84
    78.9   78.94   78.94   78.95   78.95   79.03    79.1    79.1   79.11   79.11
   79.12   79.19   79.25   79.27   79.27    79.3   77.85   77.84   77.84   77.82
   76.28   75.94   76.82   77.42   77.42
Pier Skew, UpSta & Num, DnSta & Num=  ,4920.8, 2 ,4920.8, 2 , 0 , 0 , 0 ,,
     1.8     1.8
   74.96   79.79
     1.8     1.8
   74.96   79.79
Pier Skew, UpSta & Num, DnSta & Num=  ,4975.5, 2 ,4975.5, 2 , 0 , 0 , 0 ,,
     1.8     1.8
   57.65   79.95
     1.8     1.8
   57.65   79.95
Pier Skew, UpSta & Num, DnSta & Num=  ,5028.4, 2 ,5028.4, 2 , 0 , 0 , 0 ,,
     1.8     1.8
   58.93   80.11
     1.8     1.8
   58.93   80.11
Pier Skew, UpSta & Num, DnSta & Num=  ,5083.6, 2 ,5083.6, 2 , 0 , 0 , 0 ,,
     1.8     1.8
   76.97   80.27
     1.8     1.8
   76.97   80.27
BR Coef= 1 , 1 , 0 ,1.25, 0 ,,,0.8,-1,2,0,
WSPro=,,,, 1 ,,,, 0 ,,,, 0 ,,,,-1 ,-1 ,-1 , 0 , 0 , 0 , 0 , 0
BC Design=,, 0 ,, 0 ,,,,,,
BC HTab HWMax=83.92
BC Use User HTab Curves=0
BC User HTab FreeFlow(D)= 0

Type RM Length L Ch R = 1 ,70450.0 ,320.7,103,260.7
BEGIN DESCRIPTION:
Downstream Section of Bridge/Culvert/Weir
END DESCRIPTION:
XS GIS Cut Line= 6
      3083802.59      13884968.5      3084043.68     13882064.46
      3083723.73     13881076.47      3083608.96     13880853.89
      3083536.72     13880649.18      3083563.91     13879133.84
#Sta/Elev= 30
   951.7   83.91  1011.7    83.8  1081.7   80.23  2381.7   79.52  2451.7   81.78
  2531.7   81.68  2613.1   76.98  3161.7   75.18    3654   77.71  3761.7   80.41
  3918.7   76.93  4022.1   76.64  4436.9   75.51  4827.1    77.7 4914.18   78.08
 4971.68   62.17 4975.48   58.73 5000.98   57.01 5028.38   59.21 5028.78   61.79
 5034.08   64.14 5085.18   78.38  5110.3    76.3  5344.8   77.37  5434.8   75.91
  5724.8   78.53  5764.8   76.45  6064.8   79.43  6634.8   78.87  6860.4   80.13
#Mann= 12 ,-1 , 0
   951.7    .045       0  2613.1     .08       0    3654    .045       0
  3918.7     .08       0  4022.1    .045       0  4436.9     .08       0
  4827.1     .04       0 4914.18     .04       0 5085.18     .04       0
  5110.3     .08       0  5764.8     .05       0  6634.8     .08       0
#XS Ineff= 3 ,-1
  967.14  2477.8   81.79 5085.18  8037.4   78.38  2477.8 4914.18    76.4
Permanent Ineff=
       F       F       F
Bank Sta=4914.18,5085.18
XS Rating Curve= 0 ,0
Exp/Cntr=0.5,0.3

Type RM Length L Ch R = 1 ,70347.0 ,76,81,74.6
BEGIN DESCRIPTION:
Upstream Section of Bridge/Culvert/Weir
END DESCRIPTION:
XS GIS Cut Line= 6
      3084170.92       13885259.      3084332.84     13881801.57
      3083755.23     13881130.13      3083770.34     13880621.17
      3083840.54     13879529.39      3083570.18     13879128.82
#Sta/Elev= 30
   451.8   82.28   751.8   81.08   901.8   78.28   981.8   80.18  1231.8   80.28
  1521.8   77.68  1561.8   79.08  2441.8   78.58  2521.8   76.68  2931.8   78.48
  3011.8   75.78  3061.8   78.38  3321.8   77.68  3391.8   75.68  3629.8   76.78
  3820.6   76.11  4411.8   74.45  4651.5   75.77    4887   78.02  4931.4   77.57
  4993.4    64.7    4994   61.82  5000.1   59.64  5034.8   57.23    5082   66.67
  5097.1   74.78  5114.7   76.93  6441.8   77.81  6841.8    78.6  6885.1   80.19
#Mann= 10 ,-1 , 0
   451.8     .08       0  3629.8    .045       0  3820.6     .08       0
  4411.8    .045       0  4651.5     .08       0    4887     .04       0
  4931.4     .04       0  5114.7     .08       0  6441.8     .12       0
  6841.8     .08       0
#XS Ineff= 3 ,-1
  653.64 3069.27   80.98 3069.27  4931.4    76.4  5114.7  7595.5    76.4
Permanent Ineff=
       F       F       F
Bank Sta=4931.4,5114.7
XS Rating Curve= 0 ,0
Exp/Cntr=0.5,0.3