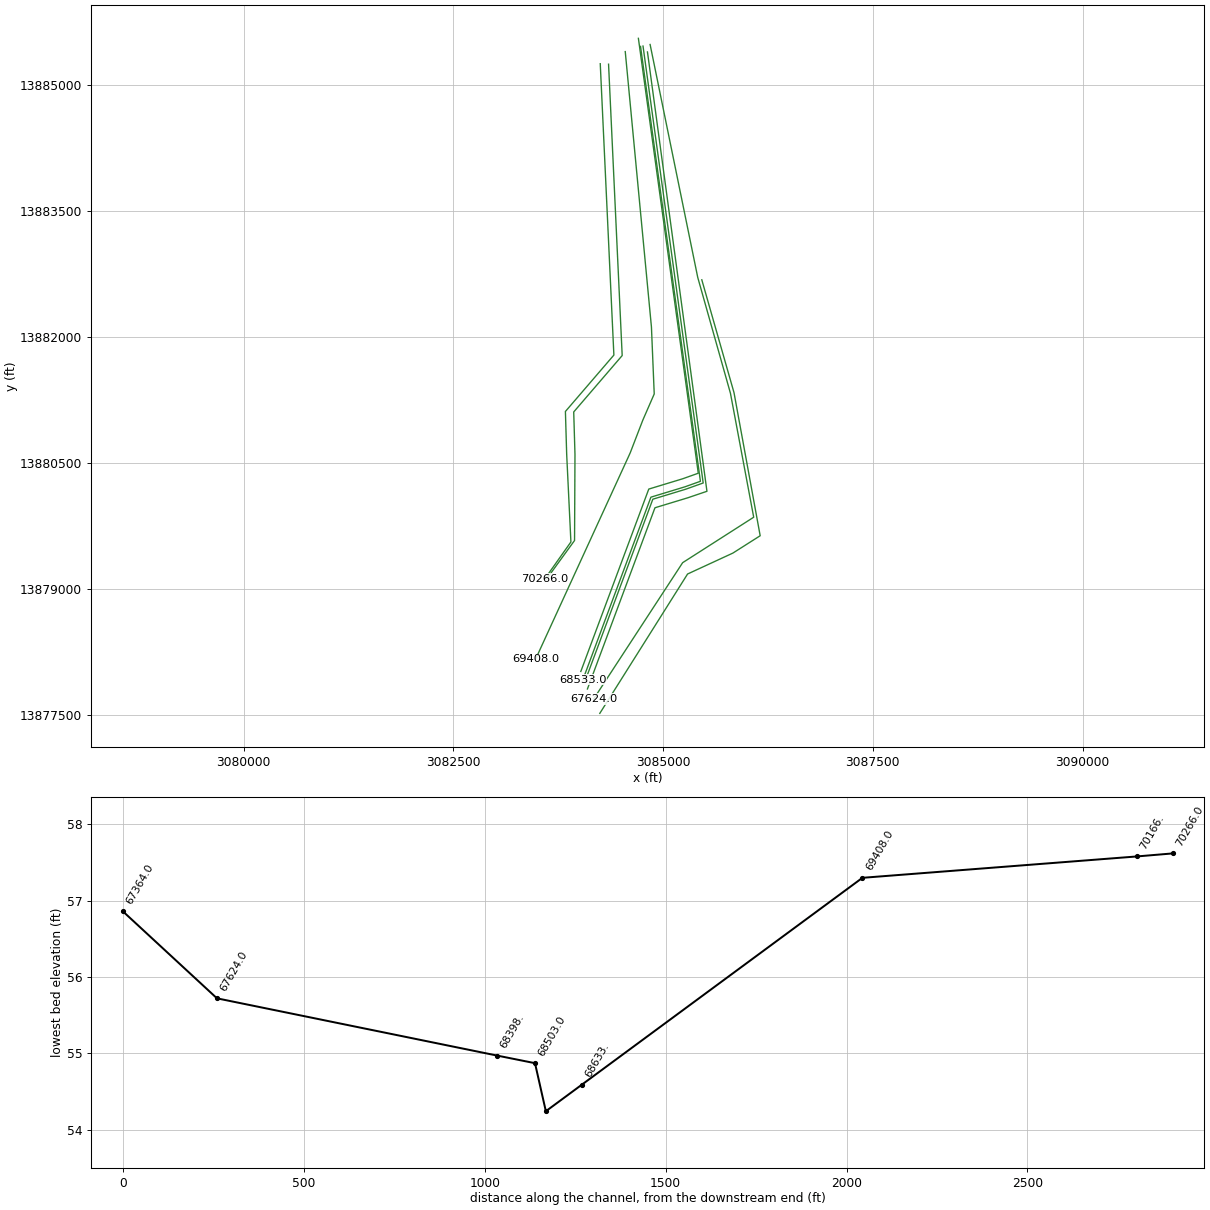
HEC-RAS study E100-00-00.prj: E100-00-00

--- E100-00-00.g02 (geometry) --- (continued)

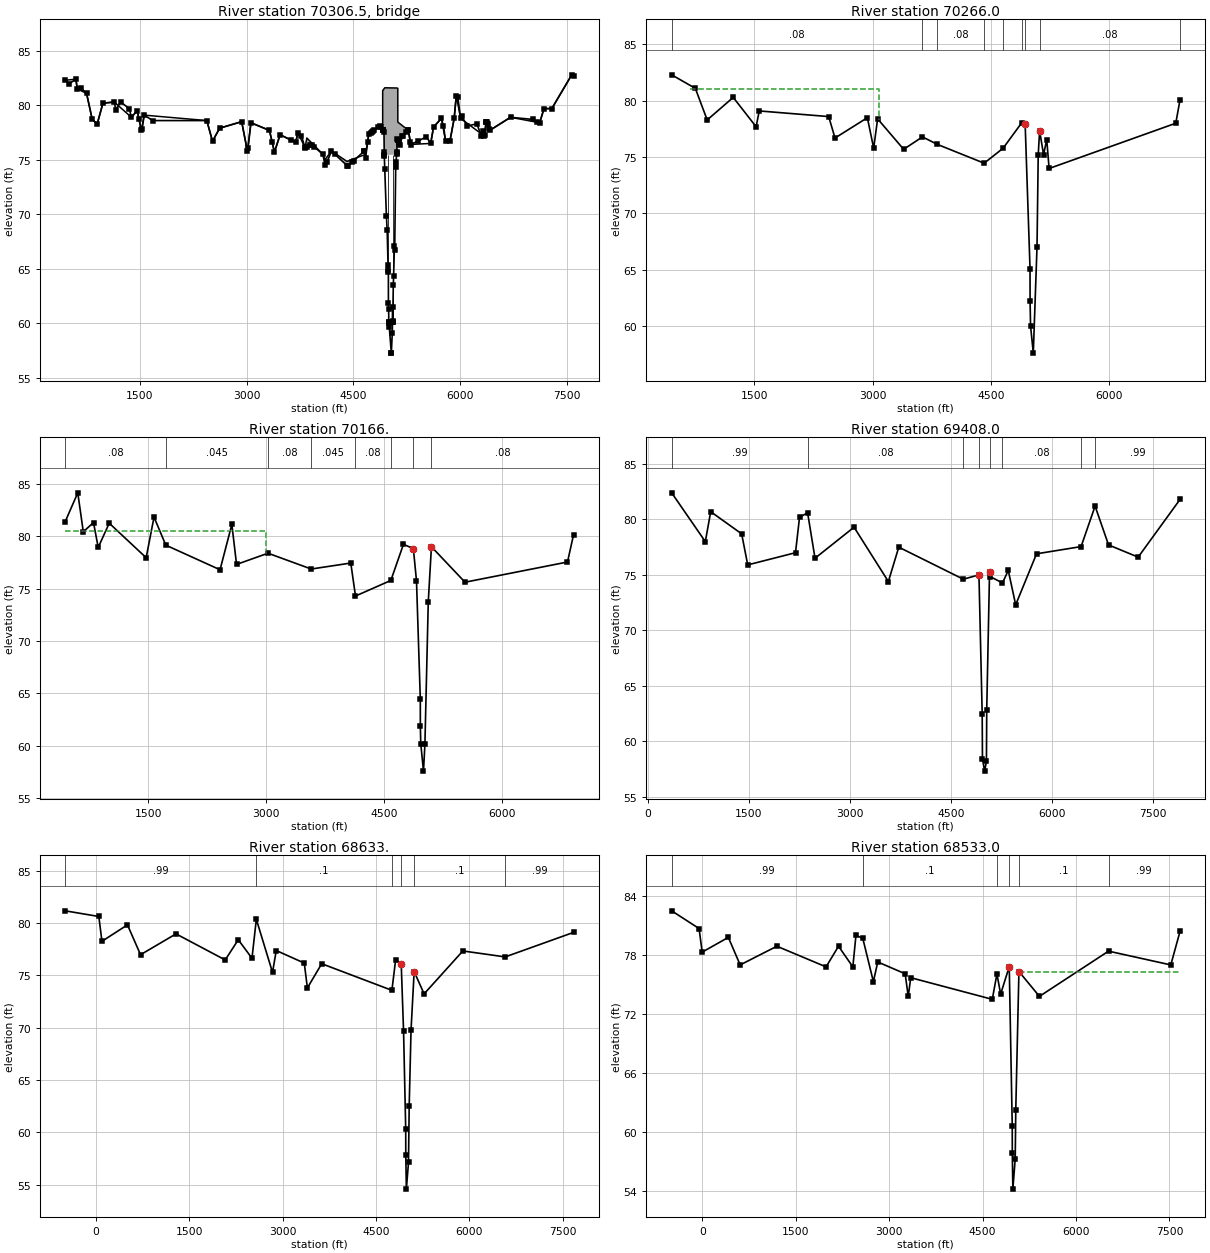
Type RM Length L Ch R = 3 ,70306.5 ,,,
BEGIN DESCRIPTION:
ALABONSON
Structure ID: E100-00-00-41
END DESCRIPTION:
Bridge Culvert--1,0,-1,-1, 0
Deck Dist Width WeirC Skew NumUp NumDn MinLoCord MaxHiCord MaxSubmerge Is_Ogee
10,61,2.6,0, 60, 60, , , 0.95, 0, ,,,
   451.8   601.8   621.8   751.8   831.8   901.8   981.8  1141.8  1381.8  1461.8
  1521.8  1561.8  2441.8  2521.8  2621.8  2931.8  3011.8  3061.8  3321.8  3391.8
  3471.8  3691.8  3721.8  3821.8  3847.8  4073.1  4103.1  4193.1  4411.8  4673.1
  4717.9    4913 4913.29  4913.4  4931.4  4934.1  4942.5  5113.2  5114.7    5126
 5126.11  5273.9    5308    5588    5628    5738    5798    5858    5918    5948
    6008    6338    6368    6418  6710.1  7120.1  7180.1  7290.1  7570.1  7595.5
    82.3    82.4    81.5    81.1    78.7    78.3    80.2    80.3    78.9    79.5
    77.7    79.1    78.6    76.7    77.9    78.5    75.8    78.4    77.7    75.7
    77.3    76.6    77.5    76.1      77   75.51   75.01   75.81   74.85    75.5
   77.37   78.24   78.25   81.35   81.51   81.53   81.61   81.59   81.59   81.56
   78.46   77.71   76.41    76.5      78    78.8    76.7    76.7    78.8    80.9
    78.8    77.2    78.5    77.7    78.9    78.4    79.7    79.7    82.8    82.7
    82.3    82.4    81.5    81.1    78.7    78.3    80.2    80.3    78.9    79.5
    77.7    79.1    78.6    76.7    77.9    78.5    75.8    78.4    77.7    75.7
    77.3    76.6    77.5    76.1   76.19    75.5    74.5    75.8   74.47    75.2
   77.36   77.78   77.78   77.77   77.59   75.72   75.41    75.5   76.95   76.81
   76.81    77.7    76.4    76.5      78    78.8    76.7    76.7    78.8    80.9
    78.8    77.2    78.5    77.7    78.9    78.4    79.7    79.7    82.8    82.7
   451.8   601.8   621.8   751.8   831.8   901.8   981.8  1141.8  1381.8  1461.8
  1521.8  1561.8  2441.8  2521.8  2621.8  2931.8  3011.8  3061.8  3321.8  3391.8
  3471.8  3691.8  3721.8  3821.8  3847.8  4073.1  4103.1  4193.1  4411.8  4673.1
  4717.9    4913 4913.29  4913.4  4931.4  4934.1  4942.5  5113.2  5114.7    5126
 5126.11  5273.9    5308    5588    5628    5738    5798    5858    5918    5948
    6008    6338    6368    6418  6710.1  7120.1  7180.1  7290.1  7570.1  7595.5
    82.3    82.4    81.5    81.1    78.7    78.3    80.2    80.3    78.9    79.5
    77.7    79.1    78.6    76.7    77.9    78.5    75.8    78.4    77.7    75.7
    77.3    76.6    77.5    76.1      77   75.51   75.01   75.81   74.85    75.5
   77.37   78.24   78.25   81.35   81.51   81.53   81.61   81.59   81.59   81.56
   78.46   77.71   76.41    76.5      78    78.8    76.7    76.7    78.8    80.9
    78.8    77.2    78.5    77.7    78.9    78.4    79.7    79.7    82.8    82.7
    82.3    82.4    81.5    81.1    78.7    78.3    80.2    80.3    78.9    79.5
    77.7    79.1    78.6    76.7    77.9    78.5    75.8    78.4    77.7    75.7
    77.3    76.6    77.5    76.1   76.19    75.5    74.5    75.8   74.47    75.2
   77.36   77.78   77.78   77.77   77.59   75.72   75.41    75.5   76.95   76.81
   76.81    77.7    76.4    76.5      78    78.8    76.7    76.7    78.8    80.9
    78.8    77.2    78.5    77.7    78.9    78.4    79.7    79.7    82.8    82.7
Pier Skew, UpSta & Num, DnSta & Num=  ,4994, 2 ,4994, 2 , 0 , 0 , 0 ,,
     1.5     1.5
   60.71   76.52
     1.5     1.5
   61.08   76.89
Pier Skew, UpSta & Num, DnSta & Num=  ,5054.4, 2 ,5054.4, 2 , 0 , 0 , 0 ,,
     1.5     1.5
   59.48   76.55
     1.5     1.5
   59.85   76.92
Abutment Skew #Up #Dn= , 2 , 2
  4935.7  5000.8
   75.39    60.1
  4935.7  5000.8
   75.76   60.47
Abutment Skew #Up #Dn= , 2 , 2
    5053 5113.49
   60.07   75.59
    5053 5113.49
   60.44   75.96
BR Coef= 1 , 1 , 0 ,1.25, 0 ,,,0.8,-1,2,0,
WSPro=,,,, 1 ,,,, 0 ,,,, 0 ,,,,-1 ,-1 ,-1 , 0 , 0 , 0 , 0 , 0
BR U #Sta/Elev= 146
   451.8    82.3   511.8      82   601.8    82.4   621.8    81.5   671.8    81.6
   751.8    81.1   831.8    78.7   901.8    78.3   981.8    80.2  1141.8    80.3
  1161.8    79.6  1231.8    80.3  1351.8    79.7  1381.8    78.9  1461.8    79.5
  1491.8    78.7  1521.8    77.7  1531.8    77.8  1561.8    79.1  1681.8    78.6
  2441.8    78.6  2521.8    76.7  2621.8    77.9  2931.8    78.5  3011.8    75.8
  3021.8    76.1  3061.8    78.4  3321.8    77.7  3361.8    76.6  3391.8    75.7
  3471.8    77.3  3629.8    76.8  3691.8    76.6  3721.8    77.5  3771.8    77.2
  3820.6   76.13  3821.8    76.1  3847.8   76.19  3897.8   76.35  3913.1    76.4
  3947.8    76.2  4073.1    75.5  4103.1    74.5  4133.1    74.8  4193.1    75.8
  4237.8   75.53  4411.8   74.47  4423.1    74.4  4487.8   74.79  4507.8   74.92
  4651.5   75.79  4653.1    75.8  4673.1    75.2  4703.1    76.6  4717.9   77.36
  4747.8    77.5  4767.8   77.59  4777.8   77.64  4797.8   77.73    4851   77.97
  4880.6   78.11    4887   78.04    4913   77.78 4913.29   77.78  4913.4   77.77
 4913.51   77.77  4931.4   77.59  4934.1   75.72 4935.81    75.4  4935.9   75.39
  4942.5   74.16  4965.8   69.83  4976.3   68.57    4989   65.31  4990.3   64.92
  4993.4   64.72    4994   61.84  4997.2    61.3  4999.1   60.09  5000.1   59.66
  5000.7   60.04  5000.8    60.1  5034.2    57.3  5034.8   57.25  5048.3   59.09
  5051.1   60.13  5052.9   60.07    5053   60.07  5053.6   61.51  5054.4   60.18
  5062.7   63.51  5067.2   64.36  5078.3   67.07    5082   66.69  5096.8   74.34
  5097.1    74.8  5113.2    75.5 5113.29   75.59  5113.4   75.69  5114.7   76.95
  5122.7   76.85 5125.89   76.81    5126   76.81 5126.11   76.81  5144.5   76.58
  5159.2    76.4  5188.2   77.16  5197.9   77.22  5247.4   77.53  5273.1   77.69
  5273.9    77.7  5303.1   76.59    5308    76.4  5406.1   76.71    5528    77.1
    5588    76.5    5628      78    5738    78.8    5768    78.1    5798    76.7
    5858    76.7    5918    78.8    5948    80.9    5968    80.8    6008    78.8
    6028      79    6098    78.1    6238    78.3    6298    77.2    6328    77.6
    6338    77.2    6348    77.3    6368    78.5  6372.3   78.47  6374.2   78.46
    6398    78.3    6408    77.8    6418    77.7  6710.1    78.9  7030.1    78.7
  7087.2   78.51  7120.1    78.4  7180.1    79.7  7290.1    79.7  7570.1    82.8
  7595.5    82.7
BR U #Mann= 13
   451.8     .99   451.8     .08  3629.8    .045  3820.6     .08  4411.8    .045
  4651.5     .08    4887     .04  4931.4     .04  5114.7     .08  6372.3     .12
  6374.2     .08  7087.2     .05  7595.5     .99
BR U Banks=4931.4,5114.7
BR D #Sta/Elev= 146
   451.8    82.3   511.8      82   601.8    82.4   621.8    81.5   671.8    81.6
   751.8    81.1   831.8    78.7   901.8    78.3   981.8    80.2  1141.8    80.3
  1161.8    79.6  1231.8    80.3  1351.8    79.7  1381.8    78.9  1461.8    79.5
  1491.8    78.7  1521.8    77.7  1531.8    77.8  1561.8    79.1  1681.8    78.6
  2441.8    78.6  2521.8    76.7  2621.8    77.9  2931.8    78.5  3011.8    75.8
  3021.8    76.1  3061.8    78.4  3321.8    77.7  3361.8    76.6  3391.8    75.7
  3471.8    77.3  3629.8    76.8  3691.8    76.6  3721.8    77.5  3771.8    77.2
  3820.6   76.13  3821.8    76.1  3847.8   76.19  3897.8   76.35  3913.1    76.4
  3947.8    76.2  4073.1    75.5  4103.1    74.5  4133.1    74.8  4193.1    75.8
  4237.8   75.53  4411.8   74.47  4423.1    74.4  4487.8   74.79  4507.8   74.92
  4651.5   75.79  4653.1    75.8  4673.1    75.2  4703.1    76.6  4717.9   77.36
  4747.8    77.5  4767.8   77.59  4777.8   77.64  4797.8   77.73    4851   77.97
  4880.6   78.11    4887   78.04    4913   77.78 4913.29   77.78  4913.4   77.77
 4913.51   77.77  4931.4   77.96  4934.1   76.09 4935.81   75.77  4935.9   75.76
  4942.5   74.53  4965.8    70.2  4976.3   68.94    4989   65.68  4990.3   65.29
  4993.4   65.09    4994   62.21  4997.2   61.67  4999.1   60.46  5000.1   60.03
  5000.7   60.41  5000.8   60.47  5034.2   57.67  5034.8   57.62  5048.3   59.46
  5051.1    60.5  5052.9   60.44    5053   60.44  5053.6   61.88  5054.4   60.55
  5062.7   63.88  5067.2   64.73  5078.3   67.44    5082   67.06  5096.8   74.71
  5097.1   75.17  5113.2   75.87 5113.29   75.96  5113.4   76.06  5114.7   77.32
  5122.7   76.85 5125.89   76.81    5126   76.81 5126.11   76.81  5144.5   76.58
  5159.2    76.4  5188.2   77.16  5197.9   77.22  5247.4   77.53  5273.1   77.69
  5273.9    77.7  5303.1   76.59    5308    76.4  5406.1   76.71    5528    77.1
    5588    76.5    5628      78    5738    78.8    5768    78.1    5798    76.7
    5858    76.7    5918    78.8    5948    80.9    5968    80.8    6008    78.8
    6028      79    6098    78.1    6238    78.3    6298    77.2    6328    77.6
    6338    77.2    6348    77.3    6368    78.5  6372.3   78.47  6374.2   78.46
    6398    78.3    6408    77.8    6418    77.7  6710.1    78.9  7030.1    78.7
  7087.2   78.51  7120.1    78.4  7180.1    79.7  7290.1    79.7  7570.1    82.8
  7595.5    82.7
BR D #Mann= 11
   451.8     .08  3629.8    .045  3820.6     .08  4411.8    .045  4651.5     .08
    4887     .04  4931.4     .04  5114.7     .08  6372.3     .12  6374.2     .08
  7087.2     .05
BR D Banks=4931.4,5114.7
BC Design=,, 0 ,, 0 ,,,,,,
BC HTab HWMax=82.78
BC Use User HTab Curves=0
BC User HTab FreeFlow(D)= 0

Type RM Length L Ch R = 1 ,70266.0 ,80.3,100,80.4
BEGIN DESCRIPTION:
Downstream Section of Bridge/Culvert/Weir
END DESCRIPTION:
XS GIS Cut Line= 6
      3084251.08      13885250.3      3084413.56     13881780.92
      3083835.76     13881109.26      3083850.81     13880602.08
       3083901.3     13879555.43      3083592.78     13879120.03
#Sta/Elev= 30
   451.8   82.28   751.8   81.08   901.8   78.28  1231.8   80.28  1521.8   77.68
  1561.8   79.08  2441.8   78.58  2521.8   76.68  2931.8   78.48  3011.8   75.78
  3061.8   78.38  3391.8   75.68  3629.8   76.78  3820.6   76.11  4411.8   74.45
  4651.5   75.77    4887   78.02  4931.4   77.96  4993.4   65.09    4994   62.21
  5000.1   60.03  5034.8   57.62    5082   67.06  5097.1   75.17  5114.7   77.32
  5165.1   75.21  5205.1   76.54  5235.1   73.98  6840.4   77.99    6894   80.05
#Mann= 9 ,-1 , 0
   451.8     .08       0  3629.8    .045       0  3820.6     .08       0
  4411.8    .045       0  4651.5     .08       0    4887     .04       0
  4931.4     .04       0  5114.7     .08       0    6894     .12       0
#XS Ineff= 3 ,-1
  682.06 3076.38   80.98 3076.38  4931.4    76.4  5114.7  7595.5    76.4
Permanent Ineff=
       F       F       F
Bank Sta=4931.4,5114.7
XS Rating Curve= 0 ,0
Exp/Cntr=0.5,0.3

Type RM Length L Ch R = 1 ,70166.  ,573.5,758,435.6
BEGIN DESCRIPTION:
Alabonson - D/S - XS 1
END DESCRIPTION:
XS GIS Cut Line= 6
      3084350.13      13885244.6       3084512.6     13881775.26
      3083934.81      13881103.6      3083949.86     13880596.42
       3083944.7     13879572.79      3083605.33     13879106.22
#Sta/Elev= 30
   444.8   81.42   604.8   84.17   674.8   80.45   804.8   81.33   864.8   78.95
  1004.8   81.27  1474.8   77.97  1574.8   81.85  1724.8   79.17  2414.8   76.82
  2564.8   81.15  2624.8   77.33  3024.8    78.4  3574.8   76.89    4078   77.46
    4138   74.31    4588    75.8    4748   79.25    4874   78.84    4914   75.77
 4962.57   64.48 4963.16   61.88 4968.15   60.21  5003.1   57.58 5021.11   60.14
    5064   73.78    5104   79.02  5531.4   75.63  6835.1   77.56    6912   80.16
#Mann= 8 ,-1 , 0
   444.8     .08       0  1724.8    .045       0  3024.8     .08       0
  3574.8    .045       0    4138     .08       0    4588    .045       0
    4874     .04       0    5104     .08       0
#XS Ineff= 2 , 0
       0    3000    80.5               0
Permanent Ineff=
       F       F
Bank Sta=4874,5104
XS Rating Curve= 0 ,0
Exp/Cntr=0.3,0.1

Type RM Length L Ch R = 1 ,69408.0 ,776,775,417.9
BEGIN DESCRIPTION:
Cross Section E100-00-00-X48
Structure evident from aerial photography (maybe sheet pile structure) approximately 300 ft. downstream of this cross section.  However, there was no data available to model the structure accurately.  The structure would only effect low flows and have virtually no effect on the 100 and 500 year flows according to its placement and height in the channel.
END DESCRIPTION:
XS GIS Cut Line= 6
      3084549.09     13885394.54      3084861.32     13882114.76
      3084894.53     13881317.93      3084758.95     13881007.22
      3084607.47     13880614.73      3083480.14     13878159.46
#Sta/Elev= 30
   352.2    82.4   852.2      78   932.2    80.7  1392.2    78.7  1482.2    75.9
  2192.2      77  2252.2    80.2  2372.2    80.6  2482.2    76.5  3062.2    79.3
  3572.2    74.4  3726.8    77.5    4686   74.61  4918.2      75  4966.3   62.45
  4970.3   58.39  5003.1    57.3  5029.5   58.22  5033.9   62.85  5075.6   75.24
  5083.9   74.85  5267.7   74.27    5354    75.4    5464    72.3    5774    76.9
  6435.9   77.55    6644    81.2    6844    77.7    7284    76.6  7905.7    81.8
#Mann= 8 ,-1 , 0
   352.2     .99       0  2372.2     .08       0    4686    .045       0
  4918.2     .04       0  5083.9    .045       0  5267.7     .08       0
  6435.9    .045       0    6644     .99       0
Bank Sta=4918.2,5075.6
XS Rating Curve= 0 ,0
Exp/Cntr=0.3,0.1

Type RM Length L Ch R = 1 ,68633.  ,20,100,101
BEGIN DESCRIPTION:
Golf Cart Bridge 40a - U/S - XS 4
END DESCRIPTION:
XS GIS Cut Line= 5
      3084705.72     13885552.46      3085419.62     13880374.04
      3085233.52     13880307.83       3084829.5     13880185.23
      3084019.35     13878013.58
#Sta/Elev= 30
  -492.3   81.16    47.7   80.62    97.7   78.25   507.7   79.82   717.7   76.97
  1287.7   78.96  2077.7   76.47  2287.7    78.4  2507.7   76.63  2577.7   80.35
  2837.7   75.28  2897.7   77.37  3347.7   76.17  3397.7    73.8  3627.7   76.11
  4755.1   73.57  4815.1   76.47  4905.1   76.09  4942.6   69.65    4977   60.35
 4978.16   57.85 4987.42   54.59 5021.89   57.15 5032.85    62.5  5062.6   69.78
  5112.6   75.36  5272.6   73.23  5894.8   77.33  6574.8   76.76  7672.7    79.1
#Mann= 6 ,-1 , 0
  -492.3     .99       0  2577.7      .1       0  4755.1    .045       0
  4905.1     .04       0  5112.6      .1       0  6574.8     .99       0
Bank Sta=4905.1,5112.6
XS Rating Curve= 0 ,0
Exp/Cntr=0.5,0.3

Type RM Length L Ch R = 1 ,68533.0 ,49.7,30,29
BEGIN DESCRIPTION:
Upstream Section of Bridge/Culvert/Weir
END DESCRIPTION:
XS GIS Cut Line= 5
      3084731.19     13885456.25      3085445.09     13880277.82
      3085258.99     13880211.62      3084854.97     13880089.01
      3084044.82     13877917.36
#Sta/Elev= 30
  -494.9   82.54   -54.9   80.74    -4.9   78.34   415.1   79.84   605.1   77.04
  1195.1   78.94  1985.1   76.84  2185.1   78.94  2415.1   76.84  2465.1   80.04
  2575.1   79.74  2745.1   75.34  2815.1   77.34  3255.1   76.14  3305.1   73.84
  3345.1   75.74  4655.1   73.54  4729.5   76.12  4789.4   74.07  4927.4   76.87
  4975.5   60.68  4976.6   57.87  4985.4   54.24  5023.4   57.34  5032.2    62.3
  5082.9   76.37  5412.2   73.84  6522.2   78.44  7522.2   77.04  7670.1   80.44
#Mann= 6 ,-1 , 0
  -494.9     .99       0  2575.1      .1       0  4729.5    .045       0
  4927.4     .04       0  5082.9      .1       0  6522.2     .99       0
#XS Ineff= 2 ,-1
 2165.19 4926.96   76.84 5082.56  7670.1   76.37
Permanent Ineff=
       F       F
Bank Sta=4927.4,5082.9
XS Rating Curve= 0 ,0
Exp/Cntr=0.5,0.3

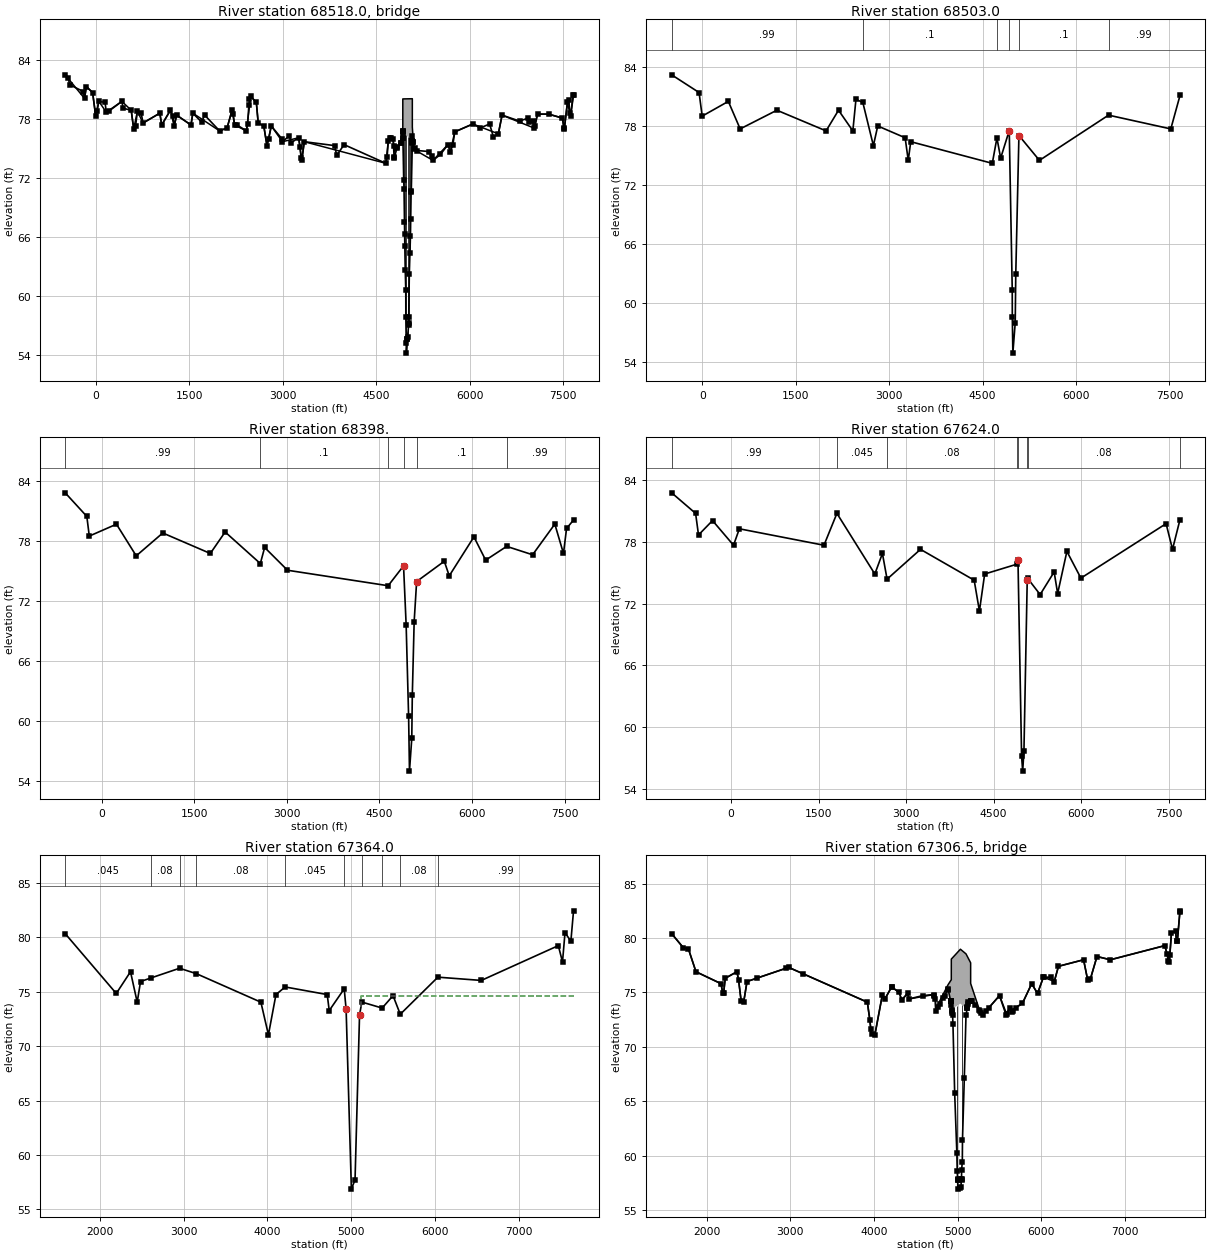
Type RM Length L Ch R = 3 ,68518.0 ,,,
BEGIN DESCRIPTION:
1000FT US VICTORY
Structure ID: E100-00-00-40a
END DESCRIPTION:
Bridge Culvert--1,0,-1,-1, 0
Deck Dist Width WeirC Skew NumUp NumDn MinLoCord MaxHiCord MaxSubmerge Is_Ogee
10,10,2.6,0, 60, 60, , , 0.95, 0, ,,,
  -494.9  -184.9  -154.9   -54.9    -4.9    45.1   165.1   415.1   565.1   605.1
   665.1   755.1  1025.1  1055.1  1195.1  1255.1  1295.1  1525.1  1555.1  1985.1
  2105.1  2185.1  2225.1  2415.1  2485.1  2575.1  2605.1  2695.1  2745.1  2815.1
  2995.1  3255.1  3305.1  3345.1  4655.1  4695.1  4729.5  4772.5  4789.4  4895.1
 4927.59  4927.7  5080.9    5081  5105.7  5412.2  5652.2  5692.2  5762.2  6052.2
  6462.2  6522.2  7032.2  7092.2  7272.2  7492.2  7522.2  7572.2  7622.2  7670.1
    82.5    80.1    81.3    80.7    78.3    79.8    78.7    79.8    78.9      77
    78.8    77.6    78.6    77.4    78.9    77.3    78.4    77.4    78.6    76.8
    77.1    78.9    77.4    76.8    80.3    79.7    77.6    77.3    75.3    77.3
    75.7    76.1    73.8    75.7    73.5    75.8    76.3   76.01   74.67   75.77
   77.15   80.05   80.07   77.17   74.92    73.8    75.4    74.7    76.7    77.5
    76.5    78.4    77.1    78.5    78.5    78.1      77    79.7    78.3    80.4
    82.5    80.1    81.3    80.7    78.3    79.8    78.7    79.8    78.9      77
    78.8    77.6    78.6    77.4    78.9    77.3    78.4    77.4    78.6    76.8
    77.1    78.9    77.4    76.8    80.3    79.7    77.6    77.3    75.3    77.3
    75.7    76.1    73.8    75.7    73.5    75.8   76.08      76   74.03   75.55
   76.77   76.73   75.73   75.76   74.92    73.8    75.4    74.7    76.7    77.5
    76.5    78.4    77.1    78.5    78.5    78.1      77    79.7    78.3    80.4
  -494.9  -184.9  -154.9   -54.9    -4.9    45.1   145.1   165.1   415.1   565.1
   605.1   665.1   755.1  1025.1  1055.1  1195.1  1255.1  1295.1  1525.1  1555.1
  1985.1  2105.1  2185.1  2225.1  2415.1  2485.1  2575.1  2605.1  2695.1  2745.1
  2815.1  2995.1  3255.1  3305.1  3345.1  4655.1  4695.1  4772.5  4789.4  4896.8
 4927.59  4927.7  5080.9    5081  5105.7  5412.2  5652.2  5692.2  5762.2  6052.2
  6462.2  6522.2  7032.2  7092.2  7272.2  7492.2  7522.2  7572.2  7622.2  7670.1
   83.16   80.76   81.96   81.36   78.96   80.46   80.36   79.36   80.46   79.56
   77.66   79.46   78.26   79.26   78.06   79.56   77.96   79.06   78.06   79.26
   77.46   77.76   79.56   78.06   77.46   80.96   80.36   78.26   77.96   75.96
   77.96   76.36   76.76   74.46   76.36   74.16   76.46   76.66   74.69   76.22
   77.43   80.05   80.07   77.17   75.58   74.46   76.06   75.36   77.36   78.16
   77.16   79.06   77.76   79.16   79.16   78.76   77.66   80.36   78.96   81.06
   83.16   80.76   81.96   81.36   78.96   80.46   80.36   79.36   80.46   79.56
   77.66   79.46   78.26   79.26   78.06   79.56   77.96   79.06   78.06   79.26
   77.46   77.76   79.56   78.06   77.46   80.96   80.36   78.26   77.96   75.96
   77.96   76.36   76.76   74.46   76.36   74.16   76.46   76.66   74.69   76.22
   77.43   77.39   76.39   76.42   75.58   74.46   76.06   75.36   77.36   78.16
   77.16   79.06   77.76   79.16   79.16   78.76   77.66   80.36   78.96   81.06
Pier Skew, UpSta & Num, DnSta & Num=  ,4947.6, 2 ,4947.6, 2 , 0 , 0 , 0 ,,
       1       1
   69.56   76.89
       1       1
   70.22   77.55
Pier Skew, UpSta & Num, DnSta & Num=  ,4966.7, 2 ,4966.7, 2 , 0 , 0 , 0 ,,
       1       1
   61.53   76.89
       1       1
   62.19   77.55
Pier Skew, UpSta & Num, DnSta & Num=  ,4985.4, 2 ,4985.4, 2 , 0 , 0 , 0 ,,
       1       1
   53.24   76.96
       1       1
    53.9   77.62
Pier Skew, UpSta & Num, DnSta & Num=  ,5004.6, 2 ,5004.6, 2 , 0 , 0 , 0 ,,
       1       1
   54.85   77.01
       1       1
   55.51   77.67
Pier Skew, UpSta & Num, DnSta & Num=  ,5023.4, 2 ,5023.4, 2 , 0 , 0 , 0 ,,
       1       1
   56.58   76.98
       1       1
   57.24   77.64
Pier Skew, UpSta & Num, DnSta & Num=  ,5042.3, 2 ,5042.3, 2 , 0 , 0 , 0 ,,
       1       1
   63.25   76.96
       1       1
   63.91   77.62
Pier Skew, UpSta & Num, DnSta & Num=  ,5061.3, 2 ,5061.3, 2 , 0 , 0 , 0 ,,
       1       1
   69.43   76.95
       1       1
   70.09   77.61
BR Coef= 1 , 1 , 0 ,1.25, 0 ,,,0.8,-1,2,0,
WSPro=,,,, 1 ,,,, 0 ,,,, 0 ,,,,-1 ,-1 ,-1 , 0 , 0 , 0 , 0 , 0
BR U #Sta/Elev= 144
  -494.9    82.5  -444.9    82.2  -424.9    81.5  -204.9    80.8  -184.9    80.1
  -154.9    81.3   -54.9    80.7    -4.9    78.3    15.1    78.8    45.1    79.8
   145.1    79.7   165.1    78.7   205.1    78.8   415.1    79.8   435.1    79.1
   565.1    78.9   605.1      77   635.1    77.3   665.1    78.8   725.1    78.6
   755.1    77.6  1025.1    78.6  1055.1    77.4  1195.1    78.9  1235.1    78.3
  1255.1    77.3  1295.1    78.4  1525.1    77.4  1555.1    78.6  1695.1    77.7
  1745.1    78.4  1985.1    76.8  2105.1    77.1  2185.1    78.9  2205.1    78.5
  2225.1    77.4  2265.1    77.4  2415.1    76.8  2435.1    77.5  2455.1    79.4
  2465.1      80  2485.1    80.3  2575.1    79.7  2605.1    77.6  2695.1    77.3
  2745.1    75.3  2775.1      76  2815.1    77.3  2985.1      76  2995.1    75.7
  3105.1    76.3  3135.1    75.6  3255.1    76.1  3275.1    75.2  3295.1      74
  3305.1    73.8  3345.1    75.7  3835.1    75.3  3865.1    74.3  3985.1    75.4
  4655.1    73.5  4675.1    74.1  4695.1    75.8  4729.5   76.08  4732.5    76.1
  4772.5      76  4779.5   75.23    4789   74.18  4789.4   74.03  4835.5   75.11
  4840.5   75.15  4895.1   75.55  4896.8   75.56  4927.4   76.83 4927.59   76.77
  4927.7   76.73 4927.81   76.69 4929.51   76.12  4929.6   76.09  4942.3   71.79
  4947.5   70.88  4953.9   67.52  4957.2   66.35  4960.6   65.14  4966.7   62.64
  4975.5   60.64  4976.6   57.83  4983.4   55.26  4985.4    54.2  5001.3   55.62
  5001.6   55.65  5004.6   55.89  5021.4   57.01  5023.3   57.84  5023.4    57.3
  5032.2   62.26  5042.3   64.35  5050.5   66.13  5054.7   67.88  5061.3   70.64
  5063.8   70.63  5080.5   75.61 5080.69   75.67 5080.79    75.7  5080.9   75.73
    5081   75.76 5081.11    75.8  5082.9   76.33  5089.9   75.72  5091.6   75.63
  5105.7   74.92    5123   75.05    5160    74.8  5352.2    74.7  5402.2    74.2
  5412.2    73.8  5532.2    74.4  5652.2    75.4  5692.2    74.7  5732.2    75.4
  5762.2    76.7  6052.2    77.5  6172.2    77.1  6322.2    77.5  6382.2    76.2
  6462.2    76.5  6522.2    78.4  6802.2    77.8  6942.2    78.1  6962.2    77.7
  7012.2    77.8  7032.2    77.1  7052.2    77.3  7092.2    78.5  7272.2    78.5
  7492.2    78.1  7512.2    77.1  7522.2      77  7572.2    79.7  7592.2    79.9
  7612.2    78.6  7622.2    78.3  7662.2    80.4  7670.1    80.4
BR U #Mann= 6
  -494.9     .99  2575.1      .1  4729.5    .045  4927.4     .04  5082.9      .1
  6522.2     .99
BR U Banks=4927.4,5082.9
BR D #Sta/Elev= 144
  -494.9   83.16  -444.9   82.86  -424.9   82.16  -204.9   81.46  -184.9   80.76
  -154.9   81.96   -54.9   81.36    -4.9   78.96    15.1   79.46    45.1   80.46
   145.1   80.36   165.1   79.36   205.1   79.46   415.1   80.46   435.1   79.76
   565.1   79.56   605.1   77.66   635.1   77.96   665.1   79.46   725.1   79.26
   755.1   78.26  1025.1   79.26  1055.1   78.06  1195.1   79.56  1235.1   78.96
  1255.1   77.96  1295.1   79.06  1525.1   78.06  1555.1   79.26  1695.1   78.36
  1745.1   79.06  1985.1   77.46  2105.1   77.76  2185.1   79.56  2205.1   79.16
  2225.1   78.06  2265.1   78.06  2415.1   77.46  2435.1   78.16  2455.1   80.06
  2465.1   80.66  2485.1   80.96  2575.1   80.36  2605.1   78.26  2695.1   77.96
  2745.1   75.96  2775.1   76.66  2815.1   77.96  2985.1   76.66  2995.1   76.36
  3105.1   76.96  3135.1   76.26  3255.1   76.76  3275.1   75.86  3295.1   74.66
  3305.1   74.46  3345.1   76.36  3835.1   75.96  3865.1   74.96  3985.1   76.06
  4655.1   74.16  4675.1   74.76  4695.1   76.46  4729.5   76.74  4732.5   76.76
  4772.5   76.66  4779.5   75.89    4789   74.84  4789.4   74.69  4835.5   75.77
  4840.5   75.81  4895.1   76.21  4896.8   76.22  4927.4   77.49 4927.59   77.43
  4927.7   77.39 4927.81   77.35 4929.51   76.78  4929.6   76.75  4942.3   72.45
  4947.5   71.54  4953.9   68.18  4957.2   67.01  4960.6    65.8  4966.7    63.3
  4975.5    61.3  4976.6   58.49  4983.4   55.92  4985.4   54.86  5001.3   56.28
  5001.6   56.31  5004.6   56.55  5021.4   57.67  5023.3    58.5  5023.4   57.96
  5032.2   62.92  5042.3   65.01  5050.5   66.79  5054.7   68.54  5061.3    71.3
  5063.8   71.29  5080.5   76.27 5080.69   76.33 5080.79   76.36  5080.9   76.39
    5081   76.42 5081.11   76.46  5082.9   76.99  5089.9   76.38  5091.6   76.29
  5105.7   75.58    5123   75.71    5160   75.46  5352.2   75.36  5402.2   74.86
  5412.2   74.46  5532.2   75.06  5652.2   76.06  5692.2   75.36  5732.2   76.06
  5762.2   77.36  6052.2   78.16  6172.2   77.76  6322.2   78.16  6382.2   76.86
  6462.2   77.16  6522.2   79.06  6802.2   78.46  6942.2   78.76  6962.2   78.36
  7012.2   78.46  7032.2   77.76  7052.2   77.96  7092.2   79.16  7272.2   79.16
  7492.2   78.76  7512.2   77.76  7522.2   77.66  7572.2   80.36  7592.2   80.56
  7612.2   79.26  7622.2   78.96  7662.2   81.06  7670.1   81.06
BR D #Mann= 6
  -494.9     .99  2575.1      .1  4729.5    .045  4927.4     .04  5082.9      .1
  6522.2     .99
BR D Banks=4927.4,5082.9
BC Design=,, 0 ,, 0 ,,,,,,
BC HTab HWMax=82.54
BC Use User HTab Curves=0
BC User HTab FreeFlow(D)= 0

Type RM Length L Ch R = 1 ,68503.0 ,108.2,105,75.3
BEGIN DESCRIPTION:
Downstream Section of Bridge/Culvert/Weir
END DESCRIPTION:
XS GIS Cut Line= 5
      3084760.91     13885460.34      3085478.14     13880257.74
      3085268.38     13880183.11      3084877.88     13880064.61
      3084072.92     13877906.87
#Sta/Elev= 30
  -494.9   83.17   -54.9   81.37    -4.9   78.97   415.1   80.47   605.1   77.67
  1195.1   79.57  1985.1   77.47  2185.1   79.57  2415.1   77.47  2465.1   80.67
  2575.1   80.37  2745.1   75.97  2815.1   77.97  3255.1   76.77  3305.1   74.47
  3345.1   76.37  4655.1   74.17  4729.5   76.75  4789.4    74.7  4927.4    77.5
  4975.5   61.31  4976.6    58.5  4985.4   54.87  5023.4   57.97  5032.2   62.93
  5082.9      77  5412.2   74.47  6522.2   79.07  7522.2   77.67  7670.1   81.07
#Mann= 6 ,-1 , 0
  -494.9     .99       0  2575.1      .1       0  4729.5    .045       0
  4927.4     .04       0  5082.9      .1       0  6522.2     .99       0
#XS Ineff= 2 ,-1
 2165.19 4927.51    75.5 5083.12  7670.1    75.5
Permanent Ineff=
       F       F
Bank Sta=4927.4,5082.9
XS Rating Curve= 0 ,0
Exp/Cntr=0.5,0.3

Type RM Length L Ch R = 1 ,68398.  ,1152,774,636.2
BEGIN DESCRIPTION:
Golf Cart Bridge 40a - D/S - XS 1
END DESCRIPTION:
XS GIS Cut Line= 5
      3084813.82      13885390.4      3085522.94     13880158.85
      3085293.85     13880081.24      3084903.35     13879962.73
      3084098.39     13877804.99
#Sta/Elev= 30
  -588.5   82.83  -238.5   80.47  -198.5    78.5   241.5   79.69   561.5   76.52
   991.5   78.81  1761.5   76.76  2001.5   78.91  2571.5   75.75  2641.5   77.36
  3011.5   75.08  4641.5   73.53  4890.9   75.52  4932.8   69.63  4972.8   60.49
 4986.94   54.97 5024.04   58.24  5032.8   62.59  5062.8   69.94  5102.8   73.95
  5550.8   75.98  5630.8   74.52  6030.8   78.42  6220.8   76.09  6560.8   77.47
  6980.8   76.63  7340.8    79.7  7480.8   76.76  7530.8   79.26  7643.8   80.11
#Mann= 6 ,-1 , 0
  -588.5     .99       0  2571.5      .1       0  4641.5    .045       0
  4890.9     .04       0  5102.8      .1       0  6560.8     .99       0
Bank Sta=4890.9,5102.8
XS Rating Curve= 0 ,0
Exp/Cntr=0.3,0.1

Type RM Length L Ch R = 1 ,67624.0 ,261,260,201.3
BEGIN DESCRIPTION:
Cross Section E100-00-00-X47
END DESCRIPTION:
XS GIS Cut Line= 6
      3084845.41     13885479.12      3085413.41     13882705.01
      3085802.98      13881326.6      3086080.31     13879850.16
      3085233.44     13879308.92      3084172.81      13877686.4
#Sta/Elev= 30
 -1017.2    82.8  -607.2    80.8  -557.2    78.7  -317.2    80.1    42.8    77.7
   142.8    79.3  1592.8    77.7  1814.5    80.8  2464.5    74.9  2594.5    76.9
  2674.4    74.4  3246.9    77.3  4166.9    74.3  4256.9    71.3  4346.9    74.9
  4901.1   75.86  4917.7   76.25  4979.7   57.16  4998.3   55.72  5019.9   57.67
  5076.4   74.35  5084.1   74.47  5297.5    72.9  5537.5    75.1  5597.5      73
    5756    77.1    5996    74.5    7456    79.8    7566    77.3  7694.4    80.2
#Mann= 8 ,-1 , 0
 -1017.2     .99       0  1814.5    .045       0  2674.4     .08       0
  4901.1    .045       0  4917.7     .04       0  5076.4     .04       0
  5084.1     .08       0  7694.4     .99       0
#XS Ineff= 2 ,-1
  2079.3  4917.7   76.25  5076.4  7694.4   74.35
Permanent Ineff=
       F       F
Bank Sta=4917.7,5076.4
XS Rating Curve= 0 ,0
Exp/Cntr=0.5,0.3

Type RM Length L Ch R = 1 ,67364.0 ,119,118,112.7
BEGIN DESCRIPTION:
Upstream Section of Bridge/Culvert/Weir
END DESCRIPTION:
XS GIS Cut Line= 6
      3085461.64     13882677.16      3085845.59     13881333.34
      3086157.54     13879629.56      3085831.76     13879422.89
        3085292.     13879173.89      3084245.74     13877514.39
#Sta/Elev= 30
  1583.9   80.35  2193.9   74.85  2363.9   76.85  2443.9   74.05  2483.9   75.95
  2609.1   76.28  2950.1   77.17  3151.1   76.67  3921.5   74.05  4011.5   71.05
  4101.5   74.75  4211.4   75.45  4713.6   74.75    4738   73.28    4917   75.28
  4939.6   73.39  5002.5   56.86  5046.2   57.72    5100   72.88  5127.6   74.06
  5369.9   73.51  5500.1   74.65  5586.4   72.94  6035.9   76.35  6554.5   76.05
  7474.5   79.25  7524.5   77.75  7554.5   80.45  7624.5   79.65  7656.3   82.45
#Mann= 10 ,-1 , 0
  1583.9    .045       0  2609.1     .08       0  2950.1    .045       0
  3151.1     .08       0  4211.4    .045       0    4917     .04       0
  5127.6     .08       0  5369.9    .045       0  5586.4     .08       0
  6035.9     .99       0
#XS Ineff= 2 , 0
       0    4924    74.6    5117       0    74.6
Permanent Ineff=
       F       F
Bank Sta=4939.6,5100
XS Rating Curve= 0 ,0
Exp/Cntr=0.5,0.3

Type RM Length L Ch R = 3 ,67306.5 ,,,
BEGIN DESCRIPTION:
VICTORY
Structure ID: E100-00-00-40
Bridge has 19 degree skew with the channel.
END DESCRIPTION:
Bridge Culvert--1,0,-1,-1, 0
Deck Dist Width WeirC Skew NumUp NumDn MinLoCord MaxHiCord MaxSubmerge Is_Ogee
10,95,2.6,0, 60, 60, , , 0.95, 0, ,,,
  1583.9  1723.9  1783.9  1873.9  2173.9  2193.9  2203.9  2223.9  2363.9  2383.9
  2413.9  2443.9  2483.9  2981.5  3921.5  3971.5  4011.5  4101.5  4131.5  4211.4
  4301.5  4331.5  4401.5  4421.5  4713.6  4733.6    4738  4885.2    4917 4924.19
  4924.3  5033.1    5100  5155.4 5155.51  5262.8  5301.1  5500.1  5580.1  5630.1
  5650.1  5774.5  5884.5  5954.5  6024.5  6154.5  6204.5  6504.5  6554.5  6584.5
  6664.5  6824.5  7474.5  7524.5  7534.5  7554.5  7604.5  7614.5  7624.5  7656.3
    80.4    79.1      79    76.9    75.8    74.9    74.9    76.3    76.9    76.1
    74.2    74.1      76    77.3    74.1    71.2    71.1    74.8    74.4    75.5
      75    74.3    74.9    74.4    74.8   74.41   73.48    75.7   76.08   76.16
   78.06   78.97   78.54   77.72   75.82   73.34   72.96   74.71   73.11   73.61
   73.35      74    75.8    74.9    76.4      76    77.4      78    76.1    76.2
    78.3      78    79.3    77.8    78.4    80.5    80.6    79.7    79.7    82.5
    80.4    79.1      79    76.9    75.8    74.9    74.9    76.3    76.9    76.1
    74.2    74.1      76    77.3    74.1    71.2    71.1    74.8    74.4    75.5
      75    74.3    74.9    74.4    74.8    74.4   73.33   75.32      70   73.44
   73.44   73.97   73.54   74.17   74.18   73.33   72.95    74.7    72.9    73.6
    73.2      74    75.8    74.9    76.4      76    77.4      78    76.1    76.2
    78.3      78    79.3    77.8    78.4    80.5    80.6    79.7    79.7    82.5
  1583.9  1723.9  1783.9  1873.9  2173.9  2193.9  2203.9  2223.9  2363.9  2383.9
  2413.9  2443.9  2483.9  2981.5  3921.5  3971.5  4011.5  4101.5  4131.5  4211.4
  4301.5  4331.5  4401.5  4421.5  4713.6  4733.6    4738  4885.2    4917 4924.19
  4924.3  5033.1    5100  5155.4 5155.51  5262.8  5301.1  5500.1  5580.1  5630.1
  5650.1  5774.5  5884.5  5954.5  6024.5  6154.5  6204.5  6504.5  6554.5  6584.5
  6664.5  6824.5  7474.5  7524.5  7534.5  7554.5  7604.5  7614.5  7624.5  7656.3
    80.4    79.1      79    76.9    75.8    74.9    74.9    76.3    76.9    76.1
    74.2    74.1      76    77.3    74.1    71.2    71.1    74.8    74.4    75.5
      75    74.3    74.9    74.4    74.8   74.41   73.48    75.7   76.08   76.16
   78.06   78.97   78.54   77.72   75.82   73.34   72.96   74.71   73.11   73.61
   73.35      74    75.8    74.9    76.4      76    77.4      78    76.1    76.2
    78.3      78    79.3    77.8    78.4    80.5    80.6    79.7    79.7    82.5
    80.4    79.1      79    76.9    75.8    74.9    74.9    76.3    76.9    76.1
    74.2    74.1      76    77.3    74.1    71.2    71.1    74.8    74.4    75.5
      75    74.3    74.9    74.4    74.8    74.4   73.33   75.32      70   73.44
   73.44   73.97   73.54   74.17   74.18   73.33   72.95    74.7    72.9    73.6
    73.2      74    75.8    74.9    76.4      76    77.4      78    76.1    76.2
    78.3      78    79.3    77.8    78.4    80.5    80.6    79.7    79.7    82.5
Pier Skew, UpSta & Num, DnSta & Num=  ,4995, 2 ,4995, 2 , 0 , 0 , 0 ,,
     1.5     1.5
   57.47   74.72
     1.5     1.5
   56.56   73.81
Pier Skew, UpSta & Num, DnSta & Num=  ,5055.9, 2 ,5055.9, 2 , 0 , 0 , 0 ,,
     1.5     1.5
   58.36   74.83
     1.5     1.5
   57.45   73.92
BR Coef= 1 , 1 , 0 ,1.25, 0 ,,,0.8,-1,2,0,
WSPro=,,,, 1 ,,,, 0 ,,,, 0 ,,,,-1 ,-1 ,-1 , 0 , 0 , 0 , 0 , 0
BR U #Sta/Elev= 115
  1583.9    80.4  1723.9    79.1  1783.9      79  1873.9    76.9  2173.9    75.8
  2193.9    74.9  2203.9    74.9  2223.9    76.3  2363.9    76.9  2383.9    76.1
  2413.9    74.2  2443.9    74.1  2483.9      76  2609.1   76.33  2950.1   77.22
  2981.5    77.3  3151.1   76.72  3921.5    74.1  3951.5    72.5  3961.5    71.6
  3971.5    71.2  4011.5    71.1  4101.5    74.8  4131.5    74.4  4211.4    75.5
  4211.5    75.5  4301.5      75  4331.5    74.3  4401.5    74.9  4421.5    74.4
  4581.5    74.7  4713.6    74.8    4721   74.65  4733.6    74.4    4738   73.33
    4761   73.62  4785.6   73.94    4831   74.52  4845.2    74.7    4880   75.24
  4885.2   75.32    4917   74.17 4924.19   74.17  4924.3   74.18 4924.41   74.22
    4925   73.87 4932.31   73.42  4932.4   73.33  4935.7   73.13  4939.6   72.95
  4944.1   72.05  4964.5   65.76  4990.7   60.21    4995    58.6  4999.3   57.88
  5000.5   57.78  5000.6   57.77  5002.5   56.91  5033.1   57.05  5040.2   57.08
  5043.6   57.85  5046.2   57.77  5046.3   57.84  5047.4   58.66  5055.9   59.43
  5057.9   61.44  5079.6   67.13    5100   72.93 5115.19   73.58  5115.3   73.58
  5116.3   73.63  5124.4   73.97  5127.6   74.11 5155.29   74.17  5155.4   74.17
 5155.51   74.18  5174.7   74.22    5210   73.87  5254.4   73.42  5262.8   73.33
  5282.8   73.13  5301.1   72.95  5342.8   73.32  5369.9   73.56  5500.1    74.7
  5580.1    72.9  5586.4   72.99  5630.1    73.6  5650.1    73.2  5663.9   73.32
  5694.5    73.6  5774.5      74  5884.5    75.8  5954.5    74.9  6024.5    76.4
  6035.9    76.4  6114.5    76.4  6154.5      76  6204.5    77.4  6504.5      78
  6554.5    76.1  6584.5    76.2  6664.5    78.3  6824.5      78  7474.5    79.3
  7504.5    78.5  7514.5    77.9  7524.5    77.8  7534.5    78.4  7554.5    80.5
  7604.5    80.6  7614.5    79.7  7624.5    79.7  7654.5    82.4  7656.3    82.5
BR U #Mann= 10
  1583.9    .045  2609.1     .08  2950.1    .045  3151.1     .08  4211.4    .045
    4917     .04  5127.6     .08  5369.9    .045  5586.4     .08  6035.9     .99
BR U Banks=4939.6,5100
BR D #Sta/Elev= 115
  1583.9    80.4  1723.9    79.1  1783.9      79  1873.9    76.9  2173.9    75.8
  2193.9    74.9  2203.9    74.9  2223.9    76.3  2363.9    76.9  2383.9    76.1
  2413.9    74.2  2443.9    74.1  2483.9      76  2609.1   76.33  2950.1   77.22
  2981.5    77.3  3151.1   76.72  3921.5    74.1  3951.5    72.5  3961.5    71.6
  3971.5    71.2  4011.5    71.1  4101.5    74.8  4131.5    74.4  4211.4    75.5
  4211.5    75.5  4301.5      75  4331.5    74.3  4401.5    74.9  4421.5    74.4
  4581.5    74.7  4713.6    74.8    4721   74.65  4733.6    74.4    4738   73.33
    4761   73.62  4785.6   73.94    4831   74.52  4845.2    74.7    4880   75.24
  4885.2   75.32    4917   74.17 4924.19   74.17  4924.3   74.18 4924.41   74.22
    4925   73.87 4932.31   73.42  4932.4   73.33  4935.7   73.13  4939.6   72.95
  4944.1   71.14  4964.5   64.85  4990.7    59.3    4995   57.69  4999.3   56.97
  5000.5   56.87  5000.6   56.86  5002.5      56  5033.1   56.14  5040.2   56.17
  5043.6   56.94  5046.2   56.86  5046.3   56.93  5047.4   57.75  5055.9   58.52
  5057.9   60.53  5079.6   66.22    5100   72.93 5115.19   73.58  5115.3   73.58
  5116.3   73.63  5124.4   73.97  5127.6   74.11 5155.29   74.17  5155.4   74.17
 5155.51   74.18  5174.7   74.22    5210   73.87  5254.4   73.42  5262.8   73.33
  5282.8   73.13  5301.1   72.95  5342.8   73.32  5369.9   73.56  5500.1    74.7
  5580.1    72.9  5586.4   72.99  5630.1    73.6  5650.1    73.2  5663.9   73.32
  5694.5    73.6  5774.5      74  5884.5    75.8  5954.5    74.9  6024.5    76.4
  6035.9    76.4  6114.5    76.4  6154.5      76  6204.5    77.4  6504.5      78
  6554.5    76.1  6584.5    76.2  6664.5    78.3  6824.5      78  7474.5    79.3
  7504.5    78.5  7514.5    77.9  7524.5    77.8  7534.5    78.4  7554.5    80.5
  7604.5    80.6  7614.5    79.7  7624.5    79.7  7654.5    82.4  7656.3    82.5
BR D #Mann= 10
  1583.9    .045  2609.1     .08  2950.1    .045  3151.1     .08  4211.4    .045
    4917     .04  5127.6     .08  5369.9    .045  5586.4     .08  6035.9     .99
BR D Banks=4939.6,5100
BC Design=,, 0 ,, 0 ,,,,,,
BC HTab HWMax=82.45
BC Use User HTab Curves=0
BC User HTab FreeFlow(D)= 0