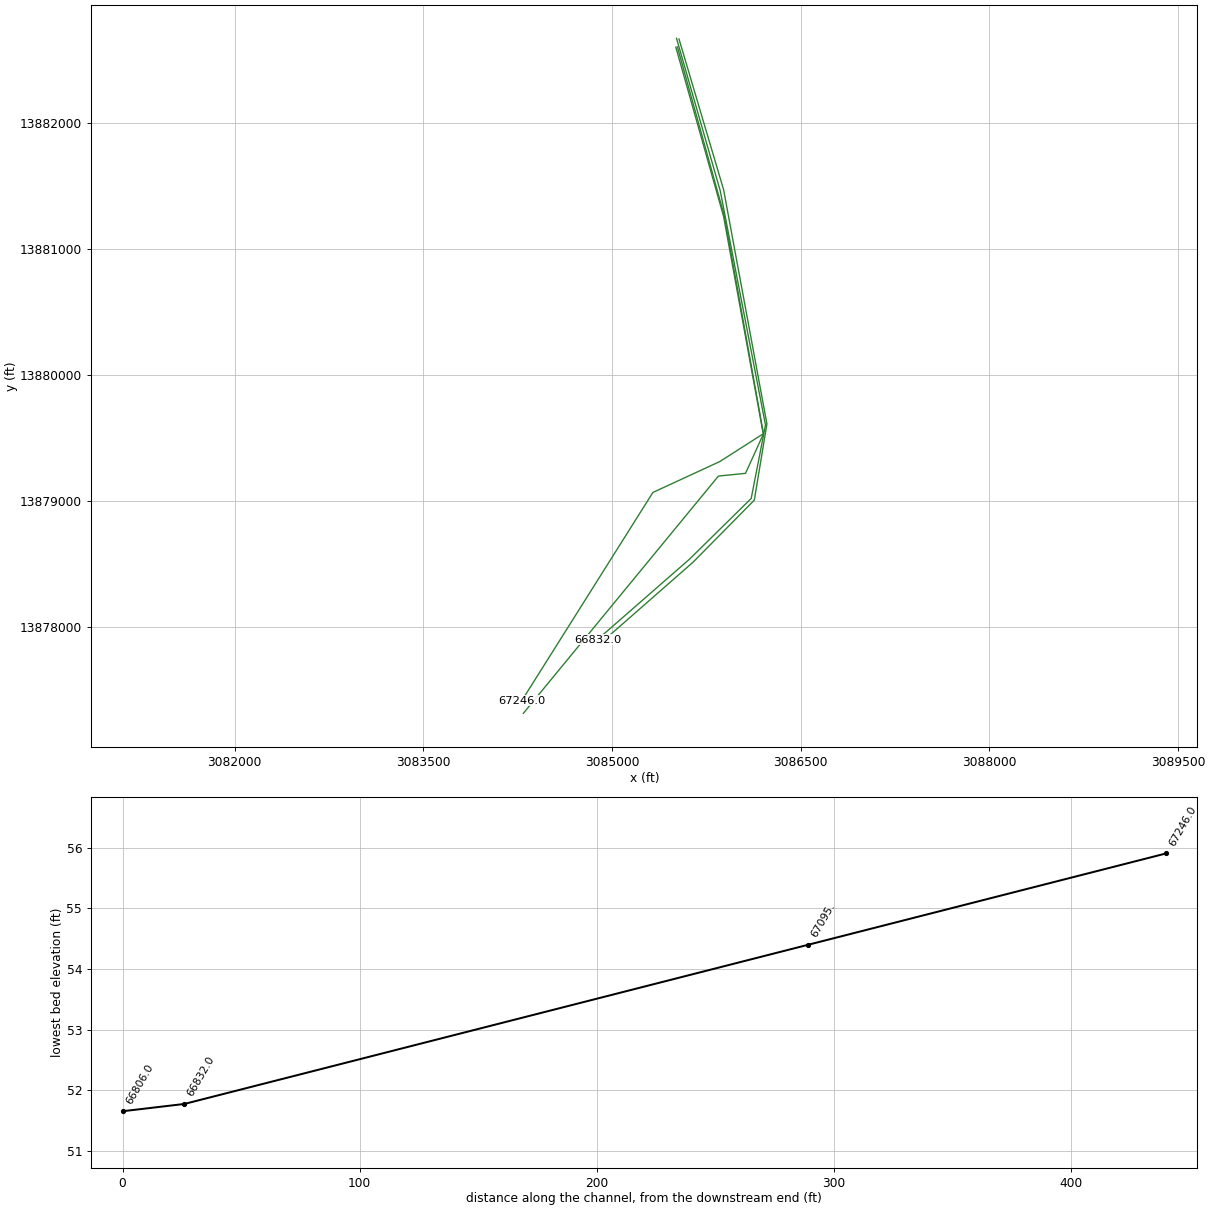
HEC-RAS study E100-00-00.prj: E100-00-00

--- E100-00-00.g02 (geometry) --- (continued)

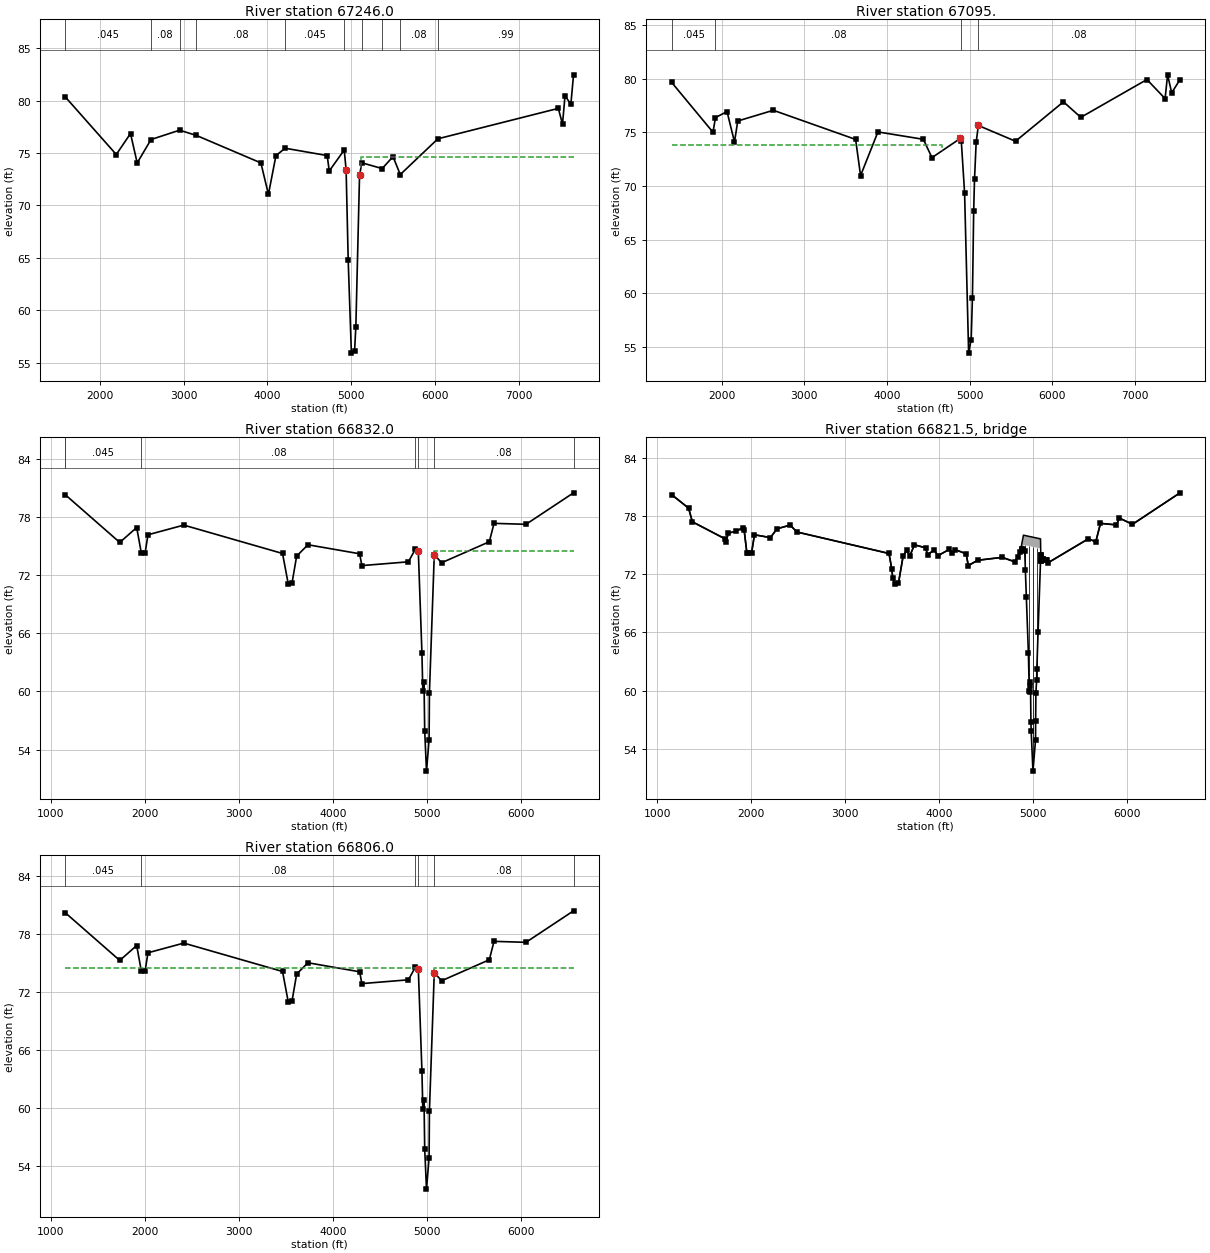
Type RM Length L Ch R = 1 ,67246.0 ,112.3,151,221.9
BEGIN DESCRIPTION:
Downstream Section of Bridge/Culvert/Weir
END DESCRIPTION:
XS GIS Cut Line= 6
      3085507.69       13882600.      3085887.55       13881255.
      3086202.45     13879530.71       3085858.1     13879310.96
      3085325.36     13879065.19      3084283.84     13877413.21
#Sta/Elev= 30
  1583.9   80.35  2193.9   74.85  2363.9   76.85  2443.9   74.05  2609.1   76.28
  2950.1   77.17  3151.1   76.67  3921.5   74.05  4011.5   71.05  4101.5   74.75
  4211.4   75.45  4713.6   74.75    4738   73.28    4917   75.28  4939.6   73.39
  4964.5   64.76  5002.5   55.91  5040.2   56.08  5055.9   58.43    5100   72.88
  5127.6   74.06  5369.9   73.51  5500.1   74.65  5586.4   72.94  6035.9   76.35
  7474.5   79.25  7524.5   77.75  7554.5   80.45  7624.5   79.65  7656.3   82.45
#Mann= 10 ,-1 , 0
  1583.9    .045       0  2609.1     .08       0  2950.1    .045       0
  3151.1     .08       0  4211.4    .045       0    4917     .04       0
  5127.6     .08       0  5369.9    .045       0  5586.4     .08       0
  6035.9     .99       0
#XS Ineff= 2 , 0
       0    4924    74.6    5117       0    74.6
Permanent Ineff=
       F       F
Bank Sta=4939.6,5100
XS Rating Curve= 0 ,0
Exp/Cntr=0.5,0.3

Type RM Length L Ch R = 1 ,67095.  ,104.7,263,263.1
BEGIN DESCRIPTION:
Victory SB - D/S - XS 1
END DESCRIPTION:
XS GIS Cut Line= 6
        3085520.     13882602.09      3085894.11     13881257.18
      3086204.39     13879530.88      3086061.58     13879216.94
      3085846.21     13879195.26      3084295.16     13877311.33
#Sta/Elev= 30
  1394.6   79.67  1894.6   75.02  1924.6   76.39  2064.6   76.95  2154.6   74.11
  2194.6   76.07  2624.6   77.07  3620.6   74.35  3680.6   70.97  3890.6   75.05
  4440.6   74.36  4544.5   72.65  4889.4   74.45  4899.4   74.21  4939.4   69.35
 4988.34    54.4 5019.05   55.67  5034.3   59.57  5049.4   67.71  5059.4   70.61
  5079.4   74.08  5105.9   75.65  5555.9   74.18  6135.9   77.86  6345.9   76.41
  7145.9   79.94  7365.9   78.16  7395.9   80.38  7445.9    78.7  7546.2   79.94
#Mann= 4 ,-1 , 0
  1394.6    .045       0  1924.6     .08       0  4899.4     .04       0
  5105.9     .08       0
#XS Ineff= 2 , 0
       0    4670   73.79               0
Permanent Ineff=
       F       F
Bank Sta=4889.4,5105.9
XS Rating Curve= 0 ,0
Exp/Cntr=0.3,0.1

Type RM Length L Ch R = 1 ,66832.0 ,22.3,26,29.6
BEGIN DESCRIPTION:
Upstream Section of Bridge/Culvert/Weir
END DESCRIPTION:
XS GIS Cut Line= 6
      3085513.09     13882670.27      3085861.04     13881458.44
      3086220.42     13879600.34       3086106.8     13879017.58
       3085615.3     13878534.58      3084884.18     13877896.85
#Sta/Elev= 30
  1155.3    80.3  1735.3   75.37  1915.3   76.91  1964.9   74.26  2005.3   74.32
  2035.3   76.16  2416.1   77.16  3466.1   74.23  3526.1   71.12  3566.1   71.14
  3616.1   73.96  3736.1   75.13  4286.1    74.2  4309.3   72.98 4803.88   73.37
  4877.8   74.66 4909.58   74.49 4948.08   63.97 4957.48      60 4970.28   60.94
 4977.58   55.93 4996.58   51.77 5024.18      55 5027.78   59.86 5079.38   74.12
  5156.7   73.27  5664.6   75.44  5714.6   77.34  6054.6   77.24    6560   80.49
#Mann= 7 , 1 , 0
  1155.3     .99       0  1155.3    .045       0  1964.9     .08       0
  4877.8     .04       0 4909.58     .04       0 5079.38     .08       0
    6560     .99       0
#XS Ineff= 2 , 0
       0  4895.3    74.5 5077.08       0    74.5
Permanent Ineff=
       F       F
Bank Sta=4909.58,5079.38
XS Rating Curve= 0 ,0
Exp/Cntr=0.5,0.3

Type RM Length L Ch R = 3 ,66821.5 ,,,
BEGIN DESCRIPTION:
PL1_E100-00-00-39a
END DESCRIPTION:
Bridge Culvert--1,0,-1,-1, 0
Deck Dist Width WeirC Skew NumUp NumDn MinLoCord MaxHiCord MaxSubmerge Is_Ogee
10,1,2.6,0, 58, 58, , , 0.95, 0, ,,,
  1155.3  1335.3  1375.3  1725.3  1735.3  1755.3  1835.3  1915.3  1925.3  1955.3
  2005.3  2035.3  2205.3  2275.3  2416.1  2486.1  3466.1  3496.1  3506.1  3526.1
  3566.1  3616.1  3656.1  3686.1  3736.1  3856.1  3876.1  3946.1  3986.1  4106.1
  4136.1  4166.1  4286.1  4309.3  4409.3  4669.3 4803.88 4834.48  4863.8 4878.68
 4895.49 4895.58 5077.07 5077.18 5079.38  5082.5 5101.18  5102.5  5132.5 5145.98
  5156.7  5584.6  5664.6  5714.6  5884.6  5914.6  6054.6    6560
   80.21   78.82   77.41   75.64   75.28   76.25   76.41   76.82    76.6   74.16
   74.23   76.07   75.78   76.69   77.07   76.36   74.14   72.51    71.6   71.03
   71.05   73.87    74.5   73.85   75.04   74.72      74   74.51   73.91   74.56
   74.18   74.55   74.11   72.89   73.44   73.74   73.28   73.79    74.4   75.17
   76.03   76.03   75.65   75.65   74.26   73.97    73.7    73.8   73.51   73.47
   73.18   75.65   75.35   77.25   77.09    77.8   77.15    80.4
   80.21   78.82   77.41   75.64   75.28   76.25   76.41   76.82    76.6   74.16
   74.23   76.07   75.78   76.69   77.07   76.36   74.14   72.51    71.6   71.03
   71.05   73.87    74.5   73.85   75.04   74.72      74   74.51   73.91   74.56
   74.18   74.55   74.11   72.89   73.44   73.74   73.28   73.79   74.32   74.59
   74.49   75.03   74.65   73.41   74.03   73.96   73.57   73.57    73.5   73.47
   73.18   75.65   75.35   77.25   77.09    77.8   77.15    80.4
  1155.3  1335.3  1375.3  1725.3  1735.3  1755.3  1835.3  1915.3  1925.3  1955.3
  2005.3  2035.3  2205.3  2275.3  2416.1  2486.1  3466.1  3496.1  3506.1  3526.1
  3566.1  3616.1  3656.1  3686.1  3736.1  3856.1  3876.1  3946.1  3986.1  4106.1
  4136.1  4166.1  4286.1  4309.3  4409.3  4669.3 4803.88 4834.48  4863.8 4878.68
 4895.49 4895.58 5077.07 5077.18 5079.38  5082.5 5101.18  5102.5  5132.5 5145.98
  5156.7  5584.6  5664.6  5714.6  5884.6  5914.6  6054.6    6560
   80.21   78.82   77.41   75.64   75.28   76.25   76.41   76.82    76.6   74.16
   74.23   76.07   75.78   76.69   77.07   76.36   74.14   72.51    71.6   71.03
   71.05   73.87    74.5   73.85   75.04   74.72      74   74.51   73.91   74.56
   74.18   74.55   74.11   72.89   73.44   73.74   73.28   73.79    74.4   75.17
   76.03   76.03   75.65   75.65   74.26   73.97    73.7    73.8   73.51   73.47
   73.18   75.65   75.35   77.25   77.09    77.8   77.15    80.4
   80.21   78.82   77.41   75.64   75.28   76.25   76.41   76.82    76.6   74.16
   74.23   76.07   75.78   76.69   77.07   76.36   74.14   72.51    71.6   71.03
   71.05   73.87    74.5   73.85   75.04   74.72      74   74.51   73.91   74.56
   74.18   74.55   74.11   72.89   73.44   73.74   73.28   73.79   74.32   74.59
   74.49   75.03   74.65   73.41   74.03   73.96   73.57   73.57    73.5   73.47
   73.18   75.65   75.35   77.25   77.09    77.8   77.15    80.4
Pier Skew, UpSta & Num, DnSta & Num=  ,4916.1, 2 ,4916.1, 2 , 0 , 0 , 0 ,,
     1.4     1.4
    71.2   75.99
     1.4     1.4
    71.2   75.99
Pier Skew, UpSta & Num, DnSta & Num=  ,4957.5, 2 ,4957.5, 2 , 0 , 0 , 0 ,,
     1.4     1.4
   58.89    75.9
     1.4     1.4
   58.89    75.9
Pier Skew, UpSta & Num, DnSta & Num=  ,4996.6, 2 ,4996.6, 2 , 0 , 0 , 0 ,,
     1.4     1.4
   50.76   75.82
     1.4     1.4
   50.76   75.82
Pier Skew, UpSta & Num, DnSta & Num=  ,5036.1, 2 ,5036.1, 2 , 0 , 0 , 0 ,,
     1.4     1.4
      60   75.74
     1.4     1.4
      60   75.74
BR Coef= 1 , 1 , 0 ,1.25, 0 ,,,0.8,-1,2,0,
WSPro=,,,, 1 ,,,, 0 ,,,, 0 ,,,,-1 ,-1 ,-1 , 0 , 0 , 0 , 0 , 0
BR U #Sta/Elev= 80
  1155.3   80.21  1335.3   78.82  1375.3   77.41  1725.3   75.64  1735.3   75.28
  1755.3   76.25  1835.3   76.41  1915.3   76.82  1925.3    76.6  1955.3   74.16
  1964.9   74.17  2005.3   74.23  2035.3   76.07  2205.3   75.78  2275.3   76.69
  2416.1   77.07  2486.1   76.36  3466.1   74.14  3496.1   72.51  3506.1    71.6
  3526.1   71.03  3566.1   71.05  3616.1   73.87  3656.1    74.5  3686.1   73.85
  3736.1   75.04  3856.1   74.72  3876.1      74  3946.1   74.51  3986.1   73.91
  4106.1   74.56  4136.1   74.18  4166.1   74.55  4286.1   74.11  4309.3   72.89
  4409.3   73.44  4669.3   73.74 4803.88   73.28 4834.48   73.79  4863.8   74.32
  4877.8   74.57 4878.68   74.59 4895.38   74.49 4895.49   74.49 4895.58   74.49
 4909.58    74.4 4916.08   72.39 4926.28   69.62 4948.08   63.88 4957.48   59.91
 4960.68   59.81 4966.28    60.5 4970.28   60.85 4975.08   56.72 4977.58   55.84
 4996.58   51.68 5024.18   54.91 5024.98   56.87 5027.78   59.77 5036.08   61.11
 5037.88   62.23 5050.88   66.02 5077.07   73.38 5077.18   73.41 5077.28   73.44
 5079.38   74.03  5082.5   73.96 5101.18   73.57  5102.5   73.57  5132.5    73.5
  5135.4   73.49 5145.98   73.47  5156.7   73.18  5584.6   75.65  5664.6   75.35
  5714.6   77.25  5884.6   77.09  5914.6    77.8  6054.6   77.15    6560    80.4
BR U #Mann= 7
  1155.3     .99  1155.3    .045  1964.9     .08  4877.8     .04 4909.58    .045
 5079.38     .08    6560     .99
BR U Banks=4909.58,5079.38
BR D #Sta/Elev= 80
  1155.3   80.21  1335.3   78.82  1375.3   77.41  1725.3   75.64  1735.3   75.28
  1755.3   76.25  1835.3   76.41  1915.3   76.82  1925.3    76.6  1955.3   74.16
  1964.9   74.17  2005.3   74.23  2035.3   76.07  2205.3   75.78  2275.3   76.69
  2416.1   77.07  2486.1   76.36  3466.1   74.14  3496.1   72.51  3506.1    71.6
  3526.1   71.03  3566.1   71.05  3616.1   73.87  3656.1    74.5  3686.1   73.85
  3736.1   75.04  3856.1   74.72  3876.1      74  3946.1   74.51  3986.1   73.91
  4106.1   74.56  4136.1   74.18  4166.1   74.55  4286.1   74.11  4309.3   72.89
  4409.3   73.44  4669.3   73.74 4803.88   73.28 4834.48   73.79  4863.8   74.32
  4877.8   74.57 4878.68   74.59 4895.38   74.49 4895.49   74.49 4895.58   74.49
 4909.58    74.4 4916.08   72.39 4926.28   69.62 4948.08   63.88 4957.48   59.91
 4960.68   59.81 4966.28    60.5 4970.28   60.85 4975.08   56.72 4977.58   55.84
 4996.58   51.68 5024.18   54.91 5024.98   56.87 5027.78   59.77 5036.08   61.11
 5037.88   62.23 5050.88   66.02 5077.07   73.38 5077.18   73.41 5077.28   73.44
 5079.38   74.03  5082.5   73.96 5101.18   73.57  5102.5   73.57  5132.5    73.5
  5135.4   73.49 5145.98   73.47  5156.7   73.18  5584.6   75.65  5664.6   75.35
  5714.6   77.25  5884.6   77.09  5914.6    77.8  6054.6   77.15    6560    80.4
BR D #Mann= 7
  1155.3     .99  1155.3    .045  1964.9     .08  4877.8     .04 4909.58    .045
 5079.38     .08    6560     .99
BR D Banks=4909.58,5079.38
BC Design=,, 0 ,, 0 ,,,,,,
BC HTab HWMax=80.49
BC Use User HTab Curves=0
BC User HTab FreeFlow(D)= 0

Type RM Length L Ch R = 1 ,66806.0 ,16.2,111,203.1
BEGIN DESCRIPTION:
Downstream Section of Bridge/Culvert/Weir
END DESCRIPTION:
XS GIS Cut Line= 6
      3085532.93     13882664.68      3085887.38      13881468.6
      3086231.65     13879609.32      3086131.55     13879004.06
      3085643.91      13878510.9      3084908.32     13877867.26
#Sta/Elev= 30
  1155.3   80.18  1735.3   75.25  1915.3   76.79  1964.9   74.14  2005.3    74.2
  2035.3   76.04  2416.1   77.04  3466.1   74.11  3526.1      71  3566.1   71.02
  3616.1   73.84  3736.1   75.01  4286.1   74.08  4309.3   72.86 4803.88   73.25
  4877.8   74.54 4909.58   74.37 4948.08   63.85 4957.48   59.88 4970.28   60.82
 4977.58   55.81 4996.58   51.65 5024.18   54.88 5027.78   59.74 5079.38      74
  5156.7   73.15  5664.6   75.32  5714.6   77.22  6054.6   77.12    6560   80.37
#Mann= 6 ,-1 , 0
  1155.3    .045       0  1964.9     .08       0  4877.8     .04       0
 4909.58     .04       0 5079.38     .08       0    6560     .99       0
#XS Ineff= 2 , 0
       0  4895.3    74.5 5077.08       0    74.5
Permanent Ineff=
       F       F
Bank Sta=4909.58,5079.38
XS Rating Curve= 0 ,0
Exp/Cntr=0.5,0.3