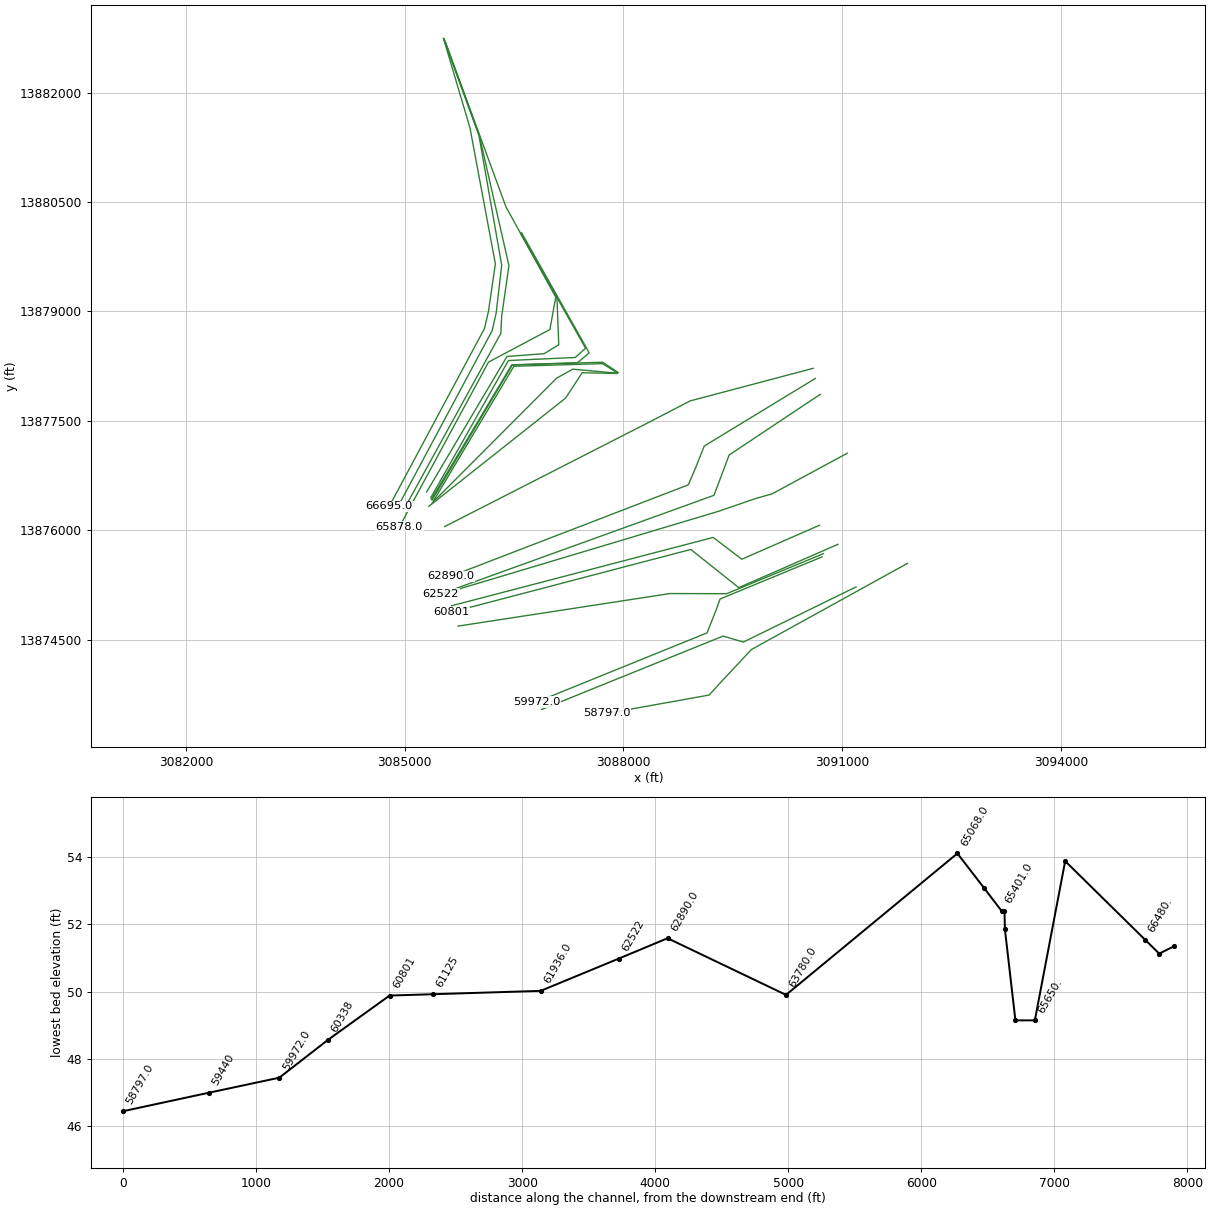
HEC-RAS study E100-00-00.prj: E100-00-00

--- E100-00-00.g02 (geometry) --- (continued)

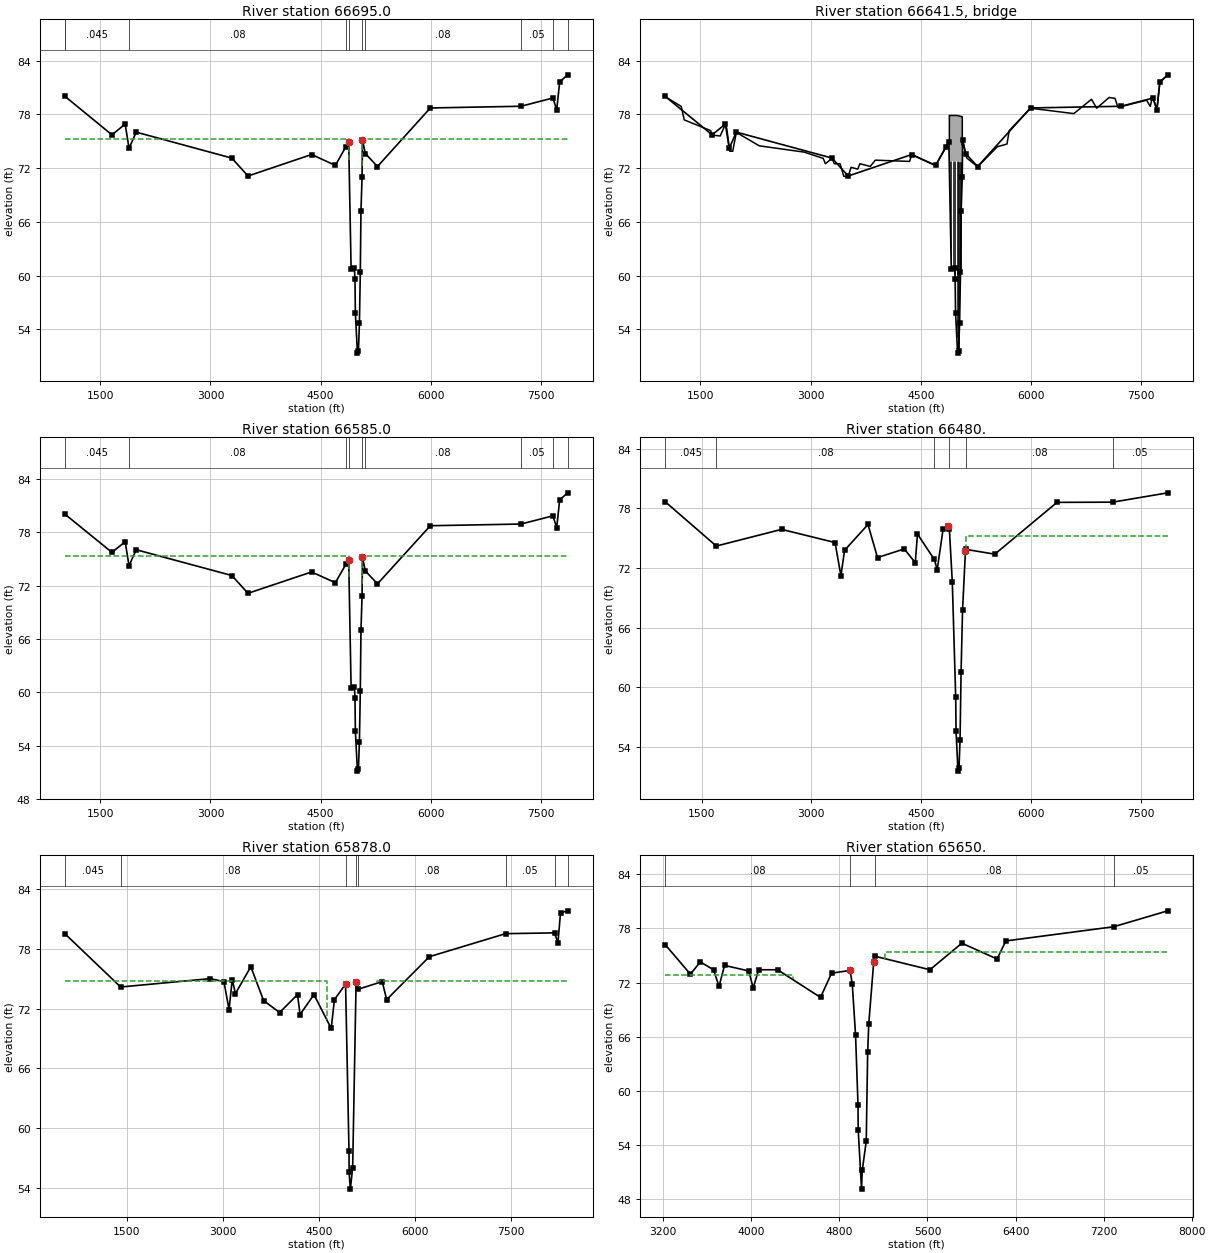
Type RM Length L Ch R = 1 ,66695.0 ,116.3,110,107
BEGIN DESCRIPTION:
Upstream Section of Bridge/Culvert/Weir
END DESCRIPTION:
XS GIS Cut Line= 6
      3085532.93     13882745.14      3085895.94     13881520.04
      3086245.13       13879652.      3086150.17     13879002.02
      3086096.44     13878768.03       3084790.7     13876328.54
#Sta/Elev= 30
  1019.7   80.03  1659.7   75.73  1839.7   76.93  1892.2   74.23  1989.7   76.03
  3291.3   73.13  3511.3   71.13  4376.5   73.53  4700.2   72.32  4842.8   74.39
  4881.3   74.93  4914.4   60.75  4959.7   60.82  4967.1   59.58  4972.3   55.87
  5000.3   51.35  5013.9   51.57  5027.4   54.66  5039.5   60.36  5048.7   67.26
  5063.5   71.06  5068.5   75.17  5108.6   73.64    5273   72.19  5992.6   78.73
  7226.8   78.92    7660   79.84  7712.6   78.53  7752.6   81.63  7859.6   82.43
#Mann= 10 , 1 , 0
  1019.7     .99       0  1019.7    .045       0  1892.2     .08       0
  4842.8     .04       0  4881.3     .02       0  5068.5     .04       0
  5108.6     .08       0  7226.8     .05       0    7660     .12       0
  7859.6     .99       0
#XS Ineff= 2 , 0
       0    4886    75.3    5065       0    75.3
Permanent Ineff=
       F       F
Bank Sta=4881.3,5068.5
XS Rating Curve= 0 ,0
Exp/Cntr=0.5,0.3

Type RM Length L Ch R = 3 ,66641.5 ,,,
BEGIN DESCRIPTION:
ANTOINE
Structure ID: E100-00-00-39
END DESCRIPTION:
Bridge Culvert--1,0,-1,-1, 0
Deck Dist Width WeirC Skew NumUp NumDn MinLoCord MaxHiCord MaxSubmerge Is_Ogee
10,87,2.6,0, 60, 60, , , 0.95, 0, ,,,
  1019.7  1239.7  1279.7  1639.7  1659.7  1769.7  1839.7  1859.7  1899.7  1939.7
  1989.7  2301.3  2911.3  3171.3  3201.3  3291.3  3321.3  3401.3  3451.3  3511.3
  3551.3  3641.3  3671.3  3811.3  3881.3  4346.5  4376.5  4700.2  4881.3 4888.29
  4888.4 4888.71  4888.8  4889.1  4993.4 5063.79 5063.89    5064  5064.1  5064.7
  5067.8  5068.5  5123.9    5273  5540.9  5672.6  5702.6  5992.6  6582.6  6822.6
  6892.6  7062.6  7142.6  7182.6  7572.6  7622.6  7652.6  7712.6  7752.6  7859.6
      80    78.9    77.4    76.2    75.7    75.6    76.9    76.4    73.9    73.9
      76    74.5    73.8    73.1    72.5    73.1    72.5    72.5    71.1    71.1
    72.1    71.9    72.5    72.2    72.9   72.76   73.51   72.29   74.91   74.68
   77.88   77.88   77.88   77.89   77.89   77.75   77.75   77.75   74.55   74.54
   74.58   75.15   73.15   72.16    74.4    74.7    76.2    78.7    78.1    79.7
    78.7    79.9    79.8    78.8    79.6    78.9      80    78.5    81.6    82.4
      80    78.9    77.4    76.2    75.7    75.6    76.9    76.4    73.9    73.9
      76    74.5    73.8    73.1    72.5    73.1    72.5    72.5    71.1    71.1
    72.1    71.9    72.5    72.2    72.9    72.7    73.5   72.29    74.9   71.84
   71.79   71.68   72.78   72.79   72.79   72.65   71.56    71.7   71.84   72.65
   74.57   75.14   73.01   72.16   74.03    74.7    76.2    78.7    78.1    79.7
    78.7    79.9    79.8    78.8    79.6    78.9      80    78.5    81.6    82.4
  1019.7  1239.7  1279.7  1639.7  1659.7  1769.7  1839.7  1859.7  1899.7  1939.7
  1989.7  2301.3  2911.3  3171.3  3201.3  3291.3  3321.3  3401.3  3451.3  3511.3
  3551.3  3641.3  3671.3  3811.3  3881.3  4346.5  4376.5  4700.2  4881.3 4888.29
  4888.4 4888.71  4888.8  4889.1  4993.4 5063.79 5063.89    5064  5064.1  5064.7
  5067.8  5068.5  5123.9    5273  5540.9  5672.6  5702.6  5992.6  6582.6  6822.6
  6892.6  7062.6  7142.6  7182.6  7572.6  7622.6  7652.6  7712.6  7752.6  7859.6
      80    78.9    77.4    76.2    75.7    75.6    76.9    76.4    73.9    73.9
      76    74.5    73.8    73.1    72.5    73.1    72.5    72.5    71.1    71.1
    72.1    71.9    72.5    72.2    72.9   72.76   73.51   72.29   74.91   74.68
   77.88   77.88   77.88   77.89   77.89   77.75   77.75   77.75   74.55   74.54
   74.58   75.15   73.15   72.16    74.4    74.7    76.2    78.7    78.1    79.7
    78.7    79.9    79.8    78.8    79.6    78.9      80    78.5    81.6    82.4
   79.77   78.67   77.17   75.97   75.47   75.37   76.67   76.17   73.67   73.67
   75.77   74.27   73.57   72.87   72.27   72.87   72.27   72.27   70.87   70.87
   71.87   71.67   72.27   71.97   72.67   72.47   73.27   72.06   74.67   71.61
   71.56   71.45   72.55   72.56   72.56   72.42   71.33   71.47   71.61   72.42
   74.34   74.91   72.78   71.93    73.8   74.47   75.97   78.47   77.87   79.47
   78.47   79.67   79.57   78.57   79.37   78.67   79.77   78.27   81.37   82.17
Pier Skew, UpSta & Num, DnSta & Num=  ,4899.4, 2 ,4899.4, 2 , 0 , 0 , 0 ,,
     1.4     1.4
   65.06   73.79
     1.4     1.4
   64.83   73.56
Pier Skew, UpSta & Num, DnSta & Num=  ,4914.4, 2 ,4914.4, 2 , 0 , 0 , 0 ,,
     1.2     1.2
   59.65    73.8
     1.2     1.2
   59.42   73.57
Pier Skew, UpSta & Num, DnSta & Num=  ,4939.2, 2 ,4939.2, 2 , 0 , 0 , 0 ,,
     3.2     3.2
   60.47    73.8
     3.2     3.2
   60.24   73.57
Pier Skew, UpSta & Num, DnSta & Num=  ,4950, 2 ,4950, 2 , 0 , 0 , 0 ,,
     1.4     1.4
   60.29    73.8
     1.4     1.4
   60.06   73.57
Pier Skew, UpSta & Num, DnSta & Num=  ,4963.9, 2 ,4963.9, 2 , 0 , 0 , 0 ,,
     3.2     3.2
   58.83   73.79
     3.2     3.2
    58.6   73.56
Pier Skew, UpSta & Num, DnSta & Num=  ,4988.9, 2 ,4988.9, 2 , 0 , 0 , 0 ,,
     3.2     3.2
   51.34   73.79
     3.2     3.2
   51.11   73.56
Pier Skew, UpSta & Num, DnSta & Num=  ,5000.3, 2 ,5000.3, 2 , 0 , 0 , 0 ,,
     1.4     1.4
   50.33   73.78
     1.4     1.4
    50.1   73.55
Pier Skew, UpSta & Num, DnSta & Num=  ,5013.9, 2 ,5013.9, 2 , 0 , 0 , 0 ,,
     3.2     3.2
   50.51   73.75
     3.2     3.2
   50.28   73.52
Pier Skew, UpSta & Num, DnSta & Num=  ,5039.5, 2 ,5039.5, 2 , 0 , 0 , 0 ,,
     1.2     1.2
   59.04    73.7
     1.2     1.2
   58.81   73.47
Pier Skew, UpSta & Num, DnSta & Num=  ,5048.7, 2 ,5048.7, 2 , 0 , 0 , 0 ,,
     1.4     1.4
   65.58   73.68
     1.4     1.4
   65.36   73.45
Abutment Skew #Up #Dn= , 2 , 2
  4888.6  4913.7
   72.78   61.02
  4888.6  4913.7
   72.55   60.79
Abutment Skew #Up #Dn= , 2 , 2
  5031.5 5063.99
   56.53   72.65
  5031.5 5063.99
    56.3   72.42
BR Coef= 1 , 1 , 0 ,1.25, 0 ,,,0.8,-1,2,0,
WSPro=,,,, 1 ,,,, 0 ,,,, 0 ,,,,-1 ,-1 ,-1 , 0 , 0 , 0 , 0 , 0
BC Design=,, 0 ,, 0 ,,,,,,
BC HTab HWMax=82.43
BC Use User HTab Curves=0
BC User HTab FreeFlow(D)= 0

Type RM Length L Ch R = 1 ,66585.0 ,97.4,105,126.5
BEGIN DESCRIPTION:
Downstream Section of Bridge/Culvert/Weir
END DESCRIPTION:
XS GIS Cut Line= 6
      3085543.38     13882716.28      3086018.68     13881416.85
      3086331.81     13879633.89      3086255.69     13878976.18
      3086200.69     13878736.66      3084893.06     13876293.64
#Sta/Elev= 30
  1019.7   80.03  1659.7   75.73  1839.7   76.93  1892.2   74.23  1989.7   76.03
  3291.3   73.13  3511.3   71.13  4376.5   73.53  4700.2   72.32  4842.8   74.39
  4881.3   74.93  4914.4   60.53  4959.7    60.6  4967.1   59.36  4972.3   55.65
  5000.3   51.13  5013.9   51.35  5027.4   54.44  5039.5   60.14  5048.7   67.04
  5063.5   70.84  5068.5   75.17  5108.6   73.64    5273   72.19  5992.6   78.73
  7226.8   78.92    7660   79.84  7712.6   78.53  7752.6   81.63  7859.6   82.43
#Mann= 9 ,-1 , 0
  1019.7    .045       0  1892.2     .08       0  4842.8     .04       0
  4881.3     .02       0  5068.5     .04       0  5108.6     .08       0
  7226.8     .05       0    7660     .12       0  7859.6     .99       0
#XS Ineff= 2 , 0
       0    4886    75.3    5065       0    75.3
Permanent Ineff=
       F       F
Bank Sta=4881.3,5068.5
XS Rating Curve= 0 ,0
Exp/Cntr=0.5,0.3

Type RM Length L Ch R = 1 ,66480.  ,708.7,602,361.2
BEGIN DESCRIPTION:
Antoine SB - D/S - XS 1
-Modified right bank location (PBS&J October 2009)
END DESCRIPTION:
XS GIS Cut Line= 6
      3085562.86      13882679.2      3086025.93     13881408.73
      3086430.85     13879628.23      3086330.91     13878929.46
      3086319.67     13878698.99      3084992.11     13876287.98
#Sta/Elev= 30
  1002.4   78.68  1702.4   74.21  2594.6   75.89  3324.6   74.56  3404.6   71.23
  3454.6   73.78  3774.6   76.38  3904.6   73.05  4270.6   73.92  4420.6   72.53
  4450.6   75.42  4680.6   72.86  4720.6   71.84  4800.6   75.91  4870.6   76.23
  4886.5   75.92  4926.5   70.58 4972.68   59.05 4977.59   55.61 5004.05   51.54
 5018.29   51.89 5032.42   54.68  5046.5   61.55  5066.5   67.73  5106.5   73.76
  5117.2   73.87  5507.2   73.39  6357.2   78.61  7117.2   78.63  7869.6   79.57
#Mann= 6 ,-1 , 0
  1002.4    .045       0  1702.4     .08       0  4680.6     .05       0
  4886.5     .04       0  5117.2     .08       0  7117.2     .05       0
#XS Ineff= 2 , 0
        4847.55375.225755115.759        75.22575
Permanent Ineff=
       F       F
Bank Sta=4870.6,5106.5
XS Rating Curve= 0 ,0
Exp/Cntr=0.3,0.1

Type RM Length L Ch R = 1 ,65878.0 ,144.3,228,229
BEGIN DESCRIPTION:
Cross Section E100-00-00-X46
END DESCRIPTION:
XS GIS Cut Line= 6
      3085543.91     13882737.73      3086390.32      13880433.3
      3087073.22     13879197.33      3086992.42      13878751.6
      3086151.07     13878305.23      3084928.26     13876045.13
#Sta/Elev= 30
   530.4    79.5  1401.2   74.16  2800.4      75  3015.8    74.7  3095.8    71.9
  3145.8    74.9  3195.8    73.5  3435.8    76.2  3635.8    72.8  3885.8    71.6
  4165.8    73.4  4205.8    71.4  4422.9    73.4  4692.9      70  4742.9    72.9
    4917   74.45  4970.7   57.69  4972.3   55.56  4991.9   53.89    5028   56.05
  5081.6   74.65  5104.4   73.92  5489.7    74.7  5559.7    72.9  6226.6    77.2
  7418.2   79.51  8182.7   79.59  8236.6    78.6  8276.6    81.6  8386.3    81.8
#Mann= 8 ,-1 , 0
   530.4    .045       0  1401.2     .08       0    4917     .04       0
  5081.6     .04       0  5104.4     .08       0  7418.2     .05       0
  8182.7     .12       0  8386.3     .99       0
#XS Ineff= 2 , 0
       0 4627.12    74.8 5406.78       0    74.8
Permanent Ineff=
       F       F
Bank Sta=4917,5081.6
XS Rating Curve= 0 ,0
Exp/Cntr=0.3,0.1

Type RM Length L Ch R = 1 ,65650.  ,447.1,146,99.3
BEGIN DESCRIPTION:
W Little York - U/S - XS 4
-Modified right bank location (PBS&J October 2009)
END DESCRIPTION:
XS GIS Cut Line= 6
      3086591.49     13880072.22      3087089.84     13879180.01
      3087114.02     13878542.23      3086912.97     13878420.16
      3086404.05     13878382.14      3085302.51     13876524.09
#Sta/Elev= 30
  3216.5    76.2  3446.5   72.92  3536.5   74.28  3656.5   73.41  3706.5   71.57
  3756.5   73.89  3976.5   73.28  4016.5   71.39  4066.5   73.41  4238.5   73.41
  4628.5   70.35  4728.5   73.03  4896.7   73.34  4916.7   71.87  4946.7   66.19
4968.923   58.464970.708    55.75000.878   49.145007.662   51.225043.723   54.43
  5056.7   64.28  5066.7   67.44  5111.9    74.3  5121.9   74.91  5622.2   73.41
  5912.2   76.35  6232.2    74.6  6312.2    76.6  7292.2   78.17  7782.3   79.93
#Mann= 4 ,-1 , 0
  3216.5     .08       0  4896.7     .04       0  5121.9     .08       0
  7292.2     .05       0
#XS Ineff= 2 , 0
         4374.45   72.87 5211.45           75.35
Permanent Ineff=
       F       F
Bank Sta=4896.7,5111.9
XS Rating Curve= 0 ,0
Exp/Cntr=0.5,0.3

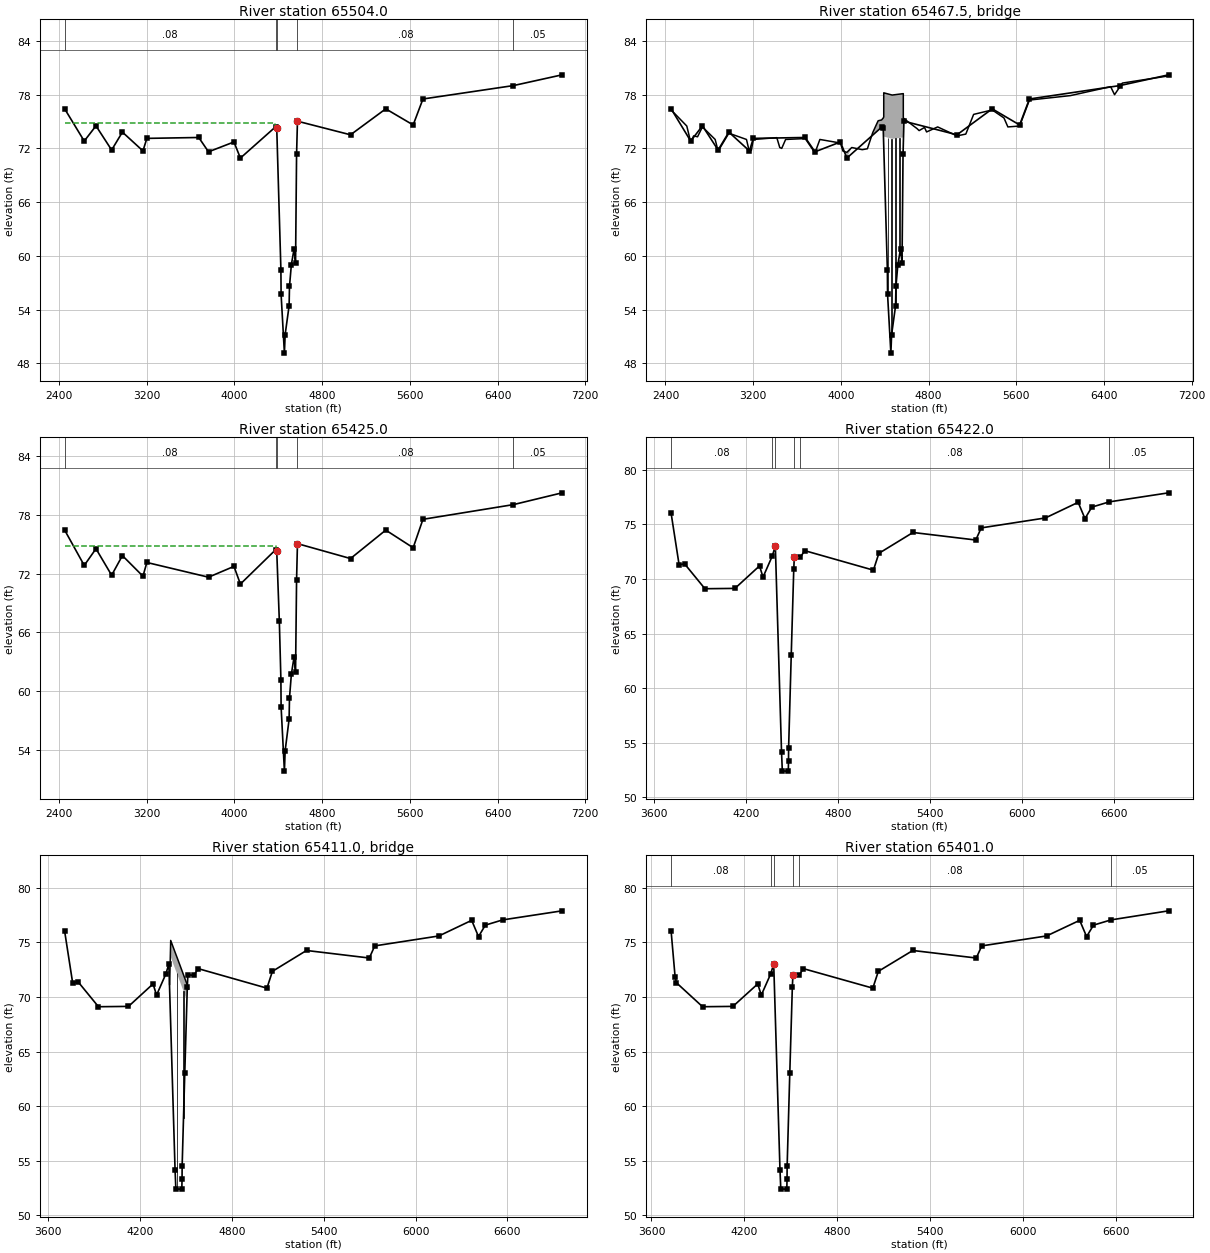
Type RM Length L Ch R = 1 ,65504.0 ,78.6,79,88.2
BEGIN DESCRIPTION:
Upstream Section of Bridge/Culvert/Weir
END DESCRIPTION:
XS GIS Cut Line= 5
        3086593.     13880072.01      3087481.94     13878494.69
      3087340.77     13878368.65      3086424.12     13878326.37
      3085359.11     13876444.85
#Sta/Elev= 30
 2451.58   76.43 2630.09   72.83  2737.2   74.53 2880.02   71.83  2978.2   73.83
 3165.65   71.73 3201.35   73.13 3674.42   73.23 3763.68   71.63 3995.75   72.73
 4054.39   70.93  4375.1   74.42  4385.9   74.31 4423.92   58.46 4425.71    55.7
 4455.88   49.14 4462.66   51.22 4498.72   54.43 4502.29   56.61 4519.52   59.04
 4544.15   60.78 4557.54   59.25 4566.83   71.34 4574.95   75.05    5059   73.53
 5380.33   76.43 5630.25   74.63 5719.51   77.53 6545.42   79.03 6988.86   80.23
#Mann= 5 ,-1 , 0
 2451.58     .08       0  4375.1     .04       0  4385.9     .02       0
 4574.95     .08       0 6545.42     .05       0
#XS Ineff= 2 , 0
       04373.608    74.84576.638       0    74.8
Permanent Ineff=
       F       F
Bank Sta=4385.9,4574.95
XS Rating Curve= 0 ,0
Skew Angle= 27
Exp/Cntr=0.5,0.3

Type RM Length L Ch R = 3 ,65467.5 ,,,
BEGIN DESCRIPTION:
W LITTLE YORK
Structure ID: E100-00-00-38
Bridge has 26.8 degree skew with the channel.
END DESCRIPTION:
Bridge Culvert--1,0,-1,-1, 0
Deck Dist Width WeirC Skew NumUp NumDn MinLoCord MaxHiCord MaxSubmerge Is_Ogee
10,53,2.6,26.8, 60, 60, , , 0.95, 0, ,,,
 2451.58 2594.39 2630.09 2656.87 2692.57  2737.2 2853.24 2880.02  2978.2 3138.87
 3165.65  3183.5 3201.35 3415.57 3442.35  3460.2  3495.93674.421 3763.68 3808.31
3995.751 4018.69 4054.39 4099.02 4194.35 4195.244241.6614290.129 4339.844371.081
  4385.9 4390.784390.879 4391.084391.169 4467.57 4569.244569.331  4570.3  4570.4
 4574.954665.549 4692.95 4713.57 4762.664781.581 4882.62    5059 5139.33 5210.74
 5380.33 5487.44 5523.14 5630.255719.509  6094.4 6460.36 6496.066567.4716988.859
   76.31   74.51   72.71   73.41   73.31   74.41   73.01   71.71   73.71   73.01
   71.61   71.81   73.01   73.21   72.11   72.01   73.01   73.11   71.51   73.01
   72.61   71.71   71.57   72.11   71.87   71.87   71.97   73.77    75.1   75.19
    75.4   75.52   78.22   78.22   78.22   77.97   78.13   75.43   75.41   75.41
   75.34   74.49   74.24      74   74.35   73.85   74.41   73.41   73.61   75.81
   76.31   75.41   74.41   74.51   77.41   77.91   78.91   78.01   79.31   80.11
   76.31   74.51   72.71   73.41   73.31   74.41   73.01   71.71   73.71   73.01
   71.61   71.81   73.01   73.21   72.11   72.01   73.01   73.11   71.51   73.01
   72.61   71.71   70.81   72.11   71.26   71.57   71.92   72.99   74.06   74.34
   74.19    72.7   72.65   72.53   73.33   73.08   73.24   73.24   73.22   72.91
   74.93   74.49   74.24    73.7   74.35   73.85   74.41   73.41   73.61   75.81
   76.31   75.41   74.41   74.51   77.41   77.91   78.91   78.01   79.31   80.11
 2451.58 2594.39 2630.09 2656.87 2692.57  2737.2 2853.24 2880.02  2978.2 3138.87
 3165.65  3183.5 3201.35 3415.57 3442.35  3460.2  3495.93674.421 3763.68 3808.31
3995.751 4018.69 4054.39 4099.02 4194.35 4195.244241.6614290.129 4339.844371.081
  4385.9 4390.784390.879 4391.084391.169 4467.57 4569.244569.331  4570.3  4570.4
 4574.954665.549 4692.95 4713.57 4762.664781.581 4882.62    5059 5139.33 5210.74
 5380.33 5487.44 5523.14 5630.255719.509  6094.4 6460.36 6496.066567.4716988.859
   76.31   74.51   72.71   73.41   73.31   74.41   73.01   71.71   73.71   73.01
   71.61   71.81   73.01   73.21   72.11   72.01   73.01   73.11   71.51   73.01
   72.61   71.71   71.57   72.11   71.87   71.87   71.97   73.77    75.1   75.19
    75.4   75.52   78.22   78.22   78.22   77.97   78.13   75.43   75.41   75.41
   75.34   74.49   74.24      74   74.35   73.85   74.41   73.41   73.61   75.81
   76.31   75.41   74.41   74.51   77.41   77.91   78.91   78.01   79.31   80.11
   76.31   74.51   72.71   73.41   73.31   74.41   73.01   71.71   73.71   73.01
   71.61   71.81   73.01   73.21   72.11   72.01   73.01   73.11   71.51   73.01
   72.61   71.71   70.81   72.11   71.26   71.57   71.92   72.99   74.06   74.34
   74.19    72.7   72.65   72.53   73.33   73.08   73.24   73.24   73.22   72.91
   74.93   74.49   74.24    73.7   74.35   73.85   74.41   73.41   73.61   75.81
   76.31   75.41   74.41   74.51   77.41   77.91   78.91   78.01   79.31   80.11
Pier Skew, UpSta & Num, DnSta & Num=  ,4425.708, 2 ,4425.708, 2 , 0 , 0 , 0 ,,
     1.2     1.2
   55.05   74.22
     1.2     1.2
   55.82   74.99
Pier Skew, UpSta & Num, DnSta & Num=  ,4462.662, 2 ,4462.662, 2 , 0 , 0 , 0 ,,
     3.2     3.2
   49.66    74.1
     3.2     3.2
   50.43   74.87
Pier Skew, UpSta & Num, DnSta & Num=  ,4498.723, 2 ,4498.723, 2 , 0 , 0 , 0 ,,
     3.2     3.2
   53.16   74.13
     3.2     3.2
   53.93    74.9
Pier Skew, UpSta & Num, DnSta & Num=  ,4534.247, 2 ,4534.247, 2 , 0 , 0 , 0 ,,
     1.2     1.2
   58.06   74.19
     1.2     1.2
   58.83   74.96
BR Coef= 1 , 1 , 0 ,1.25, 0 ,,,0.8,-1,2,0,
WSPro=,,,, 1 ,,,, 0 ,,,, 0 ,,,,-1 ,-1 ,-1 , 0 , 0 , 0 , 0 , 0
BC Design=,, 0 ,, 0 ,,,,,,
BC HTab HWMax=80.23
BC Use User HTab Curves=0
BC User HTab FreeFlow(D)= 0

Type RM Length L Ch R = 1 ,65425.0 ,35.6,3,2
BEGIN DESCRIPTION:
Downstream Section of Bridge/Culvert/Weir
END DESCRIPTION:
XS GIS Cut Line= 5
      3086605.97     13880075.98      3087531.87     13878431.92
      3087371.26     13878296.43      3086469.57     13878267.03
      3085367.25      13876425.7
#Sta/Elev= 30
 2451.58   76.43 2630.09   72.83  2737.2   74.53 2880.02   71.83  2978.2   73.83
 3165.65   71.73 3201.35   73.13 3763.68   71.63 3995.75   72.73 4054.39   70.93
  4375.1   74.42  4385.9   74.31 4409.46   67.21 4423.92   61.18 4425.71   58.42
 4455.88   51.86 4462.66   53.94 4498.72   57.15 4502.29   59.33 4519.52   61.76
 4544.15    63.5 4557.54   61.97 4566.83   71.34 4574.95   75.05    5059   73.53
 5380.33   76.43 5630.25   74.63 5719.51   77.53 6545.42   79.03 6988.86   80.23
#Mann= 5 ,-1 , 0
 2451.58     .08       0  4375.1     .04       0  4385.9     .02       0
 4574.95     .08       0 6545.42     .05       0
#XS Ineff= 2 , 0
       04382.063   74.784576.638       0   74.84
Permanent Ineff=
       F       F
Bank Sta=4385.9,4574.95
XS Rating Curve= 0 ,0
Skew Angle= 27
Exp/Cntr=0.5,0.3

Type RM Length L Ch R = 1 ,65422.0 ,23.1,21,20
BEGIN DESCRIPTION:
Upstream Section of Bridge/Culvert/Weir
END DESCRIPTION:
XS GIS Cut Line= 4
      3087925.74     13878164.55       3087715.6     13878303.13
      3086477.68     13878265.64      3085377.27     13876413.69
#Sta/Elev= 30
3709.706      76 3761.74   71.29 3797.38   71.383930.319    69.1 4126.34   69.13
4286.722   71.194309.478   70.164370.208    72.14389.936   73.014430.298   54.19
4435.555   52.414474.492    52.44476.007   53.374476.542    54.54493.738   63.04
4510.311   70.944514.053   72.034553.757   71.974580.754   72.595030.088    70.8
5065.729   72.34 5288.48   74.255698.342   73.565733.982   74.676152.756   75.58
6366.598   77.016411.148   75.526455.699   76.576568.856   77.05 6956.89   77.88
#Mann= 6 ,-1 , 0
3709.706     .08       04370.208     .04       04389.936     .02       0
4514.053     .04       04553.757     .08       06568.856     .05       0
#XS Ineff= 2 , 0
       04380.127   69.144520.138       0    70.8
Permanent Ineff=
       F       F
Bank Sta=4389.936,4514.053
XS Rating Curve= 0 ,0
Skew Angle= 27
Exp/Cntr=0.5,0.3

Type RM Length L Ch R = 3 ,65411.0 ,,,
BEGIN DESCRIPTION:
PL1_E100-00-00-38
Pipeline has 26.8 degree skew with the channel.
END DESCRIPTION:
Bridge Culvert--1,0,-1,-1, 0
Deck Dist Width WeirC Skew NumUp NumDn MinLoCord MaxHiCord MaxSubmerge Is_Ogee
10,2,2.6,26.8, 17, 17, , , 0.95, 0, ,,,
 4394.55 4397.81 4401.91  4421.1 4438.15  4438.6 4439.31 4441.99 4443.42 4482.42
 4483.94 4484.48  4501.7 4510.95 4511.05 4514.74 4518.31
   71.15    72.8   75.17   74.44    73.8   73.79   73.76   73.66   73.61   72.14
   72.08   72.06   71.41   71.07   71.06   71.04    70.7
      70    71.6   73.67   72.94    72.3   72.29   72.26   72.16   72.11   70.64
   70.58   70.56   69.91   69.64   69.69      69
 4394.55 4397.81 4401.91  4421.1 4438.15  4438.6 4439.31 4441.99 4443.42 4482.42
 4483.94 4484.48  4501.7 4510.95 4511.05 4514.74 4518.31
   71.15    72.8   75.17   74.44    73.8   73.79   73.76   73.66   73.61   72.14
   72.08   72.06   71.41   71.07   71.06   71.04    70.7
      70    71.6   73.67   72.94    72.3   72.29   72.26   72.16   72.11   70.64
   70.58   70.56   69.91   69.64   69.69      69
Pier Skew, UpSta & Num, DnSta & Num=  ,4441.239, 2 ,4441.239, 2 , 0 , 0 , 0 ,,
     1.2     1.2
   54.52   73.21
     1.2     1.2
   54.52   73.21
Pier Skew, UpSta & Num, DnSta & Num=  ,4485.511, 2 ,4485.511, 2 , 0 , 0 , 0 ,,
     1.2     1.2
   55.94   71.54
     1.2     1.2
   55.94   71.54
BR Coef= 1 , 1 , 0 ,1.25, 0 ,,,0.8,-1,2,0,
WSPro=,,,, 1 ,,,, 0 ,,,, 0 ,,,,-1 ,-1 ,-1 , 0 , 0 , 0 , 0 , 0
BC Design=,, 0 ,, 0 ,,,,,,
BC HTab HWMax=77.88
BC Use User HTab Curves=0
BC User HTab FreeFlow(D)= 0

Type RM Length L Ch R = 1 ,65401.0 ,106.5,133,220.8
BEGIN DESCRIPTION:
Downstream Section of Bridge/Culvert/Weir
END DESCRIPTION:
XS GIS Cut Line= 4
      3087921.23     13878156.08       3087712.6      13878283.9
      3086498.57     13878247.71      3085398.19     13876403.65
#Sta/Elev= 30
3727.169      76 3752.83   71.83 3761.74   71.293930.319    69.1 4126.34   69.13
4286.722   71.194309.478   70.164370.208    72.14389.936   73.014430.298   54.19
4435.555   52.414474.492    52.44476.007   53.374476.542    54.54493.738   63.04
4510.311   70.944514.053   72.034553.757   71.974580.754   72.595030.088    70.8
5065.729   72.34 5288.48   74.255698.342   73.565733.982   74.676152.756   75.58
6366.598   77.016411.148   75.526455.699   76.576568.856   77.056940.763   77.88
#Mann= 6 ,-1 , 0
3727.169     .08       04370.208     .04       04389.936     .02       0
4514.053     .04       04553.757     .08       06568.856     .05       0
#XS Ineff= 2 , 0
       04370.224   69.144524.181       0    70.8
Permanent Ineff=
       F       F
Bank Sta=4389.936,4514.053
XS Rating Curve= 0 ,0
Skew Angle= 27
Exp/Cntr=0.5,0.3

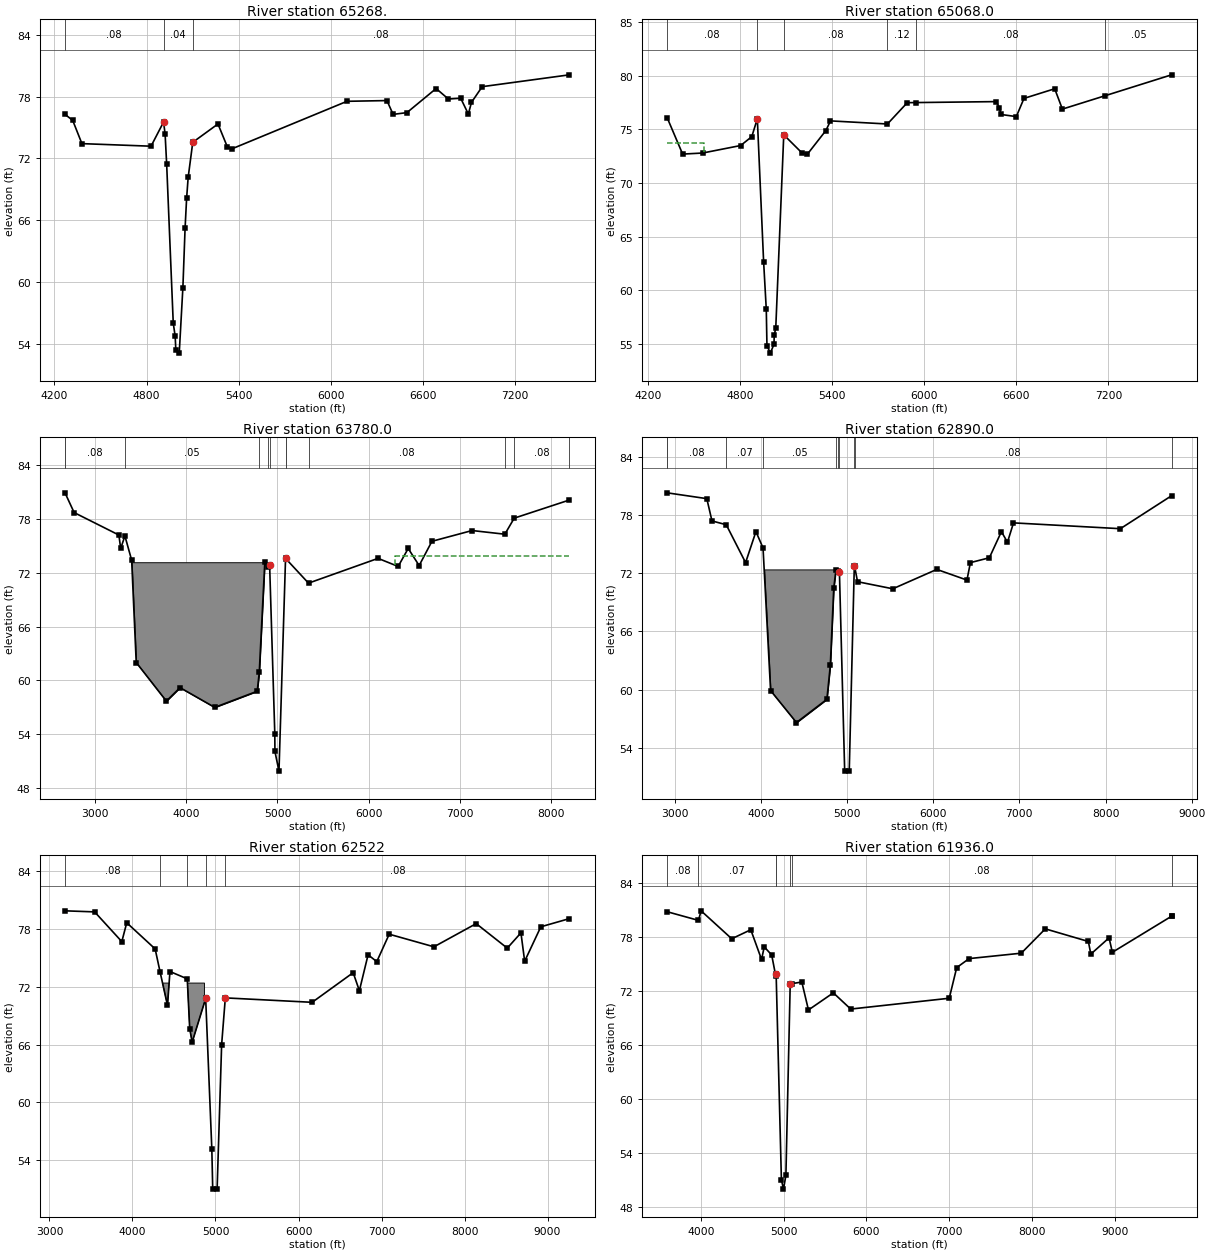
Type RM Length L Ch R = 1 ,65268.  ,41.6,200,252.9
BEGIN DESCRIPTION:
PL_38 - D/S - XS 1
END DESCRIPTION:
XS GIS Cut Line= 4
      3087915.38     13878153.16      3087306.09     13878207.79
      3087084.23     13878083.92      3085376.62     13876372.24
#Sta/Elev= 30
  4269.1   76.27  4319.1   75.69  4379.1   73.43  4829.1   73.18  4910.8   75.53
  4920.8   74.34  4930.8   71.45  4973.7   56.01  4986.3   54.72  4990.6   53.37
  5012.7   53.09 5036.42   59.44  5050.8   65.23  5060.8   68.14  5070.8   70.15
  5100.8   73.56  5264.9   75.34  5324.9   73.15  5354.9   72.92  6104.9   77.54
  6364.9   77.61  6404.9   76.27  6494.9   76.44  6684.9   78.78  6764.9   77.76
  6844.9   77.84  6894.9    76.3  6914.9   77.43  6984.9   78.96  7552.7   80.11
#Mann= 3 ,-1 , 0
  4269.1     .08       0  4910.8     .04       0  5100.8     .08       0
Bank Sta=4910.8,5100.8
XS Rating Curve= 0 ,0
Exp/Cntr=0.3,0.1

Type RM Length L Ch R = 1 ,65068.0 ,1289,1288,1052.6
BEGIN DESCRIPTION:
Cross Section E100-00-00-X45
END DESCRIPTION:
XS GIS Cut Line= 4
       3087913.9     13878149.11      3087435.41     13878159.03
      3087208.19     13877811.78      3085333.66     13876327.66
#Sta/Elev= 30
    4327    76.1  4427.8    72.7  4557.8    72.8  4805.6    73.5  4878.1   74.33
  4914.2      76  4955.1   62.66  4972.5    58.2  4976.8   54.83  4998.9   54.12
  5022.6   54.95  5024.2    55.8  5034.2   56.46  5086.3    74.5  5205.6    72.8
  5240.6    72.7  5360.6    74.9  5390.6    75.8  5761.4   75.51  5890.6    77.5
  5946.2   77.51  6470.6    77.6  6490.6      77  6500.6    76.4  6600.6    76.2
  6650.6    77.9  6850.6    78.8  6900.6    76.9  7178.9   78.15  7611.5    80.1
#Mann= 6 ,-1 , 0
    4327     .08       0  4914.2     .04       0  5086.3     .08       0
  5761.4     .12       0  5946.2     .08       0  7178.9     .05       0
#XS Ineff= 2 , 0
         4569.49   73.74
Permanent Ineff=
       F       F
Bank Sta=4914.2,5086.3
XS Rating Curve= 0 ,0
Exp/Cntr=0.3,0.1

Type RM Length L Ch R = 1 ,63780.0 ,730.8,890,1005.1
BEGIN DESCRIPTION:
Cross Section E100-00-00-X44
END DESCRIPTION:
XS GIS Cut Line= 4
      3090603.25     13878219.56      3088915.84     13877772.65
      3088397.94     13877503.61      3085551.57     13876050.31
#Sta/Elev= 30
  2672.7    80.9  2772.7    78.7  3262.7    76.2  3282.7    74.7  3328.7    76.1
  3402.7    73.4  3452.7      62  3782.7    57.7  3932.7    59.2  4312.7      57
  4778.3    58.8  4800.7    60.9  4861.3   73.17  4893.5   72.67  4914.1   72.81
  4970.6   54.09  4972.1   52.09  5016.5    49.9  5088.7   73.69  5095.3   73.52
    5340   70.84  6101.9    73.6  6321.9    72.7  6431.9    74.7  6551.9    72.8
  6691.9    75.5  7131.9    76.7  7490.5   76.29  7593.4   78.08  8197.8    80.1
#Mann= 12 , 1 , 0
  2672.7     .99       0  2672.7     .08       0  3328.7     .05       0
  4800.7     .12       0  4893.5     .04       0  4914.1     .02       0
  5088.7     .04       0  5095.3     .12       0    5340     .08       0
  7490.5     .05       0  7593.4     .08       0  8197.8     .99       0
#XS Ineff= 2 , 0
                         6291.46            73.9
Permanent Ineff=
       F       F
#Block Obstruct= 2 ,-1
  3395.6  4861.3   73.17  4861.4  4861.5      70
Bank Sta=4914.1,5088.7
XS Rating Curve= 0 ,0
Exp/Cntr=0.3,0.1

Type RM Length L Ch R = 1 ,62890.0 ,367.7,368.4,262.9
BEGIN DESCRIPTION:
Cross Section E100-00-00-X43
END DESCRIPTION:
XS GIS Cut Line= 5
      3090632.97     13878080.89      3089109.63     13877153.85
      3088994.87     13876864.64      3088891.33     13876621.97
      3085630.81     13875366.85
#Sta/Elev= 30
    2914    80.3    3374    79.7    3434    77.4  3599.4   77.01    3824    73.1
    3944    76.3  4026.4   74.61    4114    59.9    4414    56.6  4767.2      59
  4807.2    62.5  4847.2    70.5  4872.3   72.34  4893.3   72.19  4912.8   72.09
  4973.6   51.59  5026.5    51.6  5085.4   72.76    5088   72.75  5122.9   71.13
  5532.2    70.4  6042.2    72.4  6392.2    71.3  6432.2    73.1  6652.2    73.6
  6792.2    76.3  6862.2    75.2  6932.2    77.2  8172.2    76.6    8766      80
#Mann= 10 , 1 , 0
    2914     .99       0    2914     .08       0  3599.4     .07       0
  4026.4     .05       0  4872.3     .12       0  4893.3     .04       0
  4912.8     .02       0  5085.4     .04       0    5088     .08       0
    8766     .99       0
#Block Obstruct= 2 ,-1
  4033.2  4863.7    72.4  4863.9  4864.2      70
Bank Sta=4912.8,5085.4
XS Rating Curve= 0 ,0
Exp/Cntr=0.3,0.1

Type RM Length L Ch R = 1 ,62522   ,645.9,585.6,220.2
BEGIN DESCRIPTION:
-New section (PBS&J-September 2009)
-Blocked obstruction for detention pond at 4866.89 at elev. 72.4 (PBS&J-September 2009)
END DESCRIPTION:
XS GIS Cut Line= 4
3090701.9754006613877863.93975233089451.5771743913877031.4553717
3089242.6937666313876477.91434113085497.0666538213875125.9485376
#Sta/Elev= 30
 3187.22   79.91 3544.17    79.8 3871.38   76.71 3930.87   78.67 4272.95   75.95
 4332.44   73.56 4421.67   70.08 4451.42    73.6 4659.65   72.84 4689.39   67.66
 4718.98   66.25 4881.67    70.8 4955.62   55.17  4966.6   50.98  5019.5   50.99
 5073.96   66.01 5118.33   70.86 6164.29    70.4 6658.32   73.48 6733.17   71.61
 6837.96   75.34 6942.75   74.63 7092.46   77.48  7631.4   76.17 8140.41   78.58
 8514.67   76.03 8679.34   77.62 8724.25   74.67 8918.88   78.25 9263.21    79.1
#Mann= 5 ,-1 , 0
 3187.22     .08       0 4332.44     .07       0 4659.65     .05       0
 4881.67     .02       0 5118.33     .08       0
#Block Obstruct= 2 , 0
       0 4866.89    72.4               0
Bank Sta=4881.67,5118.33
XS Rating Curve= 0 ,0
Exp/Cntr=0.3,0.1

Type RM Length L Ch R = 1 ,61936.0 ,928.1,810.8,341.6
BEGIN DESCRIPTION:
Cross Section E100-00-00-X42
END DESCRIPTION:
XS GIS Cut Line= 5
      3091071.79     13877055.88      3090040.31     13876498.32
      3089815.44     13876434.18      3089304.33     13876258.57
      3085333.66     13875069.69
#Sta/Elev= 30
  3593.7    80.8  3971.8   79.84  4003.7    80.9  4373.7    77.8  4603.7    78.8
  4733.7    75.5  4766.2    76.9  4856.2      76  4905.4   73.66  4909.9   73.86
  4973.4   51.07  4998.6   50.02  5027.7   51.54  5079.9   72.82  5098.9   72.82
  5220.1      73  5300.1    69.9  5600.5    71.8  5810.5      70  7000.5    71.2
  7090.5    74.6  7240.5    75.6  7870.5    76.2  8160.5    78.9  8680.5    77.5
  8710.5    76.1  8930.5    77.9  8970.5    76.3  9685.2    80.3  9685.3    80.3
#Mann= 7 ,-1 , 0
  3593.7     .08       0  3971.8     .07       0  4905.4     .04       0
  4909.9     .02       0  5079.9     .04       0  5098.9     .08       0
  9685.2     .99       0
Bank Sta=4909.9,5079.9
XS Rating Curve= 0 ,0
Exp/Cntr=0.3,0.1

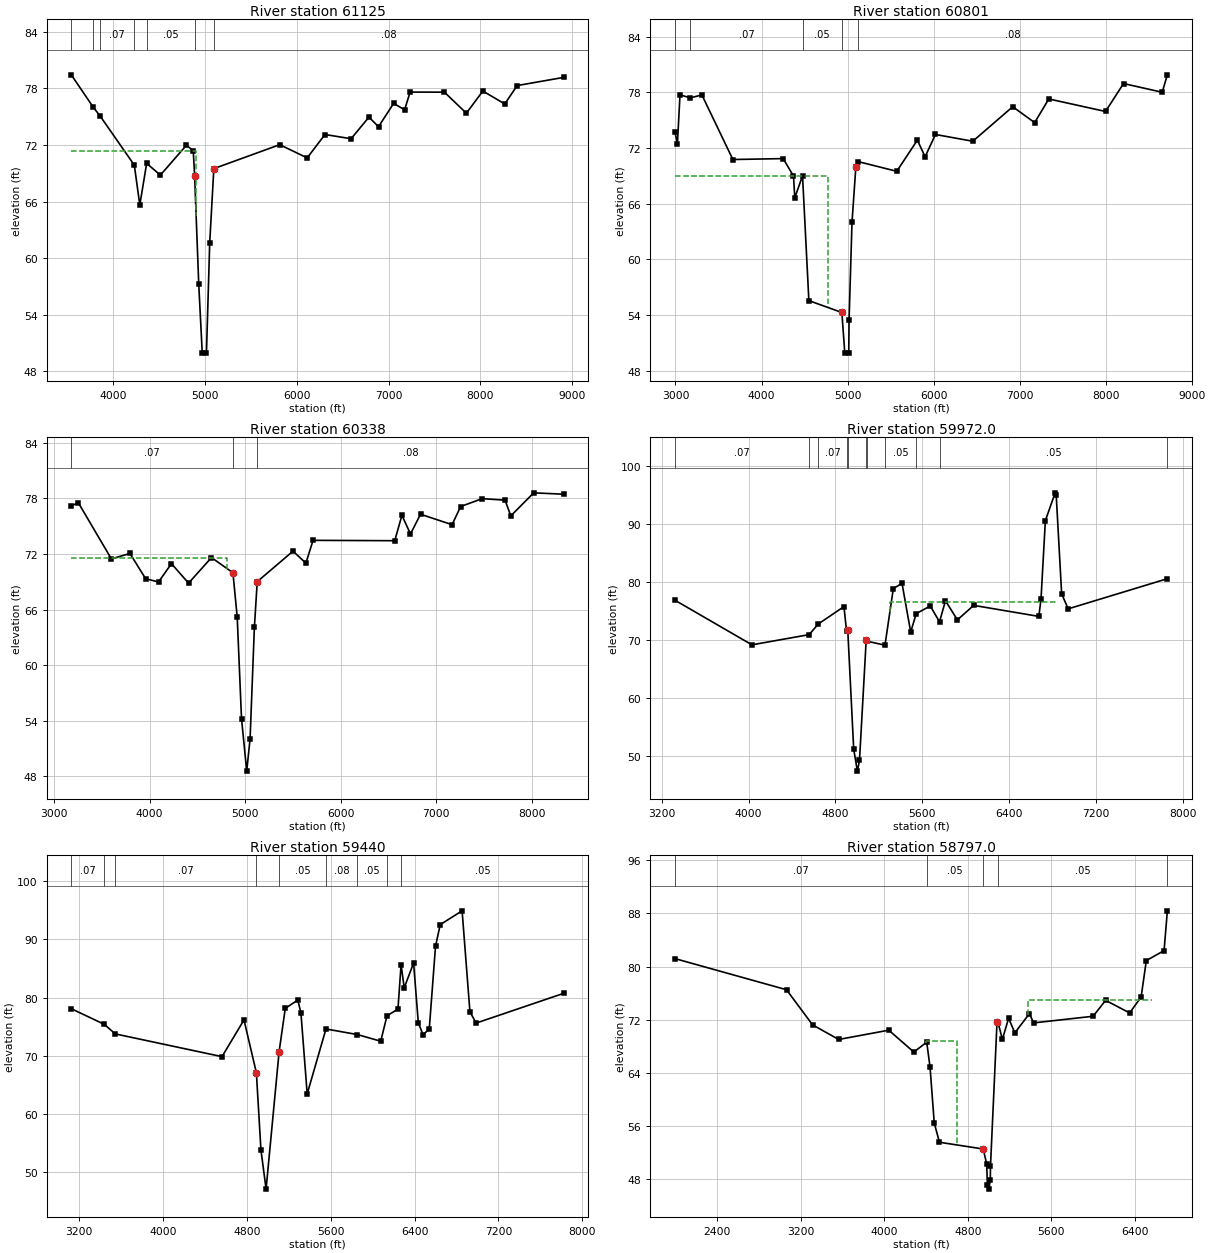
Type RM Length L Ch R = 1 ,61125   ,336.5,324.5,164.8
BEGIN DESCRIPTION:
-New section (PBS&J-September 2009)
-Ineffective area at station 4904.56 at elevation 71.05 (PBS&J-September 2009)
END DESCRIPTION:
XS GIS Cut Line= 4
3090690.5003296813876067.57908213089624.1106140513875601.4326795
3089232.43212771 13875900.729472  3085646.34990513874963.7621922
#Sta/Elev= 30
  3544.9   79.44 3783.62   76.01 3858.24   75.08 4231.25   69.86 4290.94   65.63
 4365.54   70.05 4514.75    68.8 4798.34   71.97 4873.02   71.39 4887.96   68.72
 4932.79   57.22  4970.9   49.92  5016.7   49.95 5052.29   61.65 5097.09   69.49
 5814.42   72.03 6113.33   70.63 6307.62   73.11 6591.58   72.66 6785.87   74.95
 6890.49   73.94 7054.88   76.41 7174.45   75.73 7234.23   77.61 7607.85    77.6
 7846.98   75.37 8026.33   77.72 8265.45   76.35 8399.96    78.3  8908.1   79.17
#Mann= 7 ,-1 , 0
  3544.9     .07       0 3783.62     .08       0 3858.24     .07       0
 4231.25     .04       0 4365.54     .05       0 4887.96     .02       0
 5097.09     .08       0
#XS Ineff= 2 , 0
  3544.9 4904.56   71.39          3544.9
Permanent Ineff=
       F       F
Bank Sta=4887.96,5097.09
XS Rating Curve= 0 ,0
Exp/Cntr=0.6,0.4

Type RM Length L Ch R = 1 ,60801   ,343.6,462.6,589.8
BEGIN DESCRIPTION:
-New section (PBS&J-September 2009)
-Ineffective area due to detention pond at station 4820.79 at elevation 56.28 (PBS&J-September 2009)
END DESCRIPTION:
XS GIS Cut Line= 4
3090942.7302324813875805.7708286 3089582.604427513875211.9130828
3088924.8910100613875735.52958993085636.3239228813874873.4780233
#Sta/Elev= 30
 2992.29   73.77 3022.27   72.43 3052.25   77.72 3172.18    77.4  3307.1   77.71
  3666.9   70.75 4251.54   70.85 4371.48   68.97 4386.46   66.62 4476.42      69
 4550.15   55.54 4933.63   54.26  4967.9   49.88  5013.7   49.91  5017.3   53.43
 5051.62   64.01 5095.88    69.9 5125.37   70.52 5571.71   69.48 5811.33   72.84
 5901.19   71.04    6021   73.45 6455.33   72.72 6919.59   76.44 7174.21   74.73
 7338.94   77.28 7997.92   75.93 8207.58   78.94 8656.88      78 8716.79   79.88
#Mann= 5 ,-1 , 0
 2992.29     .08       0 3172.18     .07       0 4476.42     .05       0
 4933.63     .04       0 5125.37     .08       0
#XS Ineff= 2 , 0
       0    4770      69               0
Permanent Ineff=
       F       F
Bank Sta=4933.63,5095.88
XS Rating Curve= 0 ,0
Exp/Cntr=0.6,0.4

Type RM Length L Ch R = 1 ,60338   ,146.5,366.2,545
BEGIN DESCRIPTION:
-New section (PBS&J-September 2009)
-Ineffective area at station 4812.97 at elevation 71.32 (PBS&J-September 2009)
END DESCRIPTION:
XS GIS Cut Line= 4
3090744.7776505613875678.05948543089416.6602833913875128.9772904
3088638.6180523513875130.69665053085733.6449932213874684.4179099
#Sta/Elev= 30
 3181.31   77.23 3256.16   77.52 3600.48   71.48 3795.09   72.06 3959.76   69.33
  4094.5   68.99 4229.23   70.96 4408.87   68.86 4648.38   71.62 4872.82   69.98
  4917.7   65.19 4962.59   54.24  5017.1   48.56 5052.36   52.06 5097.25   64.07
 5127.18   69.02 5501.47   72.31 5636.42   71.02  5711.4   73.48 6566.12   73.44
 6641.09   76.18 6731.06   74.17 6836.03    76.3 7165.92   75.17 7255.89   77.13
 7480.82   77.98 7720.74   77.82 7780.72   76.12 8020.64   78.61 8335.54   78.46
#Mann= 3 ,-1 , 0
 3181.31     .07       0 4872.82     .04       0 5127.18     .08       0
#XS Ineff= 2 , 0
 3181.31 4812.97   71.62         3181.31
Permanent Ineff=
       F       F
Bank Sta=4872.82,5127.18
XS Rating Curve= 0 ,0
Exp/Cntr=0.6,0.4

Type RM Length L Ch R = 1 ,59972.0 ,758.5,531.8,290.5
BEGIN DESCRIPTION:
Cross Section E100-00-00-X40
END DESCRIPTION:
XS GIS Cut Line= 5
       3090726.1     13875634.11       3089326.5     13875056.29
      3089270.63     13874900.66      3089148.22     13874591.47
      3086809.54     13873643.33
#Sta/Elev= 30
  3321.1    76.9  4031.1    69.2  4558.4   70.96  4640.5   72.77  4878.5   75.79
  4902.6   71.53  4913.6   71.72  4968.2   51.23  5002.1   47.43  5021.6   49.27
  5083.1   69.96  5094.9   69.81  5256.3   69.14  5333.2    78.9  5413.2    79.8
  5493.2    71.4  5543.8   74.57  5673.2    75.9  5758.6   73.16  5813.2    76.8
  5923.2    73.5  6073.2      76  6673.2    74.1  6693.2    77.1  6733.2    90.6
  6823.2    95.4  6833.2      95  6883.2      78  6943.2    75.4  7856.7    80.6
#Mann= 11 ,-1 , 0
  3321.1     .07       0  4558.4     .04       0  4640.5     .07       0
  4902.6     .04       0  4913.6     .04       0  5083.1     .04       0
  5094.9     .08       0  5256.3     .05       0  5543.8     .08       0
  5758.6     .05       0  7856.7     .99       0
#XS Ineff= 1 ,-1
 5300.78    6845    76.6
Permanent Ineff=
       F
Bank Sta=4913.6,5083.1
XS Rating Curve= 0 ,0
Exp/Cntr=0.3,0.1

Type RM Length L Ch R = 1 ,59440   ,214.1,643.2,885.5
BEGIN DESCRIPTION:
-New section (PBS&J-September 2009)
END DESCRIPTION:
XS GIS Cut Line= 4
3091192.5655476113875222.28962943089645.66190319 13874465.599921
 3089368.368649313874547.81409823086877.7926156513873540.2702875
#Sta/Elev= 30
 3126.09   78.07 3440.55   75.38 3545.38   73.73 4563.65   69.81 4773.29   76.14
 4891.54   67.03 4934.92   53.76  4984.1   46.98 5108.46   70.69 5167.23   78.14
 5286.63   79.56  5316.5   77.34  5376.2   63.39  5555.3   74.58 5853.81   73.62
 6077.71   72.47 6137.41   76.85 6241.88   78.01 6271.75   85.65 6301.59   81.67
 6391.15   85.95 6435.92   75.65 6480.71   73.61 6540.41   74.53  6600.1   88.81
 6644.88   92.56 6853.84   94.94 6928.47   77.52 6988.17    75.6 7824.03   80.73
#Mann= 9 ,-1 , 0
 3126.09     .07       0 3440.55     .08       0 3545.38     .07       0
 4891.54     .04       0 5108.46     .05       0  5555.3     .08       0
 5853.81     .05       0 6137.41     .08       0 6271.75     .05       0
#XS Ineff= 2 , 0
       0                    5225       0    76.6
Permanent Ineff=
       F       F
Bank Sta=4891.54,5108.46
XS Rating Curve= 0 ,0
Exp/Cntr=0.6,0.4

Type RM Length L Ch R = 1 ,58797.0 ,261.4,252.6,128.8
BEGIN DESCRIPTION:
Cross Section E100-00-00-X39
PBS&J modified ineffective flow areas to reflect inline storage  basins.
END DESCRIPTION:
XS GIS Cut Line= 5
      3091896.97      13875544.9      3089755.95     13874362.87
      3089371.52     13873952.29      3089175.75     13873738.73
      3087776.62     13873487.51
#Sta/Elev= 30
  1993.2    81.2  3063.2    76.5  3313.2    71.2  3563.2      69  4043.2    70.4
  4283.2    67.1  4406.7    68.6  4438.8    64.8  4478.8    56.4  4528.8    53.5
  4948.4   52.48  4981.5   50.21  4987.9   47.07  5002.3   46.43  5015.9   47.84
  5017.7   49.88  5080.3    71.6  5091.3   71.51  5131.3      69  5191.3    72.2
  5251.3      70    5391    72.9    5431    71.5    6001    72.5    6121    74.9
    6351      73    6461    75.4    6511    80.9    6681    82.4  6712.5    88.4
#Mann= 5 ,-1 , 0
  1993.2     .07       0  4406.7     .05       0  4948.4     .04       0
  5091.3     .05       0  6712.5     .99       0
#XS Ineff= 2 ,-1
    4400    4695    68.7    5380    6570      75
Permanent Ineff=
       F       F
Bank Sta=4948.4,5080.3
XS Rating Curve= 0 ,0
Exp/Cntr=0.6,0.4