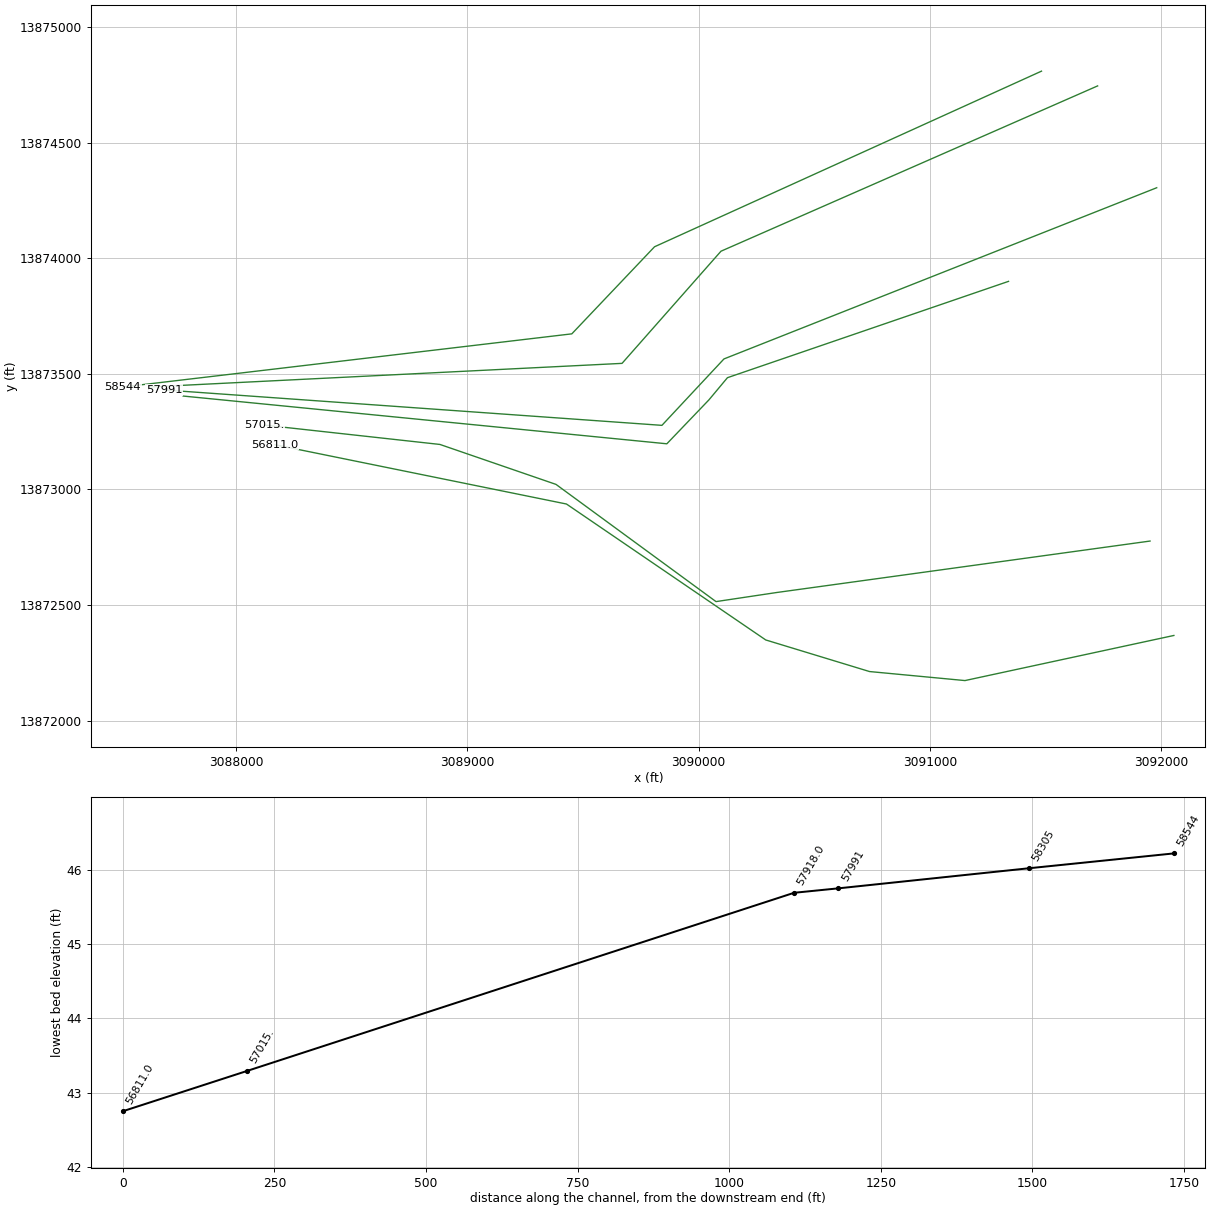
HEC-RAS study E100-00-00.prj: E100-00-00

--- E100-00-00.g02 (geometry) --- (continued)

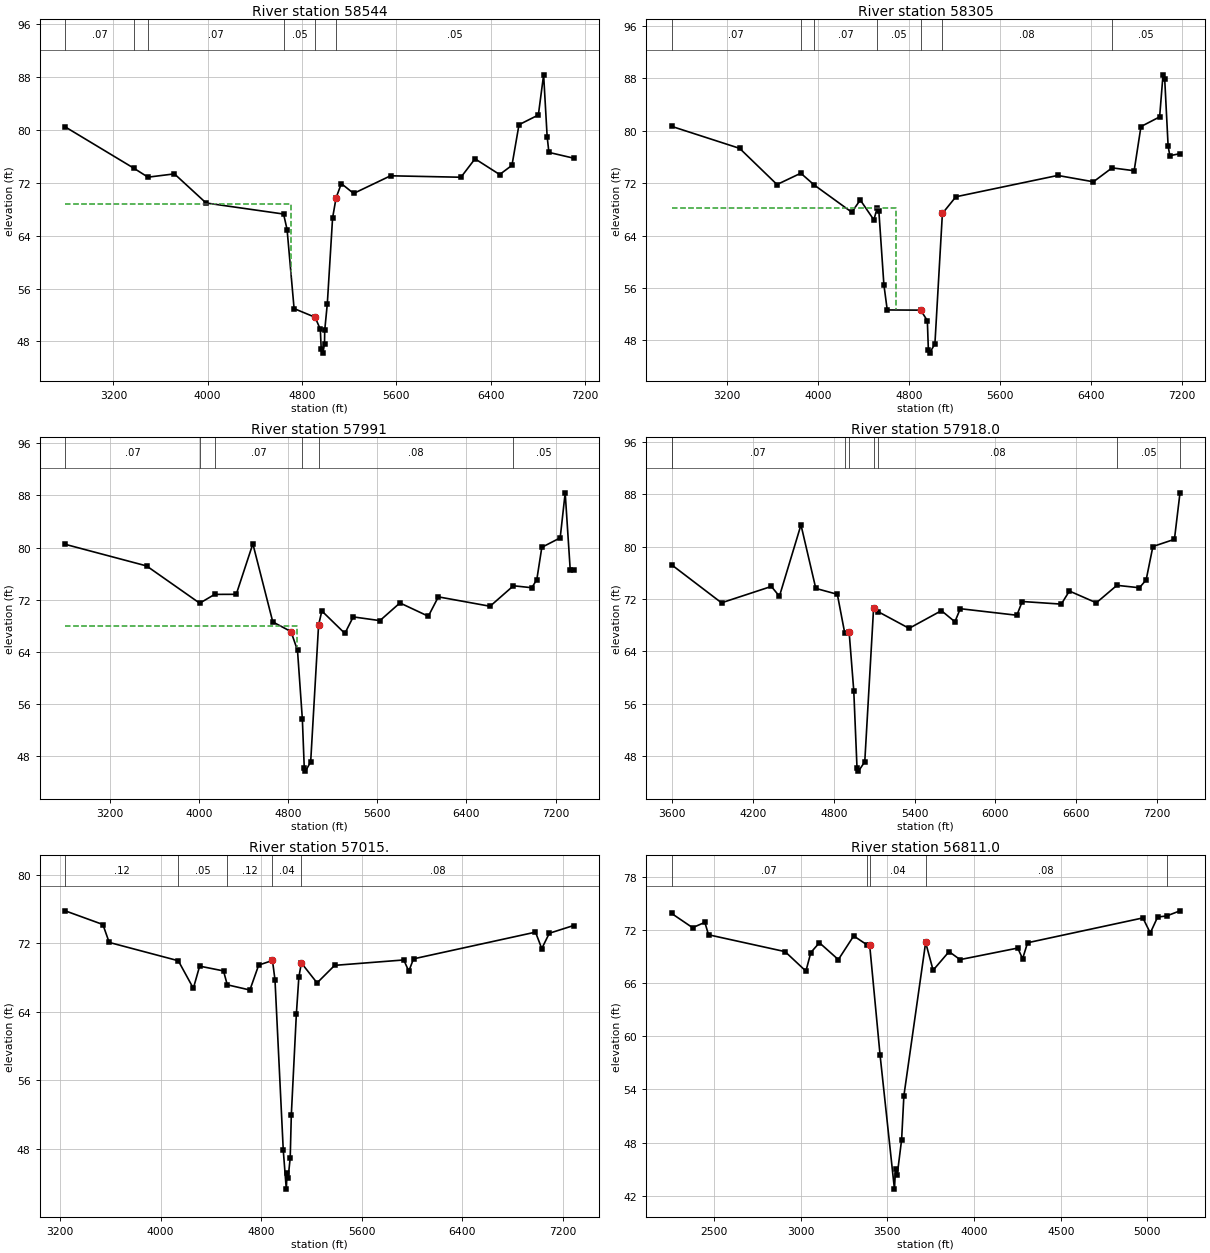
Type RM Length L Ch R = 1 ,58544   ,239,239.2,178.4
BEGIN DESCRIPTION:
-New section (PBS&J-September 2009)
-Ineffective area at station 4792.23 at elevation 61.85 (PBS&J-September 2009)
END DESCRIPTION:
XS GIS Cut Line= 4
3091481.9913791213874809.6223517 3089808.972783313874049.7398597
3089451.3810223613873672.99139733087510.1686058613873443.1109796
#Sta/Elev= 30
 2791.48   80.46  3374.1    74.2  3493.6   72.85  3717.7   73.35  3986.6   68.94
 4643.81   67.27  4673.5   64.92 4732.87   52.96 4910.96   51.65 4955.49   49.83
  4962.9   46.86  4977.3   46.22  4990.9   47.63  4992.7   49.67 5014.85   53.72
 5059.37   66.67 5089.04   69.72 5133.58   71.88 5237.95   70.39 5551.31   73.06
 6148.17   72.84 6267.56   75.63 6476.46   73.25 6580.92   74.64  6640.6   80.79
 6804.75   82.26  6849.5   88.34 6879.35      79 6894.27    76.6 7103.19   75.73
#Mann= 6 ,-1 , 0
 2791.48     .07       0  3374.1     .08       0  3493.6     .07       0
 4643.81     .05       0 4910.96     .04       0 5089.04     .05       0
#XS Ineff= 2 , 0
       0    4710   68.81               0
Permanent Ineff=
       F       F
Bank Sta=4910.96,5089.04
XS Rating Curve= 0 ,0
Exp/Cntr=0.6,0.4

Type RM Length L Ch R = 1 ,58305   ,331.1,313.9,365.6
BEGIN DESCRIPTION:
-New section (PBS&J-September 2009)
-Ineffective area at station 4860.31 at elevation 63.38 (PBS&J-September 2009)
END DESCRIPTION:
XS GIS Cut Line= 4
3091724.6429311913874745.7666801 3090096.323305513874030.5831582
 3089668.490305813873545.28005413087625.1088147413873443.1109796
#Sta/Elev= 30
 2714.26   80.68 3312.06   77.32 3640.85   71.79 3850.08   73.52 3969.65    71.7
 4298.44   67.56 4373.17   69.43 4492.72   66.39 4522.13   68.22 4536.83   67.69
 4580.94   56.48 4610.35   52.62 4904.42   52.59 4963.25   50.98  4972.2   46.52
    4983   46.02  5029.8   47.44 5095.58   67.37 5214.35   69.92 6110.38   73.18
    6424   72.21 6588.26   74.34  6782.4    73.9 6842.14   80.65 7006.42   82.13
 7036.27   88.56 7051.21    87.9 7081.08   77.69 7096.01    76.2 7185.62   76.51
#Mann= 7 ,-1 , 0
 2714.26     .07       0 3850.08     .08       0 3969.65     .07       0
 4522.13     .05       0 4904.42     .04       0 5095.58     .08       0
 6588.26     .05       0
#XS Ineff= 2 , 0
       0    4690   68.22               0
Permanent Ineff=
       F       F
Bank Sta=4904.42,5095.58
XS Rating Curve= 0 ,0
Exp/Cntr=0.6,0.4

Type RM Length L Ch R = 1 ,57991   ,68.8,73.2,124.7
BEGIN DESCRIPTION:
-New section (PBS&J-September 2009)
-Ineffective area at station 4927.21 at elevation 66.45 (PBS&J-September 2009)
END DESCRIPTION:
XS GIS Cut Line= 4
3091980.0656175813874305.1625461 3090109.094439813873564.4367556
3089840.9006191213873277.08623343087688.9644863213873430.3398453
#Sta/Elev= 30
 2798.49    80.5 3528.87   77.19 4005.85   71.48    4140   72.83 4333.77   72.84
 4482.83   80.58  4661.7   68.61 4825.31   67.13 4883.54   64.25 4927.21    53.7
  4944.2   46.25    4955   45.75  5001.8   47.17 5072.79   68.13 5101.91   70.29
 5308.69   66.85  5383.6   69.38 5623.31   68.81 5803.08   71.52 6057.78   69.48
 6147.67   72.45 6612.12   71.01 6821.86   74.15 6986.66   73.85 7031.61    75.1
 7076.55   80.04 7241.36   81.49 7286.29   88.39 7331.25   76.64 7361.21   76.59
#Mann= 6 ,-1 , 0
 2798.49     .07       0 4005.85     .08       0    4140     .07       0
 4927.21     .04       0 5072.79     .08       0 6821.86     .05       0
#XS Ineff= 2 , 0
       0    4875   68.04               0
Permanent Ineff=
       F       F
Bank Sta=4825.31,5072.79
XS Rating Curve= 0 ,0
Exp/Cntr=0.6,0.4

Type RM Length L Ch R = 1 ,57918.0 ,993.6,903,649.8
BEGIN DESCRIPTION:
Cross Section E100-00-00-X38
END DESCRIPTION:
XS GIS Cut Line= 5
      3091339.42      13873900.1      3090124.23     13873483.32
      3090044.12     13873387.31      3089862.19      13873197.3
      3087771.05     13873403.88
#Sta/Elev= 30
  3596.2    77.2  3966.2    71.4  4336.2    73.9  4396.2    72.4  4556.2    83.3
  4666.2    73.6  4826.2    72.7  4881.1   66.78  4913.9   66.89  4948.2   57.96
  4972.2   46.19    4983   45.69  5029.8   47.11  5095.3   70.56  5126.9   70.07
    5359    67.5    5599    70.2    5699    68.5    5739    70.5    6159    69.5
    6199    71.6    6489    71.2    6549    73.2    6749    71.4  6901.9   74.07
    7069    73.7    7119    74.9    7169      80    7329    81.1  7370.3    88.2
#Mann= 8 , 1 , 0
  3596.2     .99       0  3596.2     .07       0  4881.1     .04       0
  4913.9     .04       0  5095.3     .04       0  5126.9     .08       0
  6901.9     .05       0  7370.3     .99       0
Bank Sta=4913.9,5095.3
XS Rating Curve= 0 ,0
Exp/Cntr=0.3,0.1

Type RM Length L Ch R = 1 ,57015.  ,458.2,204,67.6
BEGIN DESCRIPTION:
Tidwell - U/S - XS 4
END DESCRIPTION:
XS GIS Cut Line= 6
      3091951.32     13872776.52      3090336.77     13872553.83
      3090074.77     13872514.53      3089382.98     13873021.64
      3088881.18     13873194.48       3088122.9     13873278.11
#Sta/Elev= 30
  3240.3    75.8  3540.3    74.2  3590.3   72.11  4140.3   69.97  4260.3   66.75
  4310.3   69.34  4500.3   68.78  4530.3   67.16  4710.3   66.55  4780.3   69.46
  4890.1      70  4910.1   67.73 4975.97   47.83 5000.12   43.29 5005.91   45.14
  5014.8   44.63 5031.28   46.95  5040.1   51.98  5080.1   63.72  5100.1   68.06
  5120.1   69.71  5245.1   67.38  5385.1   69.43  5935.1   70.06  5975.1   68.75
  6012.8   70.19  6983.6   73.31  7033.6   71.39  7093.6   73.18  7286.4   74.08
#Mann= 5 ,-1 , 0
  3240.3     .12       0  4140.3     .05       0  4530.3     .12       0
  4890.1     .04       0  5120.1     .08       0
Bank Sta=4890.1,5120.1
XS Rating Curve= 0 ,0
Exp/Cntr=0.5,0.3

Type RM Length L Ch R = 1 ,56811.0 ,149.6,190,191
BEGIN DESCRIPTION:
Upstream Section of Bridge/Culvert/Weir
END DESCRIPTION:
XS GIS Cut Line= 6
      3092054.35     13872368.03      3091151.11     13872172.88
      3090738.52     13872211.91      3090289.86     13872348.56
      3089428.26     13872936.74      3088168.18     13873193.21
#Sta/Elev= 30
2257.085   73.832377.646   72.232448.356   72.83 2469.57   71.432910.876   69.53
3031.084   67.333059.367   69.433108.866   70.533218.044   68.633306.501    71.3
3382.092   70.313398.497    70.33458.602   57.863541.474   42.753547.696   44.99
3557.242   44.333582.839   48.333595.849   53.273721.361   70.563764.354   67.43
3856.278   69.533919.918   68.634252.258   69.934280.542   68.734308.827   70.53
    4974   73.335016.427   71.635058.854   73.435110.542   73.555187.831   74.13
#Mann= 5 ,-1 , 0
2257.085     .07       03382.092     .04       03398.497     .04       0
3721.361     .08       05110.542     .05       0
#XS Ineff= 2 , 0
       03391.426   69.013728.432       0   68.82
Permanent Ineff=
       F       F
Bank Sta=3398.497,3721.361
XS Rating Curve= 0 ,0
Skew Angle= 45
Exp/Cntr=0.5,0.3

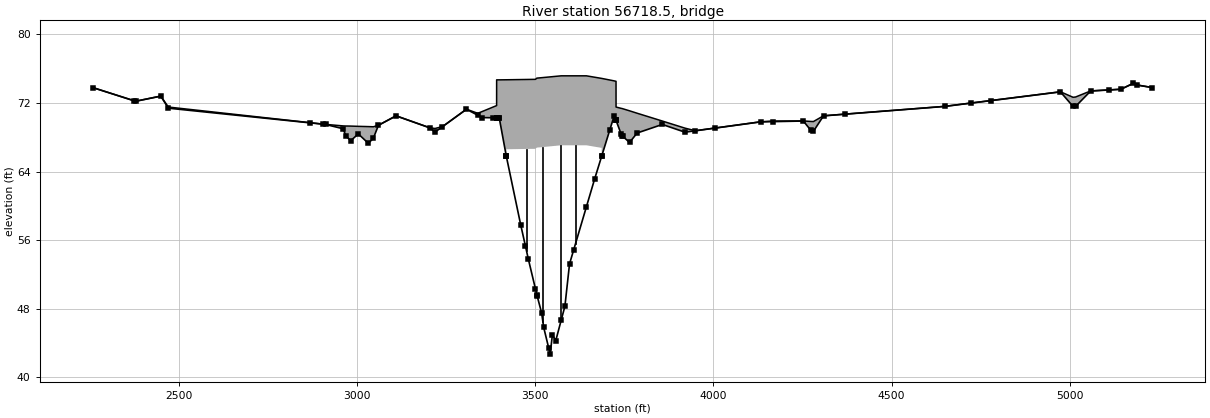
Type RM Length L Ch R = 3 ,56718.5 ,,,
BEGIN DESCRIPTION:
TIDWELL
Structure ID: E100-00-00-37
Bridge has 58 degree skew with the channel.
END DESCRIPTION:
Bridge Culvert--1,0,-1,-1, 0
Deck Dist Width WeirC Skew NumUp NumDn MinLoCord MaxHiCord MaxSubmerge Is_Ogee
10,165,2.6,45, 55, 54, , , 0.95, 0, ,,,
2257.4382377.6462448.356 2469.572910.8762960.3732967.4442981.587  3002.83031.084
3045.2253059.3673108.8663203.9013218.0443239.1873306.501 3338.183350.7683391.135
3391.2133398.4973418.4443418.5083500.1783504.0683572.5153643.2263685.9993686.077
3721.3613726.3813726.4593740.5953743.1413764.3543785.5663856.2783919.9183948.838
4132.0494168.0424252.2584273.4714280.5424308.8274648.7314974.0015009.3555016.427
5058.8545143.7085179.0625188.1855232.237
    73.8   72.21   72.81   71.53   69.51   69.33   69.32   69.31   69.28   69.25
   69.23   69.41   70.51   69.11   69.03   69.25   71.28    70.8   71.01    71.7
    74.7    74.7   74.71   74.71   74.76    74.9   75.17   75.17   74.87   74.87
   74.58   74.53   71.53   71.38   71.36   71.09   70.81    69.9   69.07   68.77
   69.81    69.9   69.91   69.85   69.84   70.51   71.61   73.31   72.67    72.7
   73.41   73.61   74.31   74.11    73.8
    73.8    72.2    72.8    71.4    69.5      69    68.2    67.6    68.4    67.3
    67.9    69.4    70.5    69.1    68.6   69.24   71.27   70.58    70.3   70.27
   70.27   70.27   65.79   66.61   66.66    66.8   67.07   67.07   66.77    65.8
   70.53   69.97   69.97    68.4    68.2    67.4    68.5    69.5    68.6   68.76
    69.8   69.83    69.9    68.8    68.7    70.5    71.6    73.3    71.6    71.6
    73.4    73.6    74.3    74.1    73.8
2257.4382377.6462448.356 2469.572910.8762960.3732967.4442981.587  3002.83031.084
3045.2253059.3673108.8663203.9013218.0443239.1873306.501 3338.183350.7683391.135
3391.2133398.4973418.4443418.5083500.1783504.0683572.5153643.2263685.9993686.077
3721.3613726.3813726.4593740.5953743.1413764.3543785.5663856.2783919.9183948.838
4132.0494252.2584273.4714280.5424308.8274648.7314974.0015009.3555016.4275058.854
5143.7085179.0625188.1855232.237
   73.96   72.36   72.96   71.56   69.66   69.33   69.32   69.31   69.28   69.25
   69.23   69.56   70.66   69.26   69.03    69.4   71.43    70.8   71.01    71.7
    74.7    74.7   74.71   74.71   74.76    74.9   75.17   75.17   74.87   74.87
   74.58   74.53   71.53   71.38   71.36   71.09   70.81    69.9   69.07   68.92
   69.96   70.06   69.85   69.84   70.66   71.76   73.46   72.67    72.7   73.56
   73.76   74.46   74.26   73.96
   73.96   72.36   72.96   71.56   69.66   69.16   68.36   67.76   68.56   67.46
   68.06   69.56   70.66   69.26   68.76    69.4   71.43   70.74   70.46   70.43
   70.43   70.43   65.95   66.77   66.82   66.96   67.23   67.23   66.93   65.96
   70.69   70.13   70.13   68.56   68.36   67.56   68.66   69.66   68.76   68.92
   69.96   70.06   68.96   68.86   70.66   71.76   73.46   71.76   71.76   73.56
   73.76   74.46   74.26   73.96
Pier Skew, UpSta & Num, DnSta & Num=  ,3474.865, 2 ,3474.865, 2 , 0 , 0 , 0 ,,
     2.5     2.5
   53.63   67.63
     2.5     2.5
   53.79   67.79
Pier Skew, UpSta & Num, DnSta & Num=  ,3521.038, 2 ,3521.038, 2 , 0 , 0 , 0 ,,
     2.5     2.5
   45.24   67.88
     2.5     2.5
    45.4   68.04
Pier Skew, UpSta & Num, DnSta & Num=  ,3571.738, 2 ,3571.738, 2 , 0 , 0 , 0 ,,
     2.5     2.5
   45.43   68.07
     2.5     2.5
   45.59   68.23
Pier Skew, UpSta & Num, DnSta & Num=  ,3612.113, 2 ,3612.113, 2 , 0 , 0 , 0 ,,
     2.5     2.5
    54.4   68.11
     2.5     2.5
   54.56   68.27
BR Coef= 1 , 1 , 0 ,1.25, 0 ,,,0.8,-1,2,0,
WSPro=,,,, 1 ,,,, 0 ,,,, 0 ,,,,-1 ,-1 ,-1 , 0 , 0 , 0 , 0 , 0
BR U #Sta/Elev= 84
2257.438    73.8 2371.85   72.282377.646    72.22448.356    72.8 2469.57    71.4
2866.824   69.692903.523   69.532910.876    69.52960.373      692967.444    68.2
2981.587    67.6  3002.8    68.43031.084    67.33045.225    67.93059.367    69.4
3108.866    70.53203.901    69.13218.044    68.63239.187   69.243306.501   71.27
 3338.18   70.583350.768    70.33382.092   70.283391.135   70.273391.213   70.27
3391.291   70.273397.438   70.273398.497   70.273418.226   65.833418.444   65.79
3418.508   65.773458.601   57.833471.895   55.35 3480.38   53.773500.178   50.33
3504.068   49.653504.774   49.533517.362   47.553523.372   45.833537.302   43.44
3541.474   42.723547.696   44.963557.242    44.33572.515   46.693582.839    48.3
3595.849   53.243607.376   54.863643.226    59.93666.277   63.143685.999   65.79
3686.077    65.8 3709.27   68.913721.361   70.533726.304   69.983726.381   69.97
3726.459   69.973740.595    68.43743.141    68.23744.695   68.143764.354    67.4
3785.566    68.53856.278    69.53919.918    68.63948.838   68.764005.407   69.08
4132.049    69.84168.042   69.834252.258    69.94273.471    68.84280.542    68.7
4308.827    70.54369.708    70.74648.731    71.64722.696   71.994779.263   72.28
4974.001    73.35009.355    71.65016.427    71.65058.854    73.45110.542   73.52
5143.708    73.65179.062    74.35188.185    74.15232.237    73.8
BR U #Mann= 7
2257.438     .992257.438     .073382.092     .043398.497     .043721.361     .08
5110.542     .055188.185     .99
BR U Banks=3398.497,3721.361
BR D #Sta/Elev= 84
2257.438   73.96 2371.85   72.442377.646   72.362448.356   72.96 2469.57   71.56
2866.824   69.852903.523   69.692910.876   69.662960.373   69.162967.444   68.36
2981.587   67.76  3002.8   68.563031.084   67.463045.225   68.063059.367   69.56
3108.866   70.663203.901   69.263218.044   68.763239.187    69.43306.501   71.43
 3338.18   70.743350.768   70.463382.092   70.443391.135   70.433391.213   70.43
3391.291   70.433397.438   70.433398.497   70.433418.226   65.993418.444   65.95
3418.508   65.933458.601   57.993471.895   55.51 3480.38   53.933500.178   50.49
3504.068   49.813504.774   49.693517.362   47.713523.372   45.993537.302    43.6
3541.474   42.883547.696   45.123557.242   44.463572.515   46.853582.839   48.46
3595.849    53.43607.376   55.023643.226   60.063666.277    63.33685.999   65.95
3686.077   65.96 3709.27   69.073721.361   70.693726.304   70.143726.381   70.13
3726.459   70.133740.595   68.563743.141   68.363744.695    68.33764.354   67.56
3785.566   68.663856.278   69.663919.918   68.763948.838   68.924005.407   69.24
4132.049   69.964168.042   69.994252.258   70.064273.471   68.964280.542   68.86
4308.827   70.664369.708   70.864648.731   71.764722.696   72.154779.263   72.44
4974.001   73.465009.355   71.765016.427   71.765058.854   73.565110.542   73.68
5143.708   73.765179.062   74.465188.185   74.265232.237   73.96
BR D #Mann= 7
2257.438     .992257.438     .073382.092     .043398.497     .043721.361     .08
5110.542     .055188.185     .99
BR D Banks=3398.497,3721.361
BC Design=,, 0 ,, 0 ,,,,,,
BC HTab HWMax=74.33
BC Use User HTab Curves=0
BC User HTab FreeFlow(D)= 0