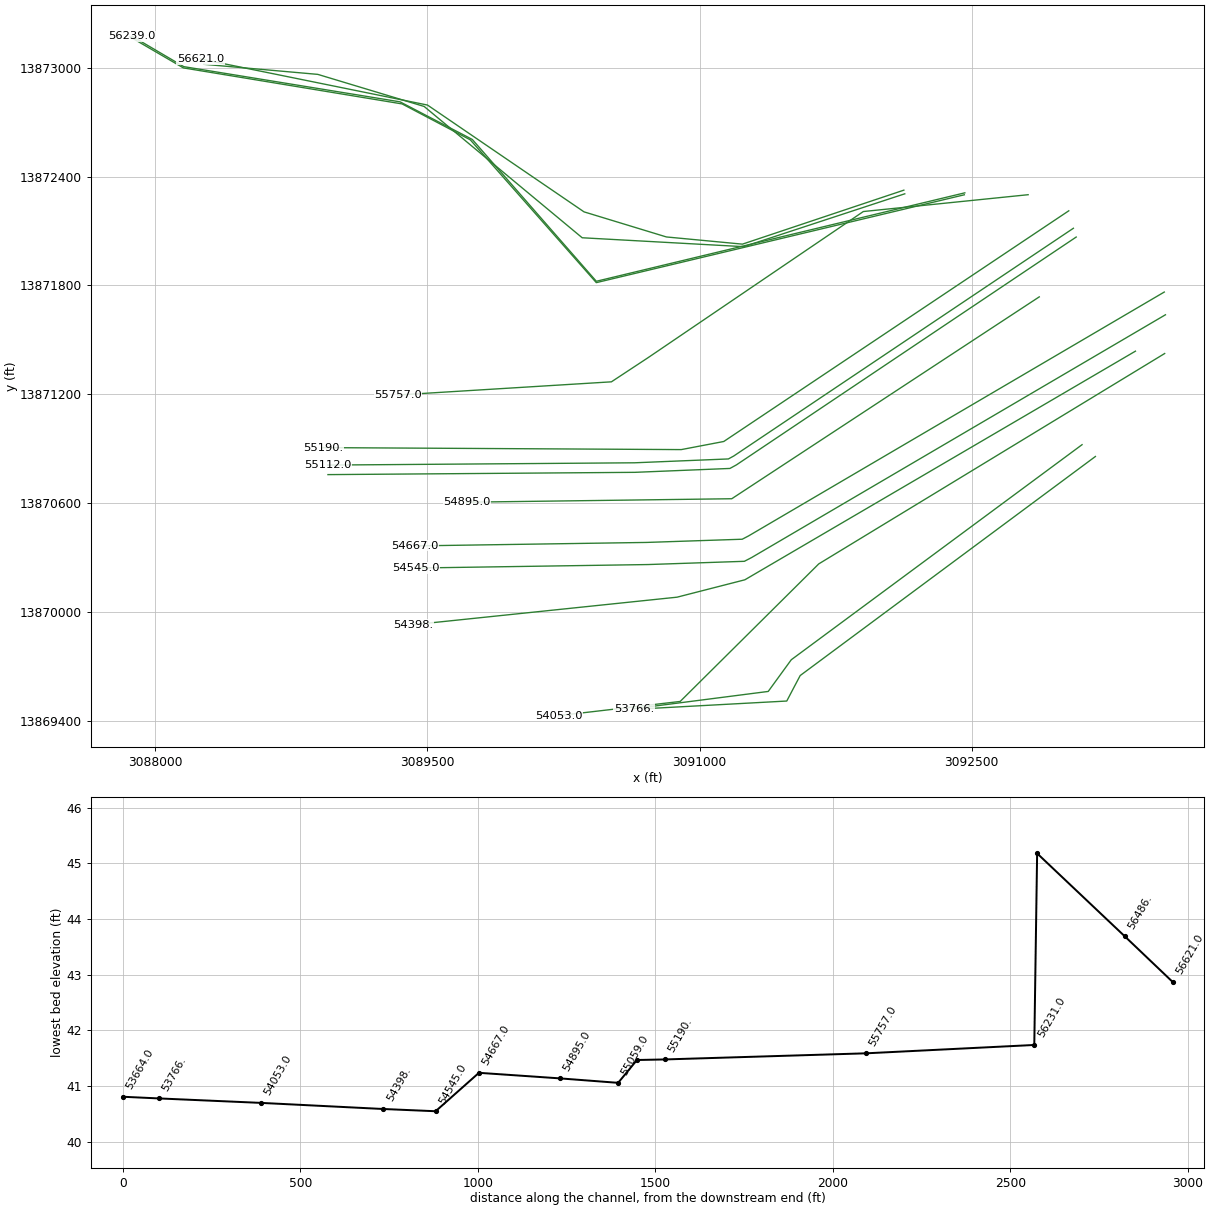
HEC-RAS study E100-00-00.prj: E100-00-00

--- E100-00-00.g02 (geometry) --- (continued)

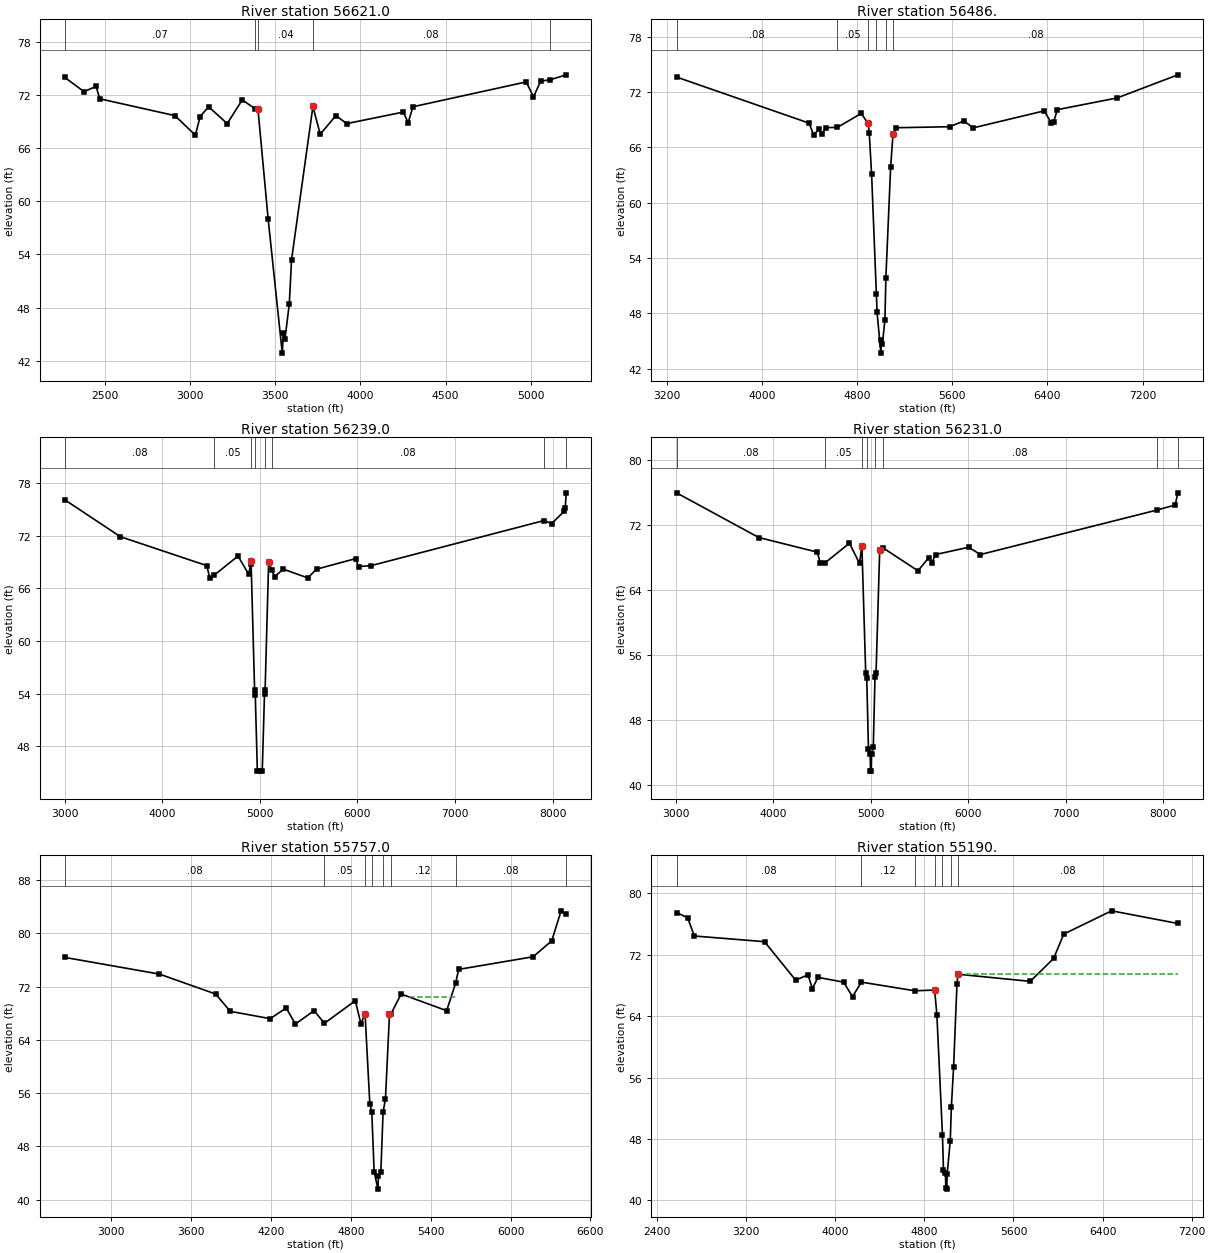
Type RM Length L Ch R = 1 ,56621.0 ,22,135,154.5
BEGIN DESCRIPTION:
Downstream Section of Bridge/Culvert/Weir
END DESCRIPTION:
XS GIS Cut Line= 6
      3092126.31     13872324.99      3091236.44     13872027.39
      3090817.48     13872067.02      3090363.26     13872205.36
      3089500.58     13872794.02      3088249.27     13873048.12
#Sta/Elev= 30
2264.934   73.952377.646   72.352448.356   72.95 2469.57   71.552910.876   69.65
3031.084   67.453059.367   69.553108.866   70.653218.044   68.753306.501   71.42
3382.092   70.433398.497   70.423458.602   57.983541.474   42.873547.696   45.11
3557.242   44.453582.839   48.453595.849   53.393721.361   70.683764.354   67.55
3856.278   69.653919.918   68.754252.258   70.054280.542   68.854308.827   70.65
    4974   73.455016.427   71.755058.854   73.555110.542   73.67 5208.76   74.25
#Mann= 5 ,-1 , 0
2264.934     .07       03382.092     .04       03398.497     .04       0
3721.361     .08       05110.542     .05       0
#XS Ineff= 2 , 0
       03393.779    67.53726.079       0    67.5
Permanent Ineff=
       F       F
Bank Sta=3398.497,3721.361
XS Rating Curve= 0 ,0
Skew Angle= 45
Exp/Cntr=0.5,0.3

Type RM Length L Ch R = 1 ,56486.  ,148.6,247,327.5
BEGIN DESCRIPTION:
Tidwell - D/S - XS 1
END DESCRIPTION:
XS GIS Cut Line= 6
      3092131.45     13872304.93      3091243.93     13872013.46
      3090353.14     13872062.58        3089482.     13872786.35
      3088895.78      13872963.2      3088266.99     13873018.87
#Sta/Elev= 30
  3282.4   73.64  4396.6   68.64  4436.6   67.32  4476.6      68  4506.6   67.42
  4536.6   68.15  4634.6   68.18  4834.6   69.69  4892.2   68.62  4902.2   67.62
  4922.2   63.07  4962.2   50.11 4968.17    48.1 5000.06   43.69 5005.19   45.14
 5013.05   44.71 5034.14    47.3  5042.2   51.89  5082.2   63.88  5102.2   67.45
  5127.2   68.14  5577.2   68.25  5697.2   68.87  5777.2   68.13  6372.8   69.97
  6432.8   68.66  6452.8   68.78  6482.8    70.1  6985.1   71.37  7496.3   73.88
#Mann= 6 ,-1 , 0
  3282.4     .08       0  4634.6     .05       0  4892.2     .04       0
  4962.2     .04       0  5042.2     .04       0  5102.2     .08       0
Bank Sta=4892.2,5102.2
XS Rating Curve= 0 ,0
Exp/Cntr=0.3,0.1

Type RM Length L Ch R = 1 ,56239.0 ,7,8,30.9
BEGIN DESCRIPTION:
Cross Section E100-00-00-X37B
END DESCRIPTION:
XS GIS Cut Line= 6
      3092462.49      13872310.3       3090431.1     13871822.69
      3089747.44     13872604.43      3089348.98     13872811.86
      3088157.04     13873005.83      3087870.75     13873174.23
#Sta/Elev= 30
  3002.6    76.1  3571.5    71.9    4457    68.6    4487    67.2  4531.3    67.5
    4777    69.7  4887.1    67.6  4905.5   68.82  4910.4   69.14  4946.7   54.45
  4953.5    53.9  4974.9   45.22  5000.4   45.18  5025.1    45.2  5048.1   54.02
  5054.2   54.42  5090.6   69.01  5123.4   68.08  5151.6   67.35  5241.6    68.2
  5491.6    67.2  5581.6    68.2  5981.6    69.4  6011.6    68.5  6140.1    68.6
  7911.9   73.74  7989.5    73.4  8119.5    74.8  8129.5    75.2  8139.6    76.9
#Mann= 8 ,-1 , 0
  3002.6     .08       0  4531.3     .05       0  4905.5     .04       0
  4953.5    .015       0  5048.1     .04       0  5123.4     .08       0
  7911.9     .05       0  8139.6     .99       0
Bank Sta=4910.4,5090.6
XS Rating Curve= 0 ,0
Exp/Cntr=0.3,0.1

Type RM Length L Ch R = 1 ,56231.0 ,314.9,474,678.2
BEGIN DESCRIPTION:
Cross Section E100-00-00-X37A
END DESCRIPTION:
XS GIS Cut Line= 6
      3092459.59     13872299.45       3090431.1     13871815.19
      3089736.43     13872602.36      3089360.49     13872800.35
      3088154.64     13872998.93      3087861.11     13873169.88
#Sta/Elev= 30
  3006.7      76  3850.4    70.5  4450.4    68.7  4480.4    67.4  4531.9    67.4
  4780.4    69.8  4883.5   67.31  4905.3   69.27  4907.6   69.48  4946.9   53.85
  4957.7   53.21  4975.1   44.51  4992.8   43.89    4996   41.74  5004.2   41.79
  5006.9   43.84  5024.5   44.66    5042   53.35  5052.9   53.81  5090.6   69.01
  5121.3   69.25  5482.7    66.4  5592.7      68  5622.7    67.3  5662.7    68.4
  6002.7    69.3  6122.7    68.4  7930.3   73.87    8120    74.5    8148      76
#Mann= 8 ,-1 , 0
  3006.7     .08       0  4531.9     .05       0  4905.3     .04       0
  4957.7    .015       0    5042     .04       0  5121.3     .08       0
  7930.3     .05       0    8148     .99       0
Bank Sta=4907.6,5090.6
XS Rating Curve= 0 ,0
Exp/Cntr=0.3,0.1

Type RM Length L Ch R = 1 ,55757.0 ,632,567,467
BEGIN DESCRIPTION:
Cross Section E100-00-00-X37
END DESCRIPTION:
XS GIS Cut Line= 5
      3092811.37     13872299.91      3091902.95     13872207.18
      3090716.35     13871401.57      3090514.23     13871268.43
      3089337.78     13871195.95
#Sta/Elev= 30
  2650.5    76.4  3360.5    73.9  3783.6    70.9  3893.6    68.3  4193.6    67.2
  4313.6    68.8  4383.6    66.4  4523.6    68.4    4601    66.5  4833.6    69.9
  4875.1   66.45  4906.7    67.9  4942.3   54.44  4957.1   53.22  4974.8   44.22
  5003.6   41.59  5007.2   43.55  5025.1    44.1  5042.2   53.19  5059.9   55.14
  5090.2   67.85  5101.4   67.92  5177.9    70.9  5519.9    68.4  5587.4   72.53
  5609.9    74.6  6169.9    76.5  6309.9    78.9  6379.9    83.4  6418.6    82.9
#Mann= 8 ,-1 , 0
  2650.5     .08       0    4601     .05       0  4906.7     .04       0
  4957.1    .015       0  5042.2     .04       0  5101.4     .12       0
  5587.4     .08       0  6418.6     .99       0
#XS Ineff= 1 ,-1
 5239.86 5589.43    70.5
Permanent Ineff=
       F
Bank Sta=4906.7,5090.2
XS Rating Curve= 0 ,0
Exp/Cntr=0.3,0.1

Type RM Length L Ch R = 1 ,55190.  ,99.6,78,69.6
BEGIN DESCRIPTION:
Creekmont - U/S - XS 4
END DESCRIPTION:
XS GIS Cut Line= 4
      3093035.39     13872211.17      3091133.65     13870939.57
      3090899.31     13870894.86       3088924.6     13870905.79
#Sta/Elev= 30
  2574.9   77.52  2674.9   76.84  2734.9   74.46  3364.9   73.72  3644.9    68.7
  3754.9   69.41  3794.9   67.61  3844.9   69.07  4074.9   68.45  4154.9   66.56
  4234.9   68.45  4714.9   67.32  4892.6   67.42  4912.6   64.14  4962.6   48.51
 4971.73   43.95 4989.42   43.57 4992.82   41.59 5001.22   41.48 5004.79   43.47
  5032.6   47.81  5042.6   52.24  5062.6   57.44  5092.6   68.19  5101.2   69.48
  5751.2   68.55  5961.2   71.55  6051.2   74.71  6481.2   77.74  7075.9   76.09
#Mann= 7 ,-1 , 0
  2574.9     .08       0  4234.9     .12       0  4714.9     .05       0
  4892.6     .04       0  4962.6    .015       0  5042.6     .04       0
  5101.2     .08       0
#XS Ineff= 2 , 0
                         5171.81           69.48
Permanent Ineff=
       F       F
Bank Sta=4892.6,5101.2
XS Rating Curve= 0 ,0
Exp/Cntr=0.5,0.3

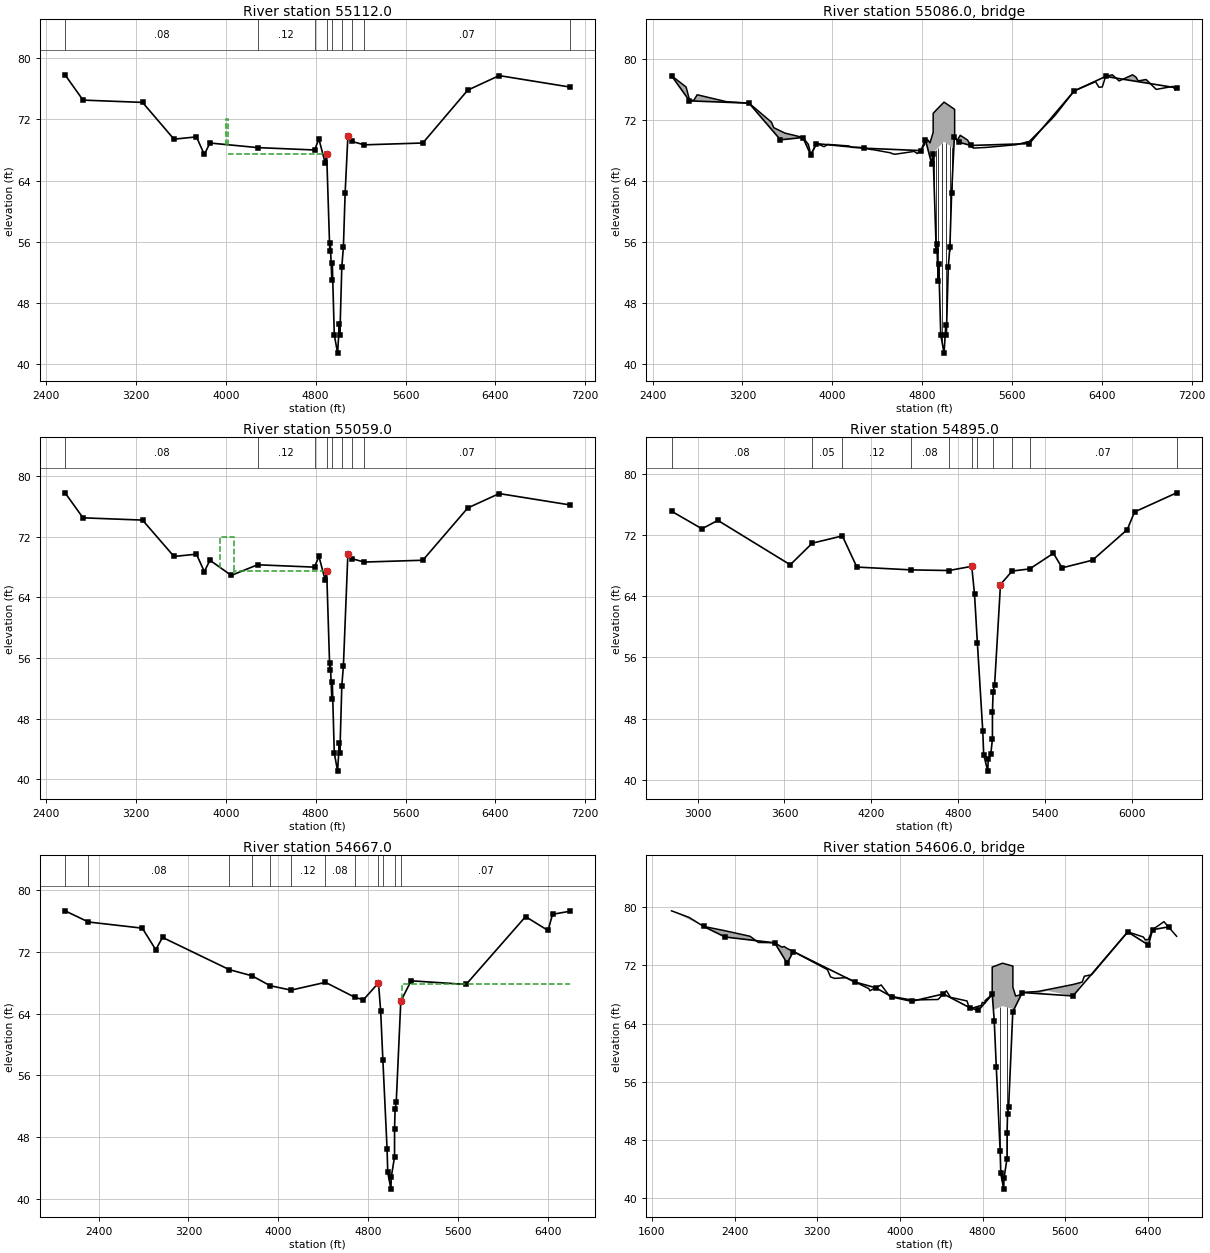
Type RM Length L Ch R = 1 ,55112.0 ,54.3,53,52
BEGIN DESCRIPTION:
Upstream Section of Bridge/Culvert/Weir
END DESCRIPTION:
XS GIS Cut Line= 5
      3093060.86     13872114.95      3091188.59     13870859.49
      3091159.11     13870843.35      3090641.88     13870822.14
      3088950.07     13870809.57
#Sta/Elev= 30
  2568.5    77.8  2728.5    74.5  3258.5    74.2  3538.5    69.4  3738.5    69.7
  3808.5    67.4  3858.5    68.9  4282.8    68.3  4789.9   67.99  4828.8   69.42
  4884.6   66.29  4897.8    67.5  4925.6   54.85  4930.2    55.8  4944.1   50.96
    4948   53.19  4965.7   43.87  4995.2   41.47  5010.9   45.21  5015.5   43.84
  5032.7   52.71  5046.9   55.36  5062.5   62.43  5086.9   69.79  5124.4    69.1
  5231.8   68.66    5754    68.9    6154    75.8    6434    77.7  7065.9    76.2
#Mann= 9 ,-1 , 0
  2568.5     .08       0  4282.8     .12       0  4789.9     .05       0
  4897.8     .04       0    4948    .015       0  5032.7     .04       0
  5124.4     .12       0  5231.8     .07       0  7065.9     .99       0
#XS Ineff= 3 ,-1
    4003    4022      72 5093.57    6000   68.32    4022 4891.13   67.47
Permanent Ineff=
       F       F       F
Bank Sta=4897.8,5086.9
XS Rating Curve= 0 ,0
Exp/Cntr=0.5,0.3

Type RM Length L Ch R = 3 ,55086.0 ,,,
BEGIN DESCRIPTION:
CREEKMONT DR
Structure ID: E100-00-00-36
END DESCRIPTION:
Bridge Culvert--1,0,-1,-1, 0
Deck Dist Width WeirC Skew NumUp NumDn MinLoCord MaxHiCord MaxSubmerge Is_Ogee
10,32,2.6,0, 133, 133, , , 0.95, 0, ,,,
  2568.5  2697.2  2698.5  2728.5  2737.2  2757.2  2768.5  2797.2  2978.5  3058.5
  3258.5  3287.2  3377.2  3397.2  3447.2  3458.5  3477.2  3478.5  3538.5  3578.5
  3738.5  3787.2  3807.2  3808.5  3827.2  3858.5  3867.2  3927.2  3957.2  3958.5
  3998.5  4048.5  4078.5  4147.2  4177.2  4248.5  4282.8  4337.2  4367.2  4517.2
  4537.2  4558.5  4718.5  4727.2  4738.5  4757.2  4789.9  4799.7  4822.7  4828.8
  4843.9  4849.7  4869.7  4875.8  4884.6  4897.8 4897.89    4898 4898.11 4898.21
  4898.3  4907.5  4925.6  4930.2  4944.1    4948  4965.7  4978.6  4983.4  4984.6
  4986.8  4993.7  4995.2  4997.6  4998.8  5010.9  5015.5  5032.7  5044.3  5046.9
  5062.5 5082.39  5082.5  5086.9    5089  5089.1 5089.19  5089.3 5089.41  5089.7
  5099.7  5109.7  5119.7  5124.4  5139.7    5142  5204.1  5231.8  5246.3  5259.7
    5374  5588.3  5608.3  5638.3    5754  5948.3    5984  6078.3    6154  6208.3
  6228.3  6278.3    6344    6374    6404    6434  6488.3    6494  6518.3    6554
  6578.3  6618.3    6674    6704    6724  6748.3  6778.3  6781.7    6794    6884
    7034    7054  7065.9
    77.8   76.33   76.31   74.63   74.53   74.58   74.61    75.3   74.67   74.39
   74.21   73.85   72.73   72.48   71.85   71.71      71   70.99   70.56   70.28
   69.71    68.8    67.5   67.47   67.97   68.91   68.86    68.5    68.8    68.8
   68.76    68.7   68.67    68.6   68.41   68.41   68.31   68.15    68.1    67.7
   67.57   67.51   67.86    67.9   67.79    67.6   68.14    68.3   68.81   69.43
   69.27    69.4      69    69.3   69.72   70.37   70.37   72.87   72.87   72.87
   72.87   73.02    73.3   73.37   73.58   73.64   73.92   74.12   74.19   74.21
   74.24   74.35   74.34   74.31    74.3   74.18   74.13   73.96   73.85   73.82
   73.66   73.47   73.46   73.42    73.4   73.39   73.39   73.39   70.89   69.75
   69.57   69.38    69.5   69.62      70   69.97   69.37   68.67    68.4   68.32
   68.41   68.69   68.72   68.76   69.19   72.04   72.61   74.39   75.81   76.15
   76.28    76.6   77.01   76.29   76.32   77.71   77.89   77.91   77.59   77.11
   77.27   77.54   77.91   77.61   77.11   77.18   77.27   77.27    77.3      76
    76.4    75.9    76.2
                                                                                
                                                                                
                                                                                
                                                                                
                                                                                
                                                                           67.28
   67.67   67.82    68.1   68.17   68.38   68.44   68.72   68.92   68.99   69.01
   69.04   69.15   69.14   69.11    69.1   68.98   68.93   68.76   68.65   68.62
   68.46   68.43
                                                                                
                                                                                
                                                                                
                                                                                
                        
  2568.5  2697.2  2698.5  2728.5  2737.2  2757.2  2768.5  2797.2  2978.5  3058.5
  3258.5  3287.2  3377.2  3397.2  3447.2  3458.5  3477.2  3478.5  3538.5  3578.5
  3738.5  3787.2  3807.2  3808.5  3827.2  3858.5  3867.2  3927.2  3957.2  3958.5
  3998.5  4048.5  4078.5  4147.2  4177.2  4248.5  4282.8  4337.2  4367.2  4517.2
  4537.2  4558.5  4718.5  4727.2  4738.5  4757.2  4789.9  4799.7  4822.7  4828.8
  4843.9  4849.7  4869.7  4875.8  4884.6  4897.8 4897.89    4898 4898.11 4898.21
  4898.3  4907.5  4925.6  4930.2  4944.1    4948  4965.7  4978.6  4983.4  4984.6
  4986.8  4993.7  4995.2  4997.6  4998.8  5010.9  5015.5  5032.7  5044.3  5046.9
  5062.5 5082.39  5082.5  5086.9    5089  5089.1 5089.19  5089.3 5089.41  5089.7
  5099.7  5109.7  5119.7  5124.4  5139.7    5142  5204.1  5231.8  5246.3  5259.7
    5374  5588.3  5608.3  5638.3    5754  5948.3    5984  6078.3    6154  6208.3
  6228.3  6278.3    6344    6374    6404    6434  6488.3    6494  6518.3    6554
  6578.3  6618.3    6674    6704    6724  6748.3  6778.3  6781.7    6794    6884
    7034    7054  7065.9
    77.8   76.33   76.31   74.63   74.53   74.58   74.61    75.3   74.67   74.39
   74.21   73.85   72.73   72.48   71.85   71.71      71   70.99   70.56   70.28
   69.71    68.8    67.5   67.47   67.97   68.91   68.86    68.5    68.8    68.8
   68.76    68.7   68.67    68.6   68.41   68.41   68.31   68.15    68.1    67.7
   67.57   67.51   67.86    67.9   67.79    67.6   68.14    68.3   68.81   69.43
   69.27    69.4      69    69.3   69.72   70.37   70.37   72.87   72.87   72.87
   72.87   73.02    73.3   73.37   73.58   73.64   73.92   74.12   74.19   74.21
   74.24   74.35   74.34   74.31    74.3   74.18   74.13   73.96   73.85   73.82
   73.66   73.47   73.46   73.42    73.4   73.39   73.39   73.39   70.89   69.75
   69.57   69.38    69.5   69.62      70   69.97   69.37   68.67    68.4   68.32
   68.41   68.69   68.72   68.76   69.19   72.04   72.61   74.39   75.81   76.15
   76.28    76.6   77.01   76.29   76.32   77.71   77.89   77.91   77.59   77.11
   77.27   77.54   77.91   77.61   77.11   77.18   77.27   77.27    77.3      76
    76.4    75.9    76.2
                                                                                
                                                                                
                                                                                
                                                                                
                                                                                
                                                                           67.28
   67.67   67.82    68.1   68.17   68.38   68.44   68.72   68.92   68.99   69.01
   69.04   69.15   69.14   69.11    69.1   68.98   68.93   68.76   68.65   68.62
   68.46   68.43
                                                                                
                                                                                
                                                                                
                                                                                
                        
Pier Skew, UpSta & Num, DnSta & Num=  ,4907.5, 2 ,4907.5, 2 , 0 , 0 , 0 ,,
     1.2     1.2
   61.01   68.83
     1.2     1.2
    60.6   68.42
Pier Skew, UpSta & Num, DnSta & Num=  ,4925.6, 2 ,4925.6, 2 , 0 , 0 , 0 ,,
     1.2     1.2
   53.97   69.11
     1.2     1.2
   53.56    68.7
Pier Skew, UpSta & Num, DnSta & Num=  ,4944.1, 2 ,4944.1, 2 , 0 , 0 , 0 ,,
     1.2     1.2
   50.17   69.39
     1.2     1.2
   49.76   68.98
Pier Skew, UpSta & Num, DnSta & Num=  ,4978.6, 2 ,4978.6, 2 , 0 , 0 , 0 ,,
     1.2     1.2
   41.87   69.93
     1.2     1.2
   41.46   69.52
Pier Skew, UpSta & Num, DnSta & Num=  ,5010.9, 2 ,5010.9, 2 , 0 , 0 , 0 ,,
     1.2     1.2
   44.03   69.99
     1.2     1.2
   43.62   69.58
Pier Skew, UpSta & Num, DnSta & Num=  ,5044.3, 2 ,5044.3, 2 , 0 , 0 , 0 ,,
     1.2     1.2
   54.36   69.66
     1.2     1.2
   53.95   69.25
Pier Skew, UpSta & Num, DnSta & Num=  ,5062.5, 2 ,5062.5, 2 , 0 , 0 , 0 ,,
     1.2     1.2
   61.16   69.47
     1.2     1.2
   60.75   69.06
BR Coef= 1 , 1 , 0 ,1.25, 0 ,,,0.8,-1,2,0,
WSPro=,,,, 1 ,,,, 0 ,,,, 0 ,,,,-1 ,-1 ,-1 , 0 , 0 , 0 , 0 , 0
BC Design=,, 0 ,, 0 ,,,,,,
BC HTab HWMax=77.9
BC Use User HTab Curves=0
BC User HTab FreeFlow(D)= 0

Type RM Length L Ch R = 1 ,55059.0 ,165,164,160.4
BEGIN DESCRIPTION:
Downstream Section of Bridge/Culvert/Weir
END DESCRIPTION:
XS GIS Cut Line= 5
      3093076.34     13872066.57      3091203.15     13870810.49
      3091167.55     13870790.99      3090644.05     13870769.53
      3088951.82     13870756.96
#Sta/Elev= 30
  2568.5    77.8  2728.5    74.5  3258.5    74.2  3538.5    69.4  3738.5    69.7
  3808.5    67.4  3858.5    68.9  4048.5    66.9  4282.8    68.3  4789.9   67.99
  4828.8   69.42  4884.6   66.29  4897.8    67.5  4925.6   54.44  4930.2   55.39
  4944.1   50.55    4948   52.78  4965.7   43.46  4995.2   41.06  5010.9    44.8
  5015.5   43.43  5032.7    52.3  5046.9   54.95  5086.9   69.79  5124.4    69.1
  5231.8   68.66    5754    68.9    6154    75.8    6434    77.7  7065.9    76.2
#Mann= 8 ,-1 , 0
  2568.5     .08       0  4282.8     .12       0  4789.9     .05       0
  4897.8     .04       0    4948    .015       0  5032.7     .04       0
  5124.4     .12       0  5231.8     .07       0
#XS Ineff= 3 ,-1
    3950    4075      72 5093.57    6000   68.32    4075 4891.13   67.47
Permanent Ineff=
       F       F       F
Bank Sta=4897.8,5086.9
XS Rating Curve= 0 ,0
Exp/Cntr=0.5,0.3

Type RM Length L Ch R = 1 ,54895.0 ,257.3,228,227
BEGIN DESCRIPTION:
Cross Section E100-00-00-X36.7
-Modified right bank location (PBS&J October 2009)
END DESCRIPTION:
XS GIS Cut Line= 3
       3092872.7     13871736.78      3091177.66     13870623.99
      3089716.92     13870604.94
#Sta/Elev= 30
  2819.9    75.1  3029.9    72.8  3139.9    73.9  3639.9    68.1  3791.6   70.92
  3999.8   71.87  4099.9    67.8  4477.3   67.43  4736.7   67.35  4893.3    67.9
  4912.5   64.27  4932.2   57.93  4969.5    46.4  4975.9    43.3  5004.1   41.14
  5007.1   42.69    5025   43.35  5036.3   45.35  5036.4   48.89  5041.1   51.54
  5051.4   52.43  5091.9   65.52  5172.3   67.28  5293.6   67.56  5457.6    69.6
  5517.6    67.7  5727.6    68.7  5967.6    72.7  6017.6      75  6308.4    77.5
#Mann= 11 ,-1 , 0
  2819.9     .08       0  3791.6     .05       0  3999.8     .12       0
  4477.3     .08       0  4736.7     .05       0  4893.3     .04       0
  4932.2    .015       0  5041.1     .04       0  5172.3     .08       0
  5293.6     .07       0  6308.4     .99       0
Bank Sta=4893.3,5091.9
XS Rating Curve= 0 ,0
Exp/Cntr=0.5,0.3

Type RM Length L Ch R = 1 ,54667.0 ,114.2,122,123
BEGIN DESCRIPTION:
Upstream Section of Bridge/Culvert/Weir
END DESCRIPTION:
XS GIS Cut Line= 6
 3093561.781809313871763.3404925      3093382.03     13871657.89
      3091269.27     13870418.45      3091235.24     13870400.81
      3090708.58     13870383.14      3089431.56     13870363.97
#Sta/Elev= 30
  2100.6   77.35    2309    75.9    2789    75.1    2909    72.3    2969    73.9
  3563.7   69.72  3766.3   68.92  3926.7   67.64  4113.9   67.06  4420.6   68.07
  4680.2   66.15  4758.5    65.8  4893.3      68  4912.5   64.37  4932.2   58.03
  4969.5    46.5  4975.8    43.4  5004.1   41.24  5007.1   42.79  5036.3   45.45
  5036.4   48.99    5041   51.58  5051.4   52.53  5091.9   65.62  5183.6   68.27
  5673.8    67.8  6203.8    76.6  6403.8    74.8  6443.8    76.9  6600.9    77.3
#Mann= 12 ,-1 , 0
  2100.6     .99       0    2309     .08       0  3563.7     .05       0
  3766.3     .12       0  3926.7     .08       0  4113.9     .12       0
  4420.6     .08       0  4680.2     .05       0  4893.3     .04       0
  4932.2    .015       0    5041     .04       0  5091.9     .07       0
#XS Ineff= 2 , 0
       0  4883.3    66.1  5101.9       0    67.8
Permanent Ineff=
       F       F
Bank Sta=4893.3,5091.9
XS Rating Curve= 0 ,0
Exp/Cntr=0.5,0.3

Type RM Length L Ch R = 3 ,54606.0 ,,,
BEGIN DESCRIPTION:
PINEMONT
Structure ID: E100-00-00-35
END DESCRIPTION:
Bridge Culvert--1,0,-1,-1, 0
Deck Dist Width WeirC Skew NumUp NumDn MinLoCord MaxHiCord MaxSubmerge Is_Ogee
10,102,2.6,0, 60, 60, , , 0.95, 0, ,,,
  1790.6  1960.6  2100.6    2309    2379  2550.6  2630.6    2789    2859  2880.6
    2909    2969    3299    3329    3369    3479    3699    3709    3819    3899
    3919    3949  4113.9    4369    4449    4489    4649    4669  4694.4  4758.5
  4788.5  4796.8  4822.1  4823.6  4888.9  4892.5 4892.59  4892.7 4904.41  4992.8
 5090.99  5091.1  5092.8 5092.91  5118.9  5172.3  5183.6  5336.7  5423.8  5673.8
  5763.8  5783.8  5853.8  6203.8  6353.8  6373.8  6403.8  6443.8  6553.8  6676.6
    79.5    78.6   77.36   76.76   76.54      76   75.15   75.11    74.5    74.6
   74.32   73.91   71.41   70.41   70.21   70.31   68.81   68.51   69.31   67.79
   67.91   67.66   67.24   67.31   68.51   67.61   67.11   66.21    66.1   66.38
   66.51   66.91   66.81   67.16   67.96    68.4   68.87   71.77   71.83    72.3
   71.91   71.91    71.9      69    67.8   67.95   68.28   68.42   68.66   69.37
   69.71   70.51   70.71   76.61   75.91   75.52   75.57   76.91   78.01      76
    79.5   78.32   77.35    75.9    75.2   75.16   75.14    75.1    72.7   72.53
    72.3    73.9    71.4    70.4    70.2    70.3    68.8    68.5    69.3    67.7
    67.9    66.9   67.06    67.3    68.5    67.6    67.1    66.2   66.09    65.8
    66.3    66.9    66.8   67.15   67.95   67.99   67.99   67.99    65.9    66.4
   66.01   65.34   65.64   65.64   66.21   67.38   68.27   67.42    68.5    67.8
    69.7    70.5    70.7    76.6    75.9    74.9    74.8    76.9      78      76
  1790.6  1960.6  2100.6    2309    2379  2550.6  2630.6    2789    2859  2880.6
    2909    2969    3299    3329    3369    3479    3699    3709    3819    3899
    3919    3949  4113.9    4369    4449    4489    4649    4669  4694.4  4758.5
  4788.5  4796.8  4822.1  4823.6  4888.9  4892.5 4892.59  4892.7 4904.41  4992.8
 5090.99  5091.1  5092.8 5092.91  5118.9  5172.3  5183.6  5336.7  5423.8  5673.8
  5763.8  5783.8  5853.8  6203.8  6353.8  6373.8  6403.8  6443.8  6553.8  6676.6
    79.5    78.6   77.36   76.76   76.54      76   75.15   75.11    74.5    74.6
   74.32   73.91   71.41   70.41   70.21   70.31   68.81   68.51   69.31   67.79
   67.91   67.66   67.24   67.31   68.51   67.61   67.11   66.21    66.1   66.38
   66.51   66.91   66.81   67.16   67.96    68.4   68.87   71.77   71.83    72.3
   71.91   71.91    71.9      69    67.8   67.95   68.28   68.42   68.66   69.37
   69.71   70.51   70.71   76.61   75.91   75.52   75.57   76.91   78.01      76
   78.81   77.63   76.66   75.21   74.51   74.47   74.45   74.41   72.01   71.84
   71.61   73.21   70.71   69.71   69.51   69.61   68.11   67.81   68.61   67.01
   67.21   66.21   66.37   66.61   67.81   66.91   66.41   65.51    65.4   65.11
   65.61   66.21   66.11   66.46   67.26    67.3    67.3    67.3   65.21   65.71
   65.32   64.65   64.95   64.95   65.52   66.69   67.58   66.73   67.81   67.11
   69.01   69.81   70.01   75.91   75.21   74.21   74.11   76.21   77.31   75.31
Pier Skew, UpSta & Num, DnSta & Num=  ,4969.4, 2 ,4969.4, 2 , 0 , 0 , 0 ,,
     1.5     1.5
   45.18   67.28
     1.5     1.5
   44.49   66.59
Pier Skew, UpSta & Num, DnSta & Num=  ,5036.3, 2 ,5036.3, 2 , 0 , 0 , 0 ,,
     1.5     1.5
   44.32   67.23
     1.5     1.5
   43.63   66.54
Abutment Skew #Up #Dn= , 2 , 2
  4904.3  4975.9
   65.93    43.4
  4904.3  4975.9
   65.24   42.71
Abutment Skew #Up #Dn= , 2 , 2
  5041.1 5091.19
   51.64   66.01
  5041.1 5091.19
   50.95   65.32
BR Coef= 1 , 1 , 0 ,1.25, 0 ,,,0.8,-1,2,0,
WSPro=,,,, 1 ,,,, 0 ,,,, 0 ,,,,-1 ,-1 ,-1 , 0 , 0 , 0 , 0 , 0
BR D #Sta/Elev= 114
  1790.6    79.5  1960.6   78.32  2010.6   77.97  2050.6   77.69  2100.6   77.35
  2170.6   76.86    2309    75.9    2379    75.2  2550.6   75.16  2630.6   75.14
    2789    75.1    2859    72.7  2880.6   72.53    2909    72.3    2969    73.9
    3299    71.4    3329    70.4    3369    70.2  3380.6   70.21  3440.6   70.27
  3470.6   70.29    3479    70.3  3563.7   69.72  3570.6   69.68  3630.6   69.27
    3699    68.8    3709    68.5  3720.6   68.58  3740.6   68.73  3766.3   68.92
  3780.6   69.02    3819    69.3    3899    67.7    3919    67.9  3926.7   67.64
    3949    66.9  4113.9   67.06  4320.6   67.25  4360.6   67.29    4369    67.3
  4410.6   67.92  4420.6   68.07    4449    68.5  4480.6   67.79    4489    67.6
  4620.6   67.19  4640.6   67.13    4649    67.1    4669    66.2  4680.2   66.15
  4694.4   66.09  4758.5    65.8  4788.5    66.3  4796.8    66.9  4808.9   66.85
  4822.1    66.8  4823.6   67.15  4878.9   67.82  4888.9   67.95  4892.5   67.99
 4892.59   67.99  4892.7   67.99 4892.81   67.99  4893.3   67.31 4904.41   65.21
  4904.5   65.19  4912.5   63.68  4932.2   57.34  4969.3   45.65  4969.4   45.78
  4969.5   45.81  4975.8   42.71  4975.9   42.71  4992.8   42.07    4993   42.06
  4993.8   41.67  4995.8   40.63  5004.1   40.55  5006.3   41.67  5007.1    42.1
    5025   42.76  5036.3   44.76  5036.4    48.3    5041   50.89  5041.1   50.95
  5051.4   51.84  5065.5    55.8 5090.99   64.62  5091.1   64.65  5091.9   64.93
  5092.6   65.64 5092.69   65.64  5092.8   65.64 5092.91   65.64  5118.9   66.21
  5172.3   67.38  5183.6   68.27  5336.7   67.42  5423.8    68.5  5673.8    67.8
  5763.8    69.7  5783.8    70.5    5826   70.62  5853.8    70.7  6203.8    76.6
    6236   76.45  6353.8    75.9  6373.8    74.9  6403.8    74.8  6443.8    76.9
  6553.8      78  6593.8    77.2  6600.9    77.3  6676.6      76
BR D #Mann= 13
  1790.6     .99    2309     .08  3563.7     .05  3766.3     .12  3926.7     .08
  4113.9     .12  4420.6     .08  4680.2     .05  4893.3     .04  4932.2    .015
    5041     .04  5091.9     .07  6600.9     .99
BC Design=,, 0 ,, 0 ,,,,,,
BC HTab HWMax=79.5
BC Use User HTab Curves=0
BC User HTab FreeFlow(D)= 0

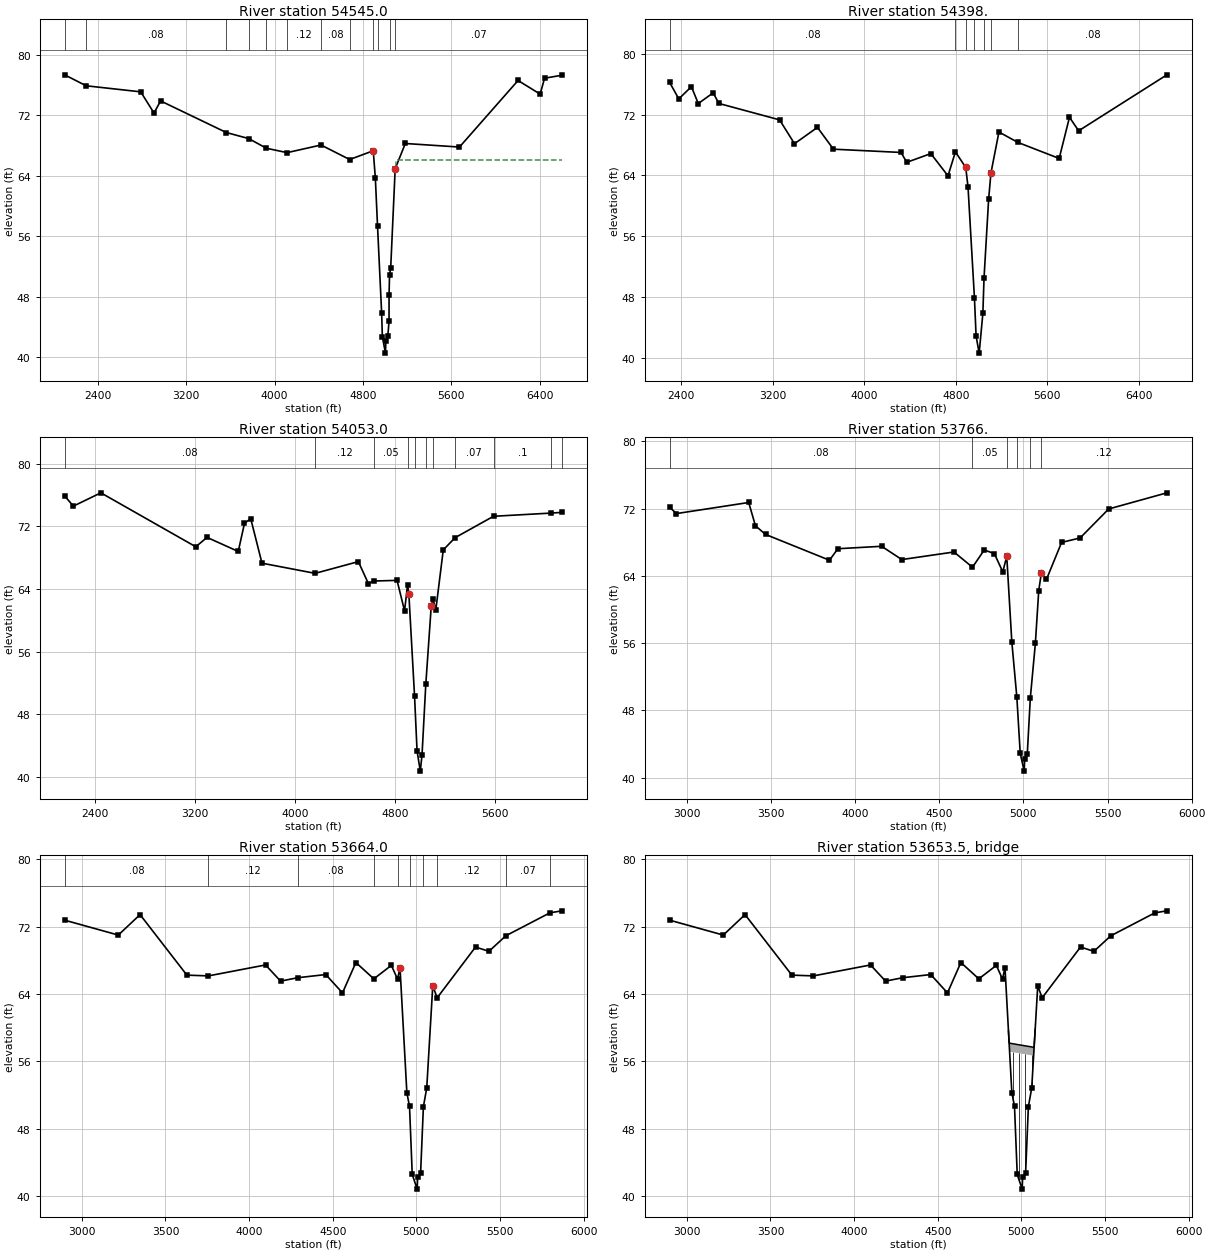
Type RM Length L Ch R = 1 ,54545.0 ,89.5,147,175.4
BEGIN DESCRIPTION:
Downstream Section of Bridge/Culvert/Weir
END DESCRIPTION:
XS GIS Cut Line= 6
 3093568.340025813871638.0907463      3093400.06     13871539.37
      3091286.74      13870299.6      3091247.11     13870279.06
      3090714.57     13870261.19      3089437.31     13870242.02
#Sta/Elev= 30
  2100.6   77.35  2295.7    75.9    2789    75.1    2909    72.3    2969    73.9
  3563.7   69.72  3766.3   68.92  3926.7   67.64  4113.9   67.06  4420.6   68.07
  4680.2   66.15  4893.3   67.31  4912.5   63.68  4932.2   57.34  4969.5   45.81
  4975.8   42.71  5004.1   40.55  5007.1    42.1    5025   42.76  5036.3   44.76
  5036.4    48.3    5041   50.89  5051.4   51.84  5091.9   64.93  5183.6   68.27
  5673.8    67.8  6203.8    76.6  6403.8    74.8  6443.8    76.9  6600.7    77.3
#Mann= 12 ,-1 , 0
  2100.6     .99       0  2295.7     .08       0  3563.7     .05       0
  3766.3     .12       0  3926.7     .08       0  4113.9     .12       0
  4420.6     .08       0  4680.2     .05       0  4893.3     .04       0
  4932.2    .015       0    5041     .04       0  5091.9     .07       0
#XS Ineff= 2 , 0
       0 4886.63    66.1 5098.57       0    66.1
Permanent Ineff=
       F       F
Bank Sta=4893.3,5091.9
XS Rating Curve= 0 ,0
Exp/Cntr=0.5,0.3

Type RM Length L Ch R = 1 ,54398.  ,175.7,345,406.1
BEGIN DESCRIPTION:
Pinemont - D/S - XS 1
END DESCRIPTION:
XS GIS Cut Line= 4
      3093402.89     13871437.49      3091249.94     13870177.18
      3090876.25     13870081.38      3089423.86     13869929.89
#Sta/Elev= 30
    2302   76.23    2382   74.06    2492   75.67    2552   73.45    2682   74.86
    2732   73.46    3262    71.3    3392   68.16    3592   70.31    3732   67.44
    4322   67.01    4372   65.71    4582   66.86    4732   63.93  4796.7   67.09
  4886.7   65.04  4906.7   62.49 4962.81   47.87 4977.27   42.83  5004.1   40.59
  5036.3   45.81  5046.7   50.52  5086.7   60.84  5106.7   64.29  5176.7    69.7
  5342.5   68.33  5702.5   66.22  5792.5   71.64  5872.5   69.86  6642.8   77.23
#Mann= 7 ,-1 , 0
    2302     .08       0  4796.7     .05       0  4886.7     .04       0
 4962.81    .015       0  5046.7     .04       0  5106.7     .05       0
  5342.5     .08       0
Bank Sta=4886.7,5106.7
XS Rating Curve= 0 ,0
Exp/Cntr=0.3,0.1

Type RM Length L Ch R = 1 ,54053.0 ,331.1,287,276
BEGIN DESCRIPTION:
Cross Section E100-00-00-X36.5
END DESCRIPTION:
XS GIS Cut Line= 4
      3093564.07     13871424.55      3091657.22     13870264.83
      3090893.37     13869506.55       3090224.3     13869428.49
#Sta/Elev= 30
  2156.3    75.9  2226.3    74.6  2446.3    76.3  3206.3    69.4  3296.3    70.6
  3546.3    68.8  3596.3    72.4  3646.3      73  3736.3    67.3  4162.2      66
  4508.1    67.5  4588.1    64.7  4633.5   65.02  4818.1    65.1  4878.1    61.2
  4902.3   64.54  4912.5   63.37  4958.1    50.3  4978.1    43.3  5004.1    40.7
  5018.1    42.8  5048.1    51.8  5091.9   61.84  5105.1   62.78  5128.1    61.3
  5188.1      69  5282.5   70.56  5590.4    73.3  6053.1   73.71    6138    73.8
#Mann= 11 ,-1 , 0
  2156.3     .08       0  4162.2     .12       0  4633.5     .05       0
  4902.3     .04       0  4958.1    .015       0  5048.1     .04       0
  5105.1     .12       0  5282.5     .07       0  5590.4      .1       0
  6053.1     .08       0    6138     .99       0
Bank Sta=4912.5,5091.9
XS Rating Curve= 0 ,0
Exp/Cntr=0.3,0.1

Type RM Length L Ch R = 1 ,53766.  ,102.3,102,76.8
BEGIN DESCRIPTION:
PL_34a U/S - XS 4
END DESCRIPTION:
XS GIS Cut Line= 4
      3093108.62     13870921.98      3091505.65     13869736.36
      3091378.66     13869561.75      3090638.93      13869466.5
#Sta/Elev= 30
  2897.2   72.18  2937.2   71.42  3367.2   72.74  3407.2   69.97  3467.2   68.94
  3847.2   65.87  3897.2   67.24  4157.2   67.53  4277.2   65.95  4587.2   66.85
  4697.2   65.04  4767.2   67.09  4827.2   66.66  4877.2   64.49    4901   66.32
    4931   56.17    4961   49.55    4981   42.91 5004.46   40.78  5007.6   42.22
 5022.98   42.83    5041   49.49    5071   55.98    5091   62.26  5106.9   64.39
  5136.9   63.59  5226.9   67.99  5336.9   68.52  5506.9   71.97  5852.7   73.89
#Mann= 6 ,-1 , 0
  2897.2     .08       0  4697.2     .05       0    4901     .04       0
    4961    .015       0    5041     .04       0  5106.9     .12       0
Bank Sta=4901,5106.9
XS Rating Curve= 0 ,0
Exp/Cntr=0.5,0.3

Type RM Length L Ch R = 1 ,53664.0 ,21.4,22,29.3
BEGIN DESCRIPTION:
Upstream Section of Bridge/Culvert/Weir
END DESCRIPTION:
XS GIS Cut Line= 5
       3093182.2     13870856.89      3091554.89     13869649.43
      3091520.36     13869584.08      3091480.91     13869508.87
      3090695.18     13869466.25
#Sta/Elev= 30
  2897.5   72.76  3218.2   70.99  3348.2   73.42  3628.2   66.23  3756.8   66.14
  4098.2   67.44  4188.2   65.52  4289.4   65.92  4458.2    66.3  4558.2   64.12
  4638.2   67.73  4745.5   65.79 4850.29   67.39  4887.2   65.75 4901.99   67.12
 4942.99   52.24 4958.79   50.65 4975.09   42.55 5004.59   40.81 5007.29    42.2
 5024.99   42.67 5041.69   50.59 5061.79   52.84 5097.69   64.95  5124.2   63.54
  5353.4   69.57  5433.4   69.06  5534.8   70.91  5797.8   73.63  5869.6   73.87
#Mann= 10 ,-1 , 0
  2897.5     .08       0  3756.8     .12       0  4289.4     .08       0
  4745.5     .05       0  4887.2     .04       0 4958.79    .015       0
 5041.69     .04       0  5124.2     .12       0  5534.8     .07       0
  5797.8      .1       0
#XS Ineff= 2 , 0
       0 4924.13   57.12 5076.75       0   56.65
Permanent Ineff=
       F       F
Bank Sta=4901.99,5097.69
XS Rating Curve= 0 ,0
Exp/Cntr=0.5,0.3

Type RM Length L Ch R = 3 ,53653.5 ,,,
BEGIN DESCRIPTION:
PL1_E100-00-00-34a
END DESCRIPTION:
Bridge Culvert--1,0,-1,-1, 0
Deck Dist Width WeirC Skew NumUp NumDn MinLoCord MaxHiCord MaxSubmerge Is_Ogee
10,1,2.6,0, 24, 24, , , 0.95, 0, ,,,
 4922.69 4926.59  4929.4 4929.49 4942.99 4949.09 4958.79 4975.09 4985.69 4992.69
 4993.59 4994.89 5004.59 5006.39 5007.29 5023.39 5024.99 5041.69 5061.79 5063.09
 5072.58 5072.69 5075.99 5082.29
    59.6   58.19   58.15   58.15    58.1   58.08   58.05   57.99   57.96   57.93
   57.93   57.93   57.89   57.89   57.88   57.83   57.82   57.77    57.7   57.69
   57.66   57.66   57.71    59.8
    59.6   58.18   57.16   57.15    57.1   57.08   57.05   56.99   56.96   56.93
   56.93   56.93   56.89   56.89   56.88   56.83   56.82   56.77    56.7   56.69
   56.66   56.59    57.7    59.8
 4922.69 4926.59  4929.4 4929.49 4942.99 4949.09 4958.79 4975.09 4985.69 4992.69
 4993.59 4994.89 5004.59 5006.39 5007.29 5023.39 5024.99 5041.69 5061.79 5063.09
 5072.58 5072.69 5075.99 5082.29
    59.6   58.19   58.15   58.15    58.1   58.08   58.05   57.99   57.96   57.93
   57.93   57.93   57.89   57.89   57.88   57.83   57.82   57.77    57.7   57.69
   57.66   57.66   57.71    59.8
    59.6   58.18   57.16   57.15    57.1   57.08   57.05   56.99   56.96   56.93
   56.93   56.93   56.89   56.89   56.88   56.83   56.82   56.77    56.7   56.69
   56.66   56.59    57.7    59.8
Pier Skew, UpSta & Num, DnSta & Num=  ,4949.1, 2 ,4949.1, 2 , 0 , 0 , 0 ,,
     1.2     1.2
   50.96   58.08
     1.2     1.2
   50.96   58.08
Pier Skew, UpSta & Num, DnSta & Num=  ,4985.7, 2 ,4985.7, 2 , 0 , 0 , 0 ,,
     1.2     1.2
   41.35   57.96
     1.2     1.2
   41.35   57.96
Pier Skew, UpSta & Num, DnSta & Num=  ,5023.4, 2 ,5023.4, 2 , 0 , 0 , 0 ,,
     1.2     1.2
   41.43   57.83
     1.2     1.2
   41.43   57.83
Pier Skew, UpSta & Num, DnSta & Num=  ,5061.8, 2 ,5061.8, 2 , 0 , 0 , 0 ,,
     1.2     1.2
   51.77    57.7
     1.2     1.2
   51.77    57.7
BR Coef= 1 , 1 , 0 ,1.25, 0 ,,,0.8,-1,2,0,
WSPro=,,,, 1 ,,,, 0 ,,,, 0 ,,,,-1 ,-1 ,-1 , 0 , 0 , 0 , 0 , 0
BC Design=,, 0 ,, 0 ,,,,,,
BC HTab HWMax=73.87
BC Use User HTab Curves=0
BC User HTab FreeFlow(D)= 0