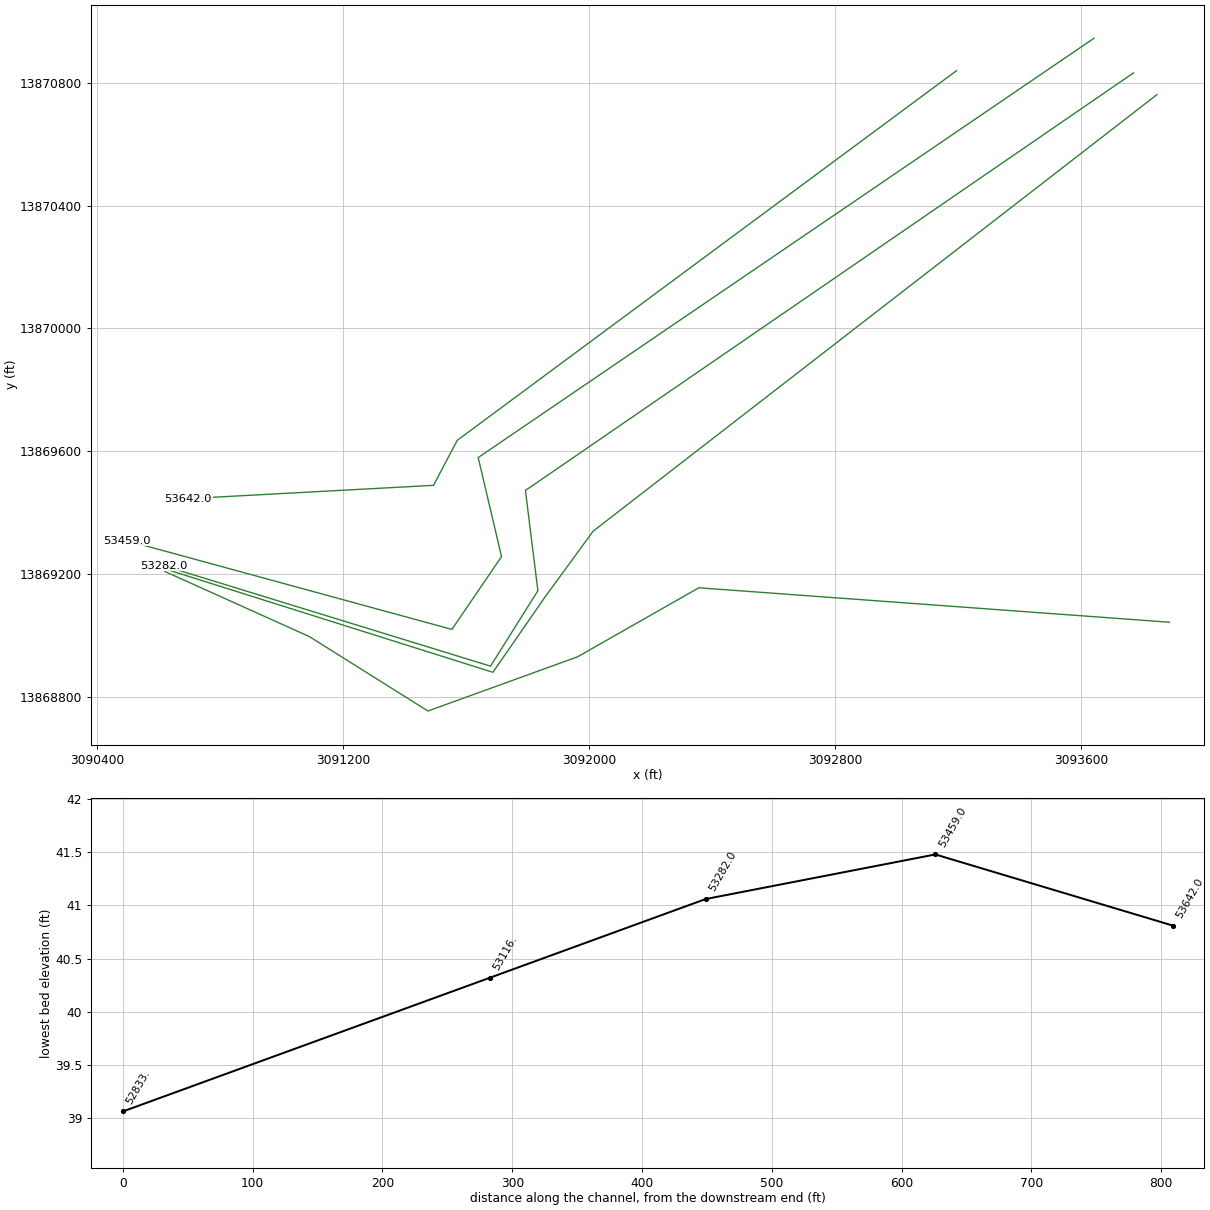
HEC-RAS study E100-00-00.prj: E100-00-00

--- E100-00-00.g02 (geometry) --- (continued)

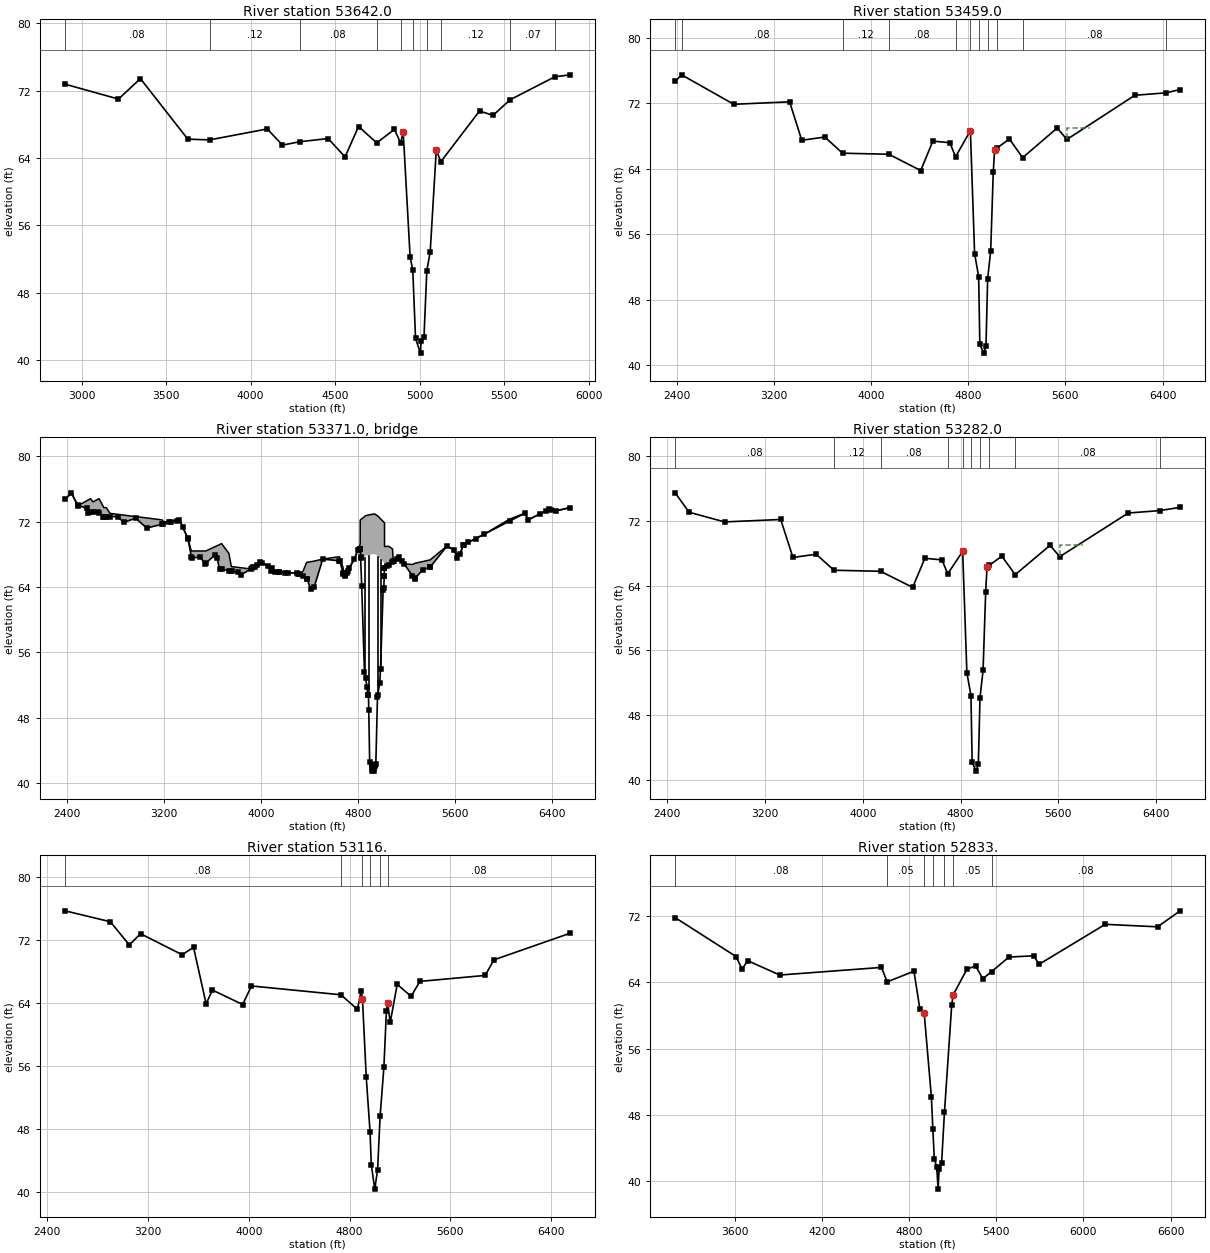
Type RM Length L Ch R = 1 ,53642.0 ,105.1,183,400.5
BEGIN DESCRIPTION:
Downstream Section of Bridge/Culvert/Weir
END DESCRIPTION:
XS GIS Cut Line= 5
      3093194.71     13870840.02      3091571.23      13869635.4
      3091538.94      13869574.3      3091493.96     13869488.55
      3090696.32     13869445.28
#Sta/Elev= 30
  2902.4   72.76  3218.2   70.99  3348.2   73.42  3628.2   66.23  3756.8   66.14
  4098.2   67.44  4188.2   65.52  4289.4   65.92  4458.2    66.3  4558.2   64.12
  4638.2   67.73  4745.5   65.79 4850.29   67.39  4887.2   65.75 4901.99   67.12
 4942.99   52.24 4958.79   50.65 4975.09   42.55 5004.59   40.81 5007.29    42.2
 5024.99   42.67 5041.69   50.59 5061.79   52.84 5097.69   64.95  5124.2   63.54
  5353.4   69.57  5433.4   69.06  5534.8   70.91  5797.8   73.63  5888.7   73.87
#Mann= 10 ,-1 , 0
  2902.4     .08       0  3756.8     .12       0  4289.4     .08       0
  4745.5     .05       0  4887.2     .04       0 4958.79    .015       0
 5041.69     .04       0  5124.2     .12       0  5534.8     .07       0
  5797.8      .1       0
#XS Ineff= 2 , 0
       0 4920.59   57.08  5080.3       0   56.69
Permanent Ineff=
       F       F
Bank Sta=4901.99,5097.69
XS Rating Curve= 0 ,0
Exp/Cntr=0.5,0.3

Type RM Length L Ch R = 1 ,53459.0 ,178.7,177,175.6
BEGIN DESCRIPTION:
Upstream Section of Bridge/Culvert/Weir
Channel is skewed 45 degrees.
END DESCRIPTION:
XS GIS Cut Line= 5
      3093642.02     13870945.87      3091639.12     13869578.96
      3091715.06     13869256.22      3091553.69     13869018.91
      3090495.28     13869308.43
#Sta/Elev= 30
  2385.5    74.7  2438.3    75.5  2868.3    71.9  3328.3    72.2  3428.3    67.5
  3618.3    67.9  3764.3   65.92  4145.3   65.79  4408.3    63.8  4508.3    67.4
  4648.3    67.2  4695.3   65.48  4817.5   68.67 4852.22   53.65 4885.39   50.83
 4895.28   42.57 4927.14   41.48 4945.85   42.31 4959.58   50.57 4984.52   53.95
 5005.92   63.61 5017.02   66.33 5036.23   66.54 5138.63   67.66 5247.63   65.37
 5532.43      69 5612.43    67.6 6172.43      73 6429.73    73.3 6545.53    73.7
#Mann= 11 ,-1 , 0
  2385.5     .99       0  2438.3     .08       0  3764.3     .12       0
  4145.3     .08       0  4695.3     .05       0  4817.5     .04       0
 4885.39    .015       0 4959.58     .04       0 5036.23     .12       0
 5247.63     .08       0 6429.73     .99       0
#XS Ineff= 3 ,-1
  5614.8    5800      69 5107.69    5600   66.75  2385.5  4807.5   65.31
Permanent Ineff=
       F       F       F
Bank Sta=4817.5,5017.02
XS Rating Curve= 0 ,0
Exp/Cntr=0.5,0.3

Type RM Length L Ch R = 3 ,53371.0 ,,,
BEGIN DESCRIPTION:
MANGUM (WATONGA-FIELD)
Structure ID: E100-00-00-34
Bridge has 45 degree skew with the channel.
END DESCRIPTION:
Bridge Culvert--1,0,-1,-1, 0
Deck Dist Width WeirC Skew NumUp NumDn MinLoCord MaxHiCord MaxSubmerge Is_Ogee
10,156,2.6,0, 146, 146, , , 0.95, 0, ,,,
  2385.5  2438.3  2488.3  2495.5  2568.3  2578.3  2595.5  2615.5  2658.3  2665.5
  2698.3  2705.5  2725.5  2755.5  2818.3  2868.3  2968.3  3058.3  3185.5  3195.5
  3245.5  3255.5  3305.5  3328.3  3355.5  3395.5  3398.3  3425.5  3428.3  3498.3
  3538.3  3545.5  3618.3  3638.3  3658.3  3675.5  3735.5  3755.5  3764.3  3808.3
  3838.3  3915.5  3925.5  3935.5  3948.3  3965.5  3988.3  4005.5  4058.3  4078.3
  4088.3  4118.3  4145.3  4145.5  4195.5  4225.5  4298.3  4305.5  4315.5  4345.5
  4375.5  4378.3  4408.3  4438.3  4508.3  4645.5  4648.3  4675.5  4678.3  4688.3
  4695.3  4695.5  4705.5  4715.5  4725.5  4768.3  4798.3  4805.5 4816.99 4817.07
 4817.15 4817.35 4820.16 4820.21 4829.42 4852.07 4861.16 4873.52 4878.78 4885.24
 4887.47 4895.14 4912.07 4915.44 4916.24 4916.52 4926.99 4927.62 4935.92    4939
  4945.7 4959.43 4962.06 4977.68 4984.37 5005.77 5011.43 5014.63 5014.69  5017.3
  5017.4  5017.5 5017.61  5036.6    5053  5083.5    5090    5100    5120    5139
    5160    5180    5248  5265.8    5270  5332.8  5389.3  5392.8  5532.8  5592.8
  5612.8  5642.8  5662.8  5669.3  5709.3  5769.3  5839.3  6049.3  6172.8  6202.8
  6299.3  6349.3  6372.8  6389.3  6430.1  6545.9
    74.7   75.51   74.01   73.97   74.56   74.65    74.8    74.4   74.74    74.8
    73.9    73.7    73.7      73   72.88   72.79    72.6   72.44    72.2      72
    71.9   71.94   72.13   72.21   71.32      70   69.91    68.4    68.4    68.4
    68.4    68.4    68.9   69.04   69.18    69.3    68.1    66.5   66.48    66.4
   66.34    66.2    66.3   66.39   66.51   66.73   67.01   66.91   66.61   66.04
   66.31    65.9    65.8    65.8   65.77   65.75   65.71   65.65   65.56    65.9
      67   67.01   67.09   67.16   67.41    67.7   67.58    66.4   66.16   65.31
   65.49    65.5   65.76   66.02   66.29   67.41   68.51   68.57   69.27   72.17
   72.17   72.17   72.21   72.21   72.32    72.6   72.71   72.76   72.78    72.8
   72.81   72.83   72.87   72.88   72.88   72.88   72.91   72.91   72.93    72.9
   72.84   72.71   72.68   72.44   72.34   72.01   71.92   71.87   71.87   71.84
   71.84   71.84   68.94   68.96   68.97   68.64   67.13   67.24   67.46   67.67
   67.23   66.81   66.75   66.87    66.9   67.11    67.3   67.31   69.01   68.51
   68.02   68.11   69.11   69.16   69.47   69.92   70.46    72.3   73.01   72.24
   72.95   73.33   73.51   73.45   73.31    73.7
                                                                                
                                                                                
                                                                                
                                                                                
                                                                                
                                                                                
                                                                                
                                                                                
                            67.6   67.42    67.7   67.81   67.86   67.88    67.9
   67.91   67.93   67.97   67.98   67.98   67.98   68.01   68.01   68.03      68
   67.94   67.81   67.78   67.54   67.44   67.11   67.02   66.97
                                                                                
                                                                                
                                                                                
                                                
  2385.5  2438.3  2488.3  2495.5  2568.3  2578.3  2595.5  2615.5  2658.3  2665.5
  2698.3  2705.5  2725.5  2755.5  2818.3  2868.3  2968.3  3058.3  3185.5  3195.5
  3245.5  3255.5  3305.5  3328.3  3355.5  3395.5  3398.3  3425.5  3428.3  3498.3
  3538.3  3545.5  3618.3  3638.3  3658.3  3675.5  3735.5  3755.5  3764.3  3808.3
  3838.3  3915.5  3925.5  3935.5  3948.3  3965.5  3988.3  4005.5  4058.3  4078.3
  4088.3  4118.3  4145.3  4145.5  4195.5  4225.5  4298.3  4305.5  4315.5  4345.5
  4375.5  4378.3  4408.3  4438.3  4508.3  4645.5  4648.3  4675.5  4678.3  4688.3
  4695.3  4695.5  4705.5  4715.5  4725.5  4768.3  4798.3  4805.5 4816.99 4817.07
 4817.15 4817.35 4820.16 4820.21 4829.42 4852.07 4861.16 4873.52 4878.78 4885.24
 4887.47 4895.14 4912.07 4915.44 4916.24 4916.52 4926.99 4927.62 4935.92    4939
  4945.7 4959.43 4962.06 4977.68 4984.37 5005.77 5011.43 5014.63 5014.69  5017.3
  5017.4  5017.5 5017.61  5036.6    5053  5083.5    5090    5100    5120    5139
    5160    5180    5248  5265.8    5270  5332.8  5389.3  5392.8  5532.8  5592.8
  5612.8  5642.8  5662.8  5669.3  5709.3  5769.3  5839.3  6049.3  6172.8  6202.8
  6299.3  6349.3  6372.8  6389.3  6430.1  6545.9
    74.7   75.51   74.01   73.97   74.56   74.65    74.8    74.4   74.74    74.8
    73.9    73.7    73.7      73   72.88   72.79    72.6   72.44    72.2      72
    71.9   71.94   72.13   72.21   71.32      70   69.91    68.4    68.4    68.4
    68.4    68.4    68.9   69.04   69.18    69.3    68.1    66.5   66.48    66.4
   66.34    66.2    66.3   66.39   66.51   66.73   67.01   66.91   66.61   66.04
   66.31    65.9    65.8    65.8   65.77   65.75   65.71   65.65   65.56    65.9
      67   67.01   67.09   67.16   67.41    67.7   67.58    66.4   66.16   65.31
   65.49    65.5   65.76   66.02   66.29   67.41   68.51   68.57   69.27   72.17
   72.17   72.17   72.21   72.21   72.32    72.6   72.71   72.76   72.78    72.8
   72.81   72.83   72.87   72.88   72.88   72.88   72.91   72.91   72.93    72.9
   72.84   72.71   72.68   72.44   72.34   72.01   71.92   71.87   71.87   71.84
   71.84   71.84   68.94   68.96   68.97   68.64   67.13   67.24   67.46   67.67
   67.23   66.81   66.75   66.87    66.9   67.11    67.3   67.31   69.01   68.51
   68.02   68.11   69.11   69.16   69.47   69.92   70.46    72.3   73.01   72.24
   72.95   73.33   73.51   73.45   73.31    73.7
                                                                                
                                                                                
                                                                                
                                                                                
                                                                                
                                                                                
                                                                                
                                                                                
                            67.6   67.42    67.7   67.81   67.86   67.88    67.9
   67.91   67.93   67.97   67.98   67.98   67.98   68.01   68.01   68.03      68
   67.94   67.81   67.78   67.54   67.44   67.11   67.02   66.97
                                                                                
                                                                                
                                                                                
                                                
Pier Skew, UpSta & Num, DnSta & Num=  ,4852.25, 2 ,4852.25, 2 , 0 , 0 , 0 ,,
     1.5     1.5
   50.69   68.86
     1.5     1.5
    50.3   68.47
Pier Skew, UpSta & Num, DnSta & Num=  ,4885.56, 2 ,4885.56, 2 , 0 , 0 , 0 ,,
     1.5     1.5
   41.15   68.97
     1.5     1.5
   40.76   68.58
Pier Skew, UpSta & Num, DnSta & Num=  ,4959.5, 2 ,4959.5, 2 , 0 , 0 , 0 ,,
     1.5     1.5
   41.18      69
     1.5     1.5
   40.79   68.61
Pier Skew, UpSta & Num, DnSta & Num=  ,4984.54, 2 ,4984.54, 2 , 0 , 0 , 0 ,,
     1.5     1.5
   51.24   68.55
     1.5     1.5
   50.85   68.16
BR Coef= 1 , 1 , 0 ,1.25, 0 ,,,0.8,-1,1.2,0,
WSPro=,,,, 1 ,,,, 0 ,,,, 0 ,,,,-1 ,-1 ,-1 , 0 , 0 , 0 , 0 , 0
BR U #Sta/Elev= 145
  2385.5    74.7  2438.3    75.5  2488.3      74  2495.5   73.96  2568.3    73.6
  2578.3    73.1  2595.5   73.12  2615.5   73.15  2658.3    73.2  2665.5   73.09
  2698.3    72.6  2705.5    72.6  2725.5    72.6  2755.5    72.6  2818.3    72.6
  2868.3    71.9  2968.3    72.4  3058.3    71.2  3185.5   71.67  3195.5   71.71
  3245.5   71.89  3255.5   71.93  3305.5   72.12  3328.3    72.2  3355.5   71.31
  3395.5   69.99  3398.3    69.9  3425.5   67.72  3428.3    67.5  3498.3    67.7
  3538.3    66.8  3545.5    66.9  3618.3    67.9  3638.3    67.5  3658.3    66.2
  3675.5   66.15  3735.5   65.99  3755.5   65.94  3764.3   65.92  3808.3    65.8
  3838.3    65.5  3915.5    66.2  3925.5   66.29  3935.5   66.38  3948.3    66.5
  3965.5   66.72  3988.3      67  4005.5    66.9  4058.3    66.6  4078.3      66
  4088.3    66.3  4118.3    65.8  4145.3   65.79  4145.5   65.78  4195.5   65.76
  4225.5   65.74  4298.3    65.7  4305.5   65.64  4315.5   65.55  4345.5   65.29
  4375.5   65.02  4378.3      65  4408.3    63.8  4438.3      64  4508.3    67.4
  4645.5    67.2  4648.3    67.2  4675.5   65.75  4678.3    65.6  4688.3    65.3
  4695.3   65.48  4695.5   65.49  4705.5   65.75  4715.5   66.01  4725.5   66.28
  4768.3    67.4  4798.3    68.5  4805.5   68.56 4816.99   68.67  4817.1   68.67
 4817.21   68.67  4817.5   68.67 4820.31   67.62 4820.36    67.6 4829.57   64.16
 4852.22   53.65 4861.31   52.85 4873.66   51.76 4878.92   50.84 4885.39   50.83
 4887.61   48.97 4895.28   42.57 4912.21   42.17 4915.58   42.03 4916.67   41.49
 4927.14   41.48 4927.77   41.88 4936.06   42.11 4939.15   42.19 4945.85   42.31
 4959.58   50.57 4962.21   50.82 4977.83   52.28 4984.52   53.95 5005.92   63.61
 5011.58   63.82 5014.77   65.31 5014.84   65.34 5016.95   66.33 5017.02   66.33
 5017.13   66.33 5017.24   66.33 5036.23   66.54 5052.63   66.72 5083.13   67.05
 5089.63   67.12 5099.63   67.23 5119.63   67.45 5138.63   67.66 5159.63   67.22
 5179.63    66.8 5247.63   65.37 5265.43      65 5269.63   65.07 5332.43    66.1
 5388.93   66.38 5392.43    66.4 5532.43      69 5592.43    68.5 5612.43    67.6
 5642.43      68 5662.43    69.1 5668.93   69.15 5708.93   69.46 5768.93   69.91
 5838.93   70.45 6048.93   72.06 6172.43      73 6202.43    72.2 6298.93   72.94
 6348.93   73.32 6372.43    73.5 6388.93   73.44 6429.73    73.3 6545.53    73.7
BR U #Mann= 10
  2385.5     .99  2438.3     .08  3764.3     .12  4145.3     .08  4695.3     .05
  4817.5    .015 5017.02     .04 5036.23     .12 5247.63     .08 6429.73     .99
BR D #Sta/Elev= 145
  2385.5    74.7  2438.3    75.5  2488.3      74  2495.5   73.96  2568.3    73.6
  2578.3    73.1  2595.5   73.12  2615.5   73.15  2658.3    73.2  2665.5   73.09
  2698.3    72.6  2705.5    72.6  2725.5    72.6  2755.5    72.6  2818.3    72.6
  2868.3    71.9  2968.3    72.4  3058.3    71.2  3185.5   71.67  3195.5   71.71
  3245.5   71.89  3255.5   71.93  3305.5   72.12  3328.3    72.2  3355.5   71.31
  3395.5   69.99  3398.3    69.9  3425.5   67.72  3428.3    67.5  3498.3    67.7
  3538.3    66.8  3545.5    66.9  3618.3    67.9  3638.3    67.5  3658.3    66.2
  3675.5   66.15  3735.5   65.99  3755.5   65.94  3764.3   65.92  3808.3    65.8
  3838.3    65.5  3915.5    66.2  3925.5   66.29  3935.5   66.38  3948.3    66.5
  3965.5   66.72  3988.3      67  4005.5    66.9  4058.3    66.6  4078.3      66
  4088.3    66.3  4118.3    65.8  4145.3   65.79  4145.5   65.78  4195.5   65.76
  4225.5   65.74  4298.3    65.7  4305.5   65.64  4315.5   65.55  4345.5   65.29
  4375.5   65.02  4378.3      65  4408.3    63.8  4438.3      64  4508.3    67.4
  4645.5    67.2  4648.3    67.2  4675.5   65.75  4678.3    65.6  4688.3    65.3
  4695.3   65.48  4695.5   65.49  4705.5   65.75  4715.5   66.01  4725.5   66.28
  4768.3    67.4  4798.3    68.5  4805.5   68.56 4816.99   68.67  4817.1   68.67
 4817.21   68.67  4817.5   68.25 4820.31    67.2 4820.36   67.18 4829.57   63.74
 4852.22   53.23 4861.31   52.43 4873.66   51.34 4878.92   50.42 4885.39   50.41
 4887.61   48.55 4895.28   42.15 4912.21   41.75 4915.58   41.61 4916.67   41.07
 4927.14   41.06 4927.77   41.46 4936.06   41.69 4939.15   41.77 4945.85   41.89
 4959.58   50.15 4962.21    50.4 4977.83   51.86 4984.52   53.53 5005.92   63.19
 5011.58    63.4 5014.77   64.89 5014.84   64.92 5016.95   65.91 5017.02   66.33
 5017.13   66.33 5017.24   66.33 5036.23   66.54 5052.63   66.72 5083.13   67.05
 5089.63   67.12 5099.63   67.23 5119.63   67.45 5138.63   67.66 5159.63   67.22
 5179.63    66.8 5247.63   65.37 5265.43      65 5269.63   65.07 5332.43    66.1
 5388.93   66.38 5392.43    66.4 5532.43      69 5592.43    68.5 5612.43    67.6
 5642.43      68 5662.43    69.1 5668.93   69.15 5708.93   69.46 5768.93   69.91
 5838.93   70.45 6048.93   72.06 6172.43      73 6202.43    72.2 6298.93   72.94
 6348.93   73.32 6372.43    73.5 6388.93   73.44 6429.73    73.3 6545.53    73.7
BR D #Mann= 10
  2385.5     .99  2438.3     .08  3764.3     .12  4145.3     .08  4695.3     .05
  4817.5    .015 5017.02     .04 5036.23     .12 5247.63     .08 6429.73     .99
BC Design=,, 0 ,, 0 ,,,,,,
BC HTab HWMax=75.5
BC Use User HTab Curves=0
BC User HTab FreeFlow(D)= 0

Type RM Length L Ch R = 1 ,53282.0 ,219.9,166,26.5
BEGIN DESCRIPTION:
Downstream Section of Bridge/Culvert/Weir
Channel is skewed 45 degrees.
END DESCRIPTION:
XS GIS Cut Line= 6
      3093770.52     13870832.97      3091816.69      13869488.2
      3091792.72     13869472.06      3091833.31       13869145.
      3091679.28     13868899.14      3090615.75     13869226.83
#Sta/Elev= 30
  2464.5    75.5  2578.3    73.1  2868.3    71.9  3328.3    72.2  3428.3    67.5
  3618.3    67.9  3764.3   65.92  4145.3   65.79  4408.3    63.8  4508.3    67.4
  4648.3    67.2  4695.3   65.48  4817.5   68.25 4852.22   53.23 4885.39   50.41
 4895.28   42.15 4927.14   41.06 4945.85   41.89 4959.58   50.15 4984.52   53.53
 5005.92   63.19 5017.02   66.33 5036.23   66.54 5138.63   67.66 5247.63   65.37
 5532.43      69 5612.43    67.6 6172.43      73 6429.73    73.3  6597.8    73.7
#Mann= 10 ,-1 , 0
  2464.5     .08       0  3764.3     .12       0  4145.3     .08       0
  4695.3     .05       0  4817.5     .04       0 4885.39    .015       0
 4959.58     .04       0 5036.23     .12       0 5247.63     .08       0
 6429.73     .99       0
#XS Ineff= 3 ,-1
  5614.6    5800      69    5105    5600   66.75  2464.5 4810.83   65.31
Permanent Ineff=
       F       F       F
Bank Sta=4817.5,5017.02
XS Rating Curve= 0 ,0
Exp/Cntr=0.5,0.3

Type RM Length L Ch R = 1 ,53116.  ,452.9,283,132.5
BEGIN DESCRIPTION:
Magnum (Watonga-Field) - D/S - XS 1
END DESCRIPTION:
XS GIS Cut Line= 5
      3093846.93     13870762.22      3092013.01     13869339.09
       3091856.3     13869124.25      3091686.96     13868879.09
       3090615.3     13869217.77
#Sta/Elev= 30
  2541.7   75.69  2901.7    74.3  3051.7   71.36  3141.7   72.78  3471.7   70.11
  3561.7   71.06  3661.7   63.87  3711.7   65.62  3951.7   63.78  4021.7   66.14
  4731.7   65.02    4863   63.17    4893   65.53    4903   64.44    4933   54.53
    4963   47.62    4973   43.44 5000.31   40.32    5023   42.75    5043    49.6
    5073    55.8    5093   62.97    5103      64    5123    61.5  5178.9   66.34
  5288.9   64.83  5358.9   66.72  5876.9   67.48  5946.9   69.46  6550.8   72.84
#Mann= 6 ,-1 , 0
  2541.7     .08       0  4731.7     .05       0    4903     .04       0
    4963    .015       0    5043     .04       0    5103     .08       0
Bank Sta=4903,5103
XS Rating Curve= 0 ,0
Exp/Cntr=0.3,0.1

Type RM Length L Ch R = 1 ,52833.  ,119.3,73,72
BEGIN DESCRIPTION:
Bicycle Bridge2 - U/S - XS 4
END DESCRIPTION:
XS GIS Cut Line= 6
      3093886.74     13869042.41      3092356.74     13869154.58
      3091962.46     13868929.64      3091475.67     13868752.89
      3091090.47     13868995.35      3090620.36     13869207.66
#Sta/Elev= 30
  3189.6   71.83  3609.6   67.12  3649.6   65.63  3689.6   66.63  3909.6    64.9
  4609.6   65.82  4649.6   64.08  4833.7   65.36  4873.7   60.86  4903.7   60.37
  4953.7   50.17  4963.7   46.31  4973.7   42.72 4990.51   41.77 4999.81   39.06
 5006.89   41.51  5023.7   42.17  5043.7   48.35  5093.7   61.32  5103.7   62.51
  5197.7   65.58  5257.7   66.01  5307.7   64.45  5367.7   65.31  5487.7   67.07
  5657.7   67.22  5695.5    66.2  6150.7   71.02  6510.7   70.72  6666.5   72.65
#Mann= 7 ,-1 , 0
  3189.6     .08       0  4649.6     .05       0  4903.7     .04       0
  4963.7    .015       0  5043.7     .04       0  5103.7     .05       0
  5367.7     .08       0
Bank Sta=4903.7,5103.7
XS Rating Curve= 0 ,0
Exp/Cntr=0.5,0.3