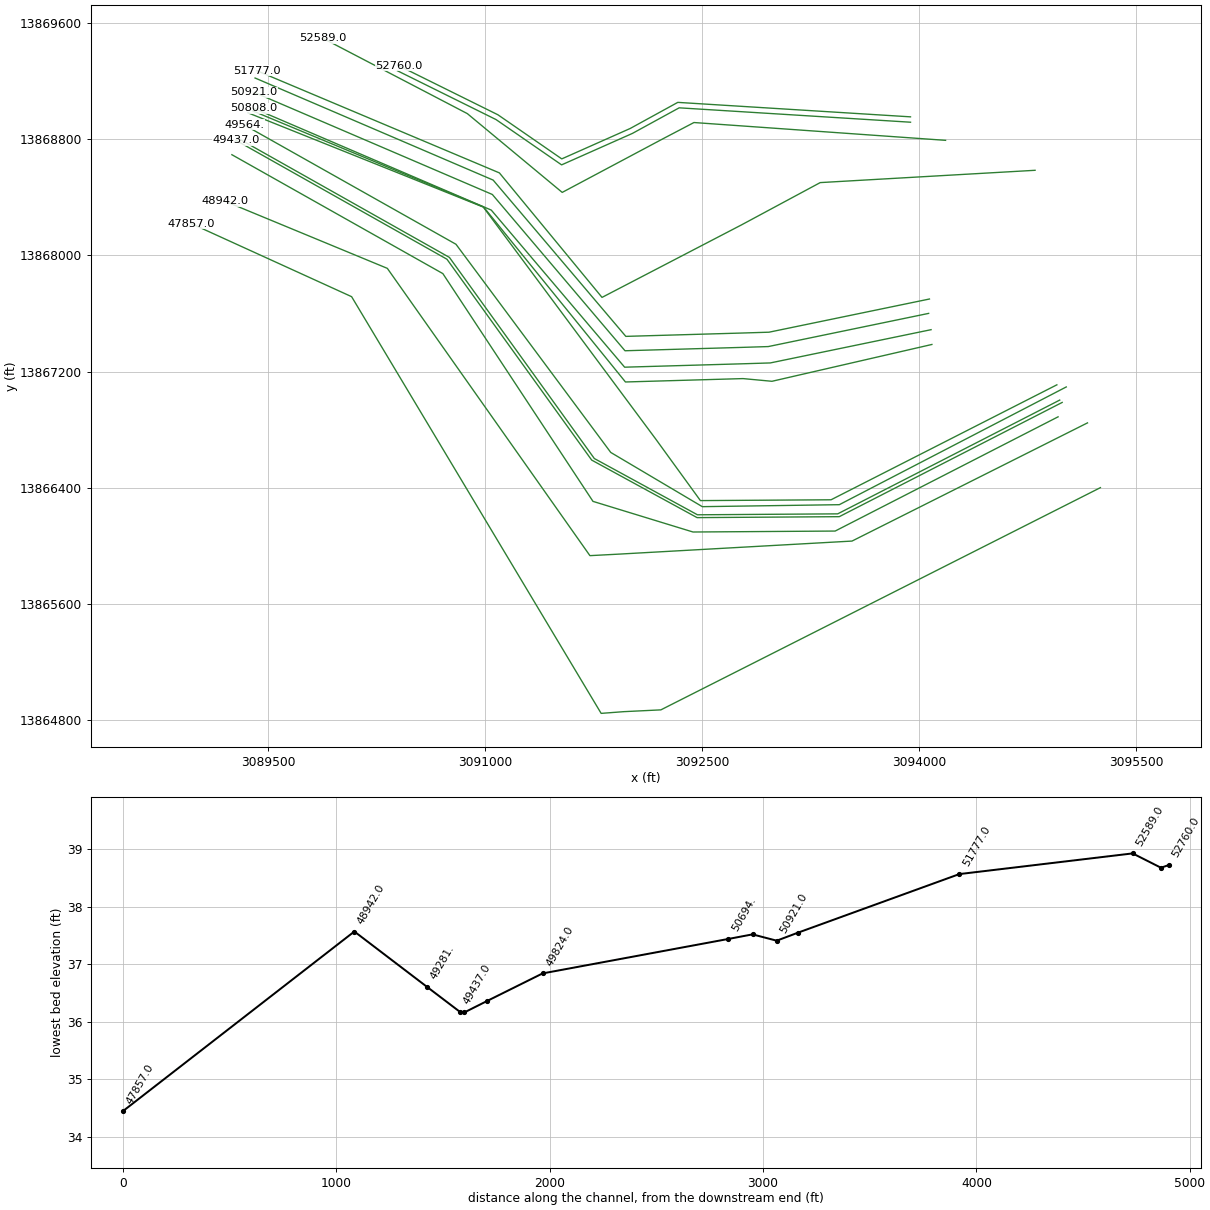
HEC-RAS study E100-00-00.prj: E100-00-00

--- E100-00-00.g02 (geometry) --- (continued)

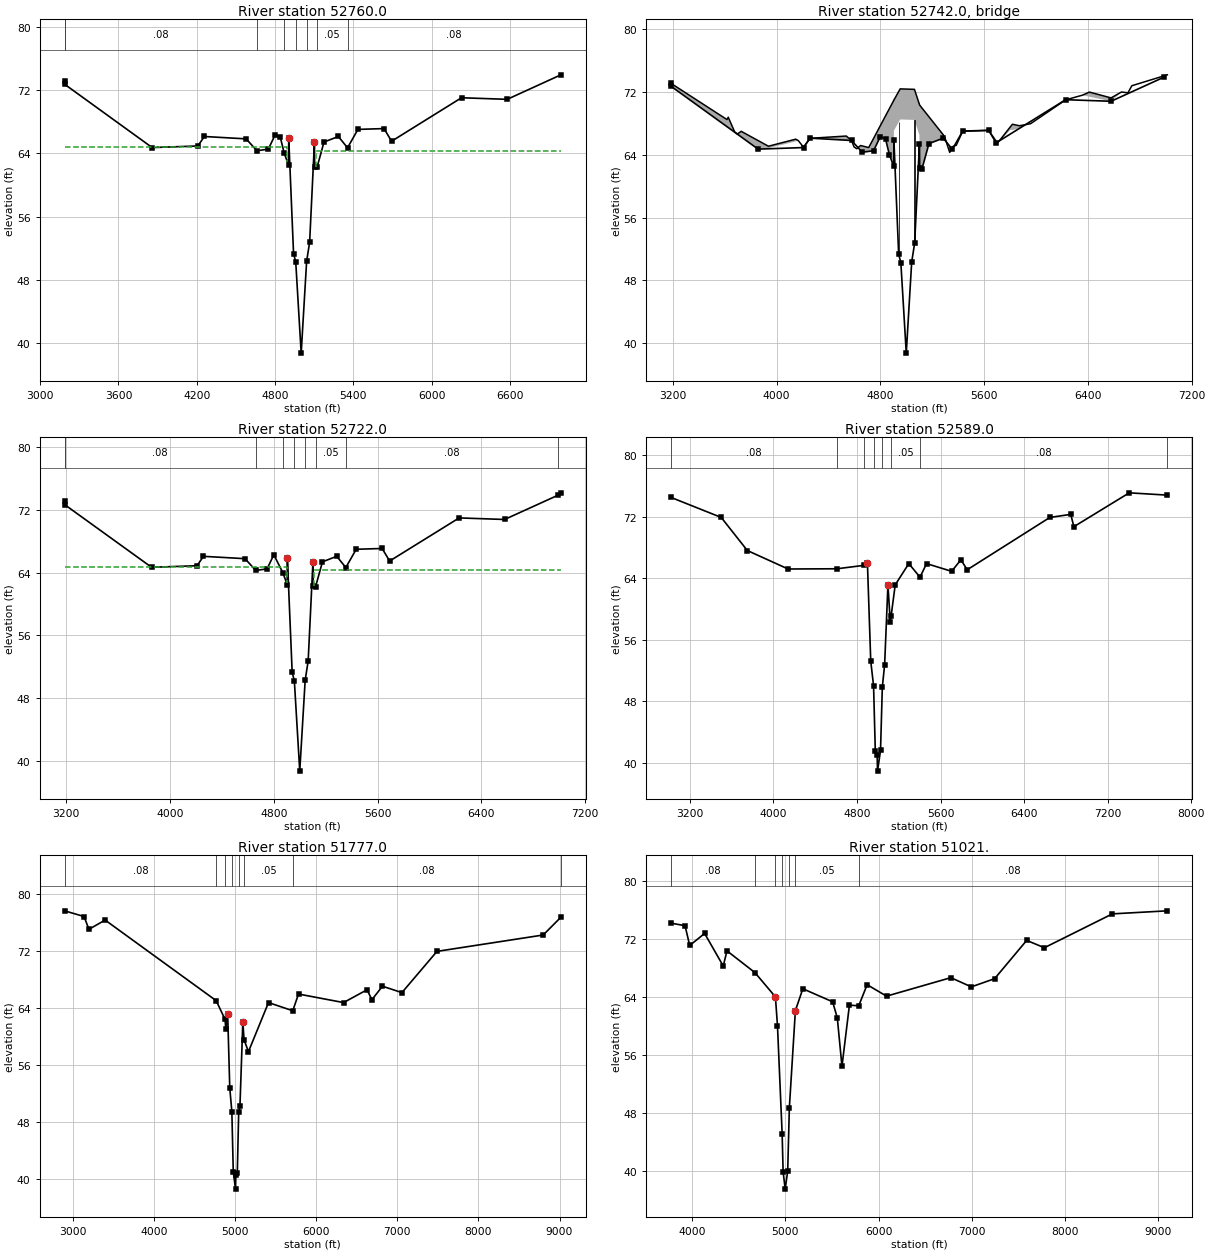
Type RM Length L Ch R = 1 ,52760.0 ,43.9,38,37.4
BEGIN DESCRIPTION:
Upstream Section of Bridge/Culvert/Weir
END DESCRIPTION:
XS GIS Cut Line= 6
      3093940.51     13868954.68      3092331.55     13869054.35
      3092002.86     13868874.71      3091529.44     13868665.16
      3091088.04     13868968.92      3090404.59      13869305.9
#Sta/Elev= 30
  3187.5   73.13  3188.2   72.73  3858.2   64.73  4208.2   64.93  4258.2   66.13
  4578.2   65.83    4661   64.33  4748.2   64.53  4800.2   66.33  4840.2   66.03
  4869.7   64.04  4903.4   62.53  4904.6   65.91  4941.6   51.32  4958.3   50.26
    5000   38.73  5041.8   50.34  5064.8   52.77  5101.7   65.44  5103.4   62.33
  5121.7   62.24  5174.9   65.43  5284.9   66.13  5355.2    64.7  5434.9   67.03
  5634.9   67.13  5692.6   65.53  6228.4   71.03  6578.4   70.83  6989.8   73.93
#Mann= 8 ,-1 , 0
  3187.5     .99       0  3188.2     .08       0    4661     .05       0
  4869.7     .04       0  4958.3    .015       0  5041.8     .04       0
  5121.7     .05       0  5355.2     .08       0
#XS Ineff= 2 , 0
       0  4894.6   64.78  5111.7       0   64.31
Permanent Ineff=
       F       F
Bank Sta=4904.6,5101.7
XS Rating Curve= 0 ,0
Exp/Cntr=0.5,0.3

Type RM Length L Ch R = 3 ,52742.0 ,,,
BEGIN DESCRIPTION:
BICYCLE BRIDGE
Structure ID: E100-00-00-33b
END DESCRIPTION:
Bridge Culvert--1,0,-1,-1, 0
Deck Dist Width WeirC Skew NumUp NumDn MinLoCord MaxHiCord MaxSubmerge Is_Ogee
10,16,2.6,0, 60, 60, , , 0.95, 0, ,,,
  3188.1  3188.2  3618.1  3628.1  3678.1  3698.1  3728.1  3858.2  3938.1  4148.1
  4168.2  4208.2  4258.2  4538.1  4578.2  4598.1  4618.2  4648.2  4710.6  4748.2
  4788.2  4800.2  4840.2  4863.4  4873.4  4893.4  4903.4  4904.6 4904.71  4904.8
  4953.1  5063.2 5101.59  5101.7  5103.4  5123.4  5174.9  5284.9  5304.9  5314.9
  5334.9  5361.9  5384.9  5434.9  5634.9  5692.6    5708  5732.6  5802.6    5818
  5872.6    5958  6228.4  6358.4  6411.1  6578.4  6658.4  6708.4  6738.4  7012.2
    73.1    73.1    68.5    68.8   66.91   66.66      67   65.82    65.1      66
   65.81   64.97   66.11    66.4   65.81   65.01   64.78   65.19   64.93    66.1
   67.35   67.72   68.97   69.69      70   70.62   70.93   70.97   70.97   70.98
   72.41   72.35   70.42   70.42   70.34   69.92   68.85   66.56   65.87   65.31
   64.31    65.1   65.21   67.01   67.11   65.75   65.63   66.11   67.58    67.9
   67.71   67.97   71.01   71.61      72   71.26   72.01   71.91   72.81    74.2
    73.1    72.7   67.63   67.51    66.9   66.65   66.29    64.7   64.86   65.71
    65.8    64.9    66.1   65.84    65.8      65    64.2   64.27   64.41    64.5
    66.1    66.3      66    64.7    63.6    63.3    62.5   65.88   65.84   67.08
   68.51   68.45   66.52   65.41    62.3    62.2    65.4    66.1    65.4    64.6
    64.3   64.79    65.2      67    67.1    65.5   65.62    65.8    67.2   67.16
      67   67.96      71    71.6   71.41    70.8      72    71.9    72.8    74.2
  3188.1  3188.2  3618.1  3628.1  3678.1  3698.1  3728.1  3858.2  3938.1  4148.1
  4168.2  4208.2  4258.2  4538.1  4578.2  4598.1  4618.2  4648.2  4710.6  4748.2
  4788.2  4800.2  4840.2  4863.4  4873.4  4893.4  4903.4  4904.6 4904.71  4904.8
  4953.1  5063.2 5101.59  5101.7  5103.4  5123.4  5174.9  5284.9  5304.9  5314.9
  5334.9  5361.9  5384.9  5434.9  5634.9  5692.6    5708  5732.6  5802.6    5818
  5872.6    5958  6228.4  6358.4  6411.1  6578.4  6658.4  6708.4  6738.4  7012.2
    73.1    73.1    68.5    68.8   66.91   66.66      67   65.82    65.1      66
   65.81   64.97   66.11    66.4   65.81   65.01   64.78   65.19   64.93    66.1
   67.35   67.72   68.97   69.69      70   70.62   70.93   70.97   70.97   70.98
   72.41   72.35   70.42   70.42   70.34   69.92   68.85   66.56   65.87   65.31
   64.31    65.1   65.21   67.01   67.11   65.75   65.63   66.11   67.58    67.9
   67.71   67.97   71.01   71.61      72   71.26   72.01   71.91   72.81    74.2
   73.06   72.66   67.59   67.47   66.86   66.61   66.25   64.66   64.82   65.67
   65.76   64.86   66.06    65.8   65.76   64.96   64.16   64.23   64.37   64.46
   66.06   66.26   65.96   64.66   63.56   63.26   62.46   65.84    65.8   67.04
   68.47   68.41   66.48   65.37   62.26   62.16   65.36   66.06   65.36   64.56
   64.26   64.75   65.16   66.96   67.06   65.46   65.58   65.76   67.16   67.12
   66.96   67.92   70.96   71.56   71.37   70.76   71.96   71.86   72.76   74.16
Pier Skew, UpSta & Num, DnSta & Num=  ,4943.4, 2 ,4943.4, 2 , 0 , 0 , 0 ,,
     2.5     2.5
   50.26   69.25
     2.5     2.5
   50.22   69.21
Pier Skew, UpSta & Num, DnSta & Num=  ,5063.3, 2 ,5063.3, 2 , 0 , 0 , 0 ,,
     2.5     2.5
   51.65   69.45
     2.5     2.5
   51.61   69.41
BR Coef= 1 , 1 , 0 ,1.25, 0 ,,,0.8,-1,1.2,0,
WSPro=,,,, 1 ,,,, 0 ,,,, 0 ,,,,-1 ,-1 ,-1 , 0 , 0 , 0 , 0 , 0
BC Design=,, 0 ,, 0 ,,,,,,
BC HTab HWMax=74.23
BC Use User HTab Curves=0
BC User HTab FreeFlow(D)= 0

Type RM Length L Ch R = 1 ,52722.0 ,114.4,133,141.7
BEGIN DESCRIPTION:
Downstream Section of Bridge/Culvert/Weir
END DESCRIPTION:
XS GIS Cut Line= 6
      3093940.77     13868917.72      3092341.18     13869016.81
      3092018.13     13868840.71      3091528.35     13868623.92
      3091074.93     13868935.96      3090393.43     13869271.97
#Sta/Elev= 30
  3188.1   73.08  3188.2   72.68  3858.2   64.68  4208.2   64.88  4258.2   66.08
  4578.2   65.78    4661   64.28  4748.2   64.48  4800.2   66.28  4869.7   63.99
  4903.4   62.48  4904.6   65.86  4941.6   51.27  4958.3   50.21    5000   38.68
  5041.8   50.29  5064.8   52.72  5101.7   65.39  5103.4   62.28  5121.7   62.19
  5174.9   65.38  5284.9   66.08  5355.2   64.65  5434.9   66.98  5634.9   67.08
  5692.6   65.48  6228.4   70.98  6578.4   70.78  6990.5   73.88  7012.2   74.18
#Mann= 9 ,-1 , 0
  3188.1     .99       0  3188.2     .08       0    4661     .05       0
  4869.7     .04       0  4958.3    .015       0  5041.8     .04       0
  5121.7     .05       0  5355.2     .08       0  6990.5     .99       0
#XS Ineff= 2 , 0
       0 4897.93   64.78 5108.37       0   64.31
Permanent Ineff=
       F       F
Bank Sta=4904.6,5101.7
XS Rating Curve= 0 ,0
Exp/Cntr=0.5,0.3

Type RM Length L Ch R = 1 ,52589.0 ,683.5,812,813
BEGIN DESCRIPTION:
Cross Section E100-00-00-X36
END DESCRIPTION:
XS GIS Cut Line= 6
      3094182.96     13868792.88      3092443.38     13868915.54
       3092229.4     13868803.84       3091532.5     13868434.35
      3090876.64     13868976.87      3089878.62      13869495.4
#Sta/Elev= 30
  3020.3    74.5  3500.3    71.9  3750.3    67.6  4140.3    65.2    4608   65.23
    4864   65.67  4899.7   65.93  4931.3   53.22  4958.3   50.03  4974.9   41.58
  4992.8   41.02  4996.1   38.93    5025   41.62  5042.1   49.84  5064.3   52.77
  5095.8   63.13  5118.5   58.28  5126.7   59.13  5165.6   63.14  5295.6    65.9
  5402.7   64.14  5465.6    65.9  5705.6    64.9  5794.4    66.4  5854.4    65.1
  6645.5    71.9  6845.5    72.3  6875.5    70.7  7405.5    75.1  7770.2    74.8
#Mann= 8 ,-1 , 0
  3020.3     .08       0    4608     .05       0    4864     .04       0
  4958.3    .015       0  5042.1     .04       0  5126.7     .05       0
  5402.7     .08       0  7770.2     .99       0
Bank Sta=4899.7,5095.8
XS Rating Curve= 0 ,0
Exp/Cntr=0.3,0.1

Type RM Length L Ch R = 1 ,51777.0 ,819.2,756,472.5
BEGIN DESCRIPTION:
Cross Section E100-00-00-X35
END DESCRIPTION:
XS GIS Cut Line= 6
      3094801.85     13868586.58      3093316.34     13868501.86
      3092771.74     13868210.41      3091807.76     13867711.22
      3091098.24     13868568.67      3089421.42     13869272.38
#Sta/Elev= 30
  2894.5    77.7  3134.5    76.9  3194.5    75.1  3394.5    76.4  4764.3   65.07
  4873.7   62.44  4882.6   61.15  4906.3   63.16    4932   52.81  4957.8   49.46
  4975.2   41.04  5003.1   38.57  5007.1   40.55    5025   40.85  5042.3   49.46
  5057.6    50.2  5093.3   62.12  5108.4   59.56  5162.6    57.9  5410.1    64.8
  5709.4   63.65  5780.1      66  6335.7    64.8  6625.7    66.6  6685.7    65.2
  6815.7    67.1  7055.7    66.2  7488.6      72  8798.6    74.3  9017.1    76.8
#Mann= 8 ,-1 , 0
  2894.5     .08       0  4764.3     .05       0  4873.7     .04       0
  4957.8    .015       0  5042.3     .04       0  5108.4     .05       0
  5709.4     .08       0  9017.1     .99       0
Bank Sta=4906.3,5093.3
XS Rating Curve= 0 ,0
Exp/Cntr=0.3,0.1

Type RM Length L Ch R = 1 ,51021.  ,96.2,100,101
BEGIN DESCRIPTION:
W 43rd Street - U/S - XS 4
END DESCRIPTION:
XS GIS Cut Line= 6
      3094071.52     13867700.08      3092962.63     13867471.57
      3092770.62     13867465.66      3091972.32     13867442.77
       3091055.1     13868519.06      3089408.92     13869222.17
#Sta/Elev= 30
  3773.2   74.24  3923.2   73.89  3973.2   71.16  4133.2   72.82  4333.2   68.33
  4373.2   70.42  4673.2   67.42  4893.2   64.07  4915.4   60.08  4965.4   45.17
 4975.87   39.96 4998.07   37.55 5024.96   40.05 5042.85   48.78  5107.5   62.17
  5187.5   65.19  5507.5   63.39  5557.5   61.17  5607.5   54.49  5687.5   62.93
  5787.5   62.84  5877.5   65.75  6086.1   64.17  6776.1   66.72  6996.1   65.45
  7246.1   66.58  7590.2   71.86  7780.2   70.85  8510.2   75.52  9100.3   75.94
#Mann= 7 ,-1 , 0
  3773.2     .08       0  4673.2     .05       0  4893.2     .04       0
  4965.4    .015       0 5042.85     .04       0  5107.5     .05       0
  5787.5     .08       0
Bank Sta=4893.2,5107.5
XS Rating Curve= 0 ,0
Exp/Cntr=0.5,0.3

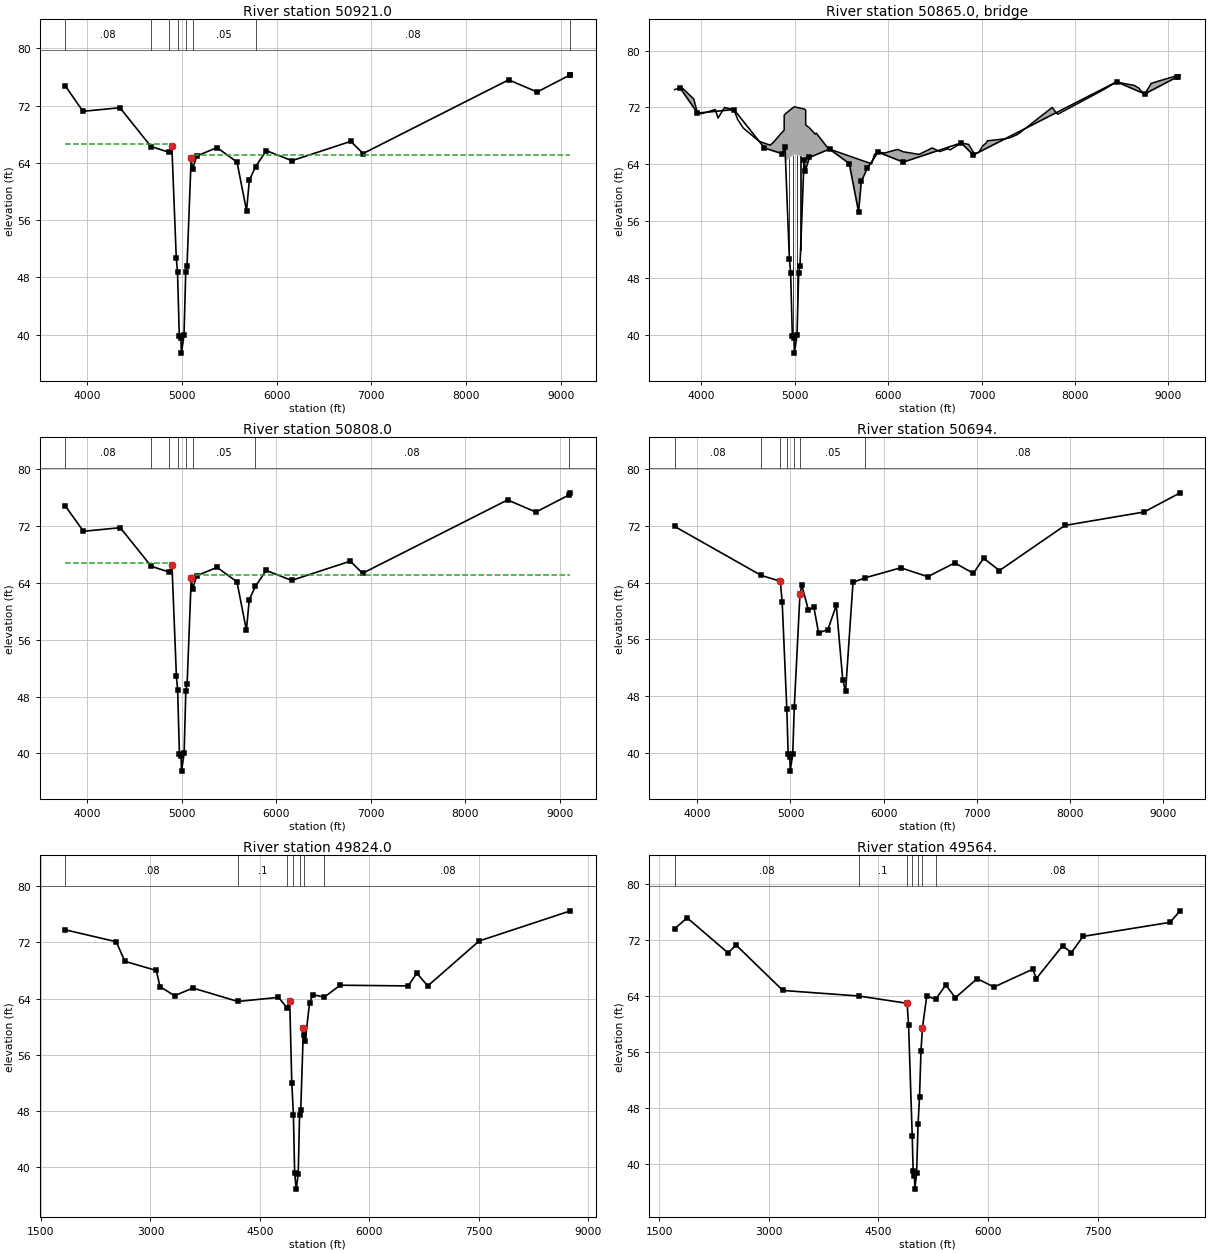
Type RM Length L Ch R = 1 ,50921.0 ,115.2,113,112
BEGIN DESCRIPTION:
Upstream Section of Bridge/Culvert/Weir
END DESCRIPTION:
XS GIS Cut Line= 6
      3094065.86     13867601.03      3092956.97     13867372.52
      3092764.96     13867366.61      3091966.66     13867343.72
      3091049.44     13868420.01      3089403.26     13869123.12
#Sta/Elev= 30
  3771.2   74.81  3959.7   71.21  4349.7   71.71  4676.9   66.29  4866.3   65.49
  4896.4   66.42  4943.3   50.72  4956.5   48.76  4975.1   39.84  4992.4   39.47
  4997.4   37.41  5024.9   39.92    5043   48.73  5056.6   49.63  5100.2   64.63
  5115.1   63.12  5157.9   64.96    5373   66.14    5584   64.11    5684   57.31
    5714   61.61  5779.2   63.47  5892.6   65.71  6162.6   64.31  6782.6   67.01
  6912.6   65.31  8446.7   75.61    8747   73.91  9096.7   76.31  9098.3   76.31
#Mann= 8 ,-1 , 0
  3771.2     .08       0  4676.9     .05       0  4866.3     .04       0
  4956.5    .015       0    5043     .04       0  5115.1     .05       0
  5779.2     .08       0  9096.7     .99       0
#XS Ineff= 2 , 0
       0  4886.4    66.7 5103.28       0   65.07
Permanent Ineff=
       F       F
Bank Sta=4896.4,5100.2
XS Rating Curve= 0 ,0
Exp/Cntr=0.5,0.3

Type RM Length L Ch R = 3 ,50865.0 ,,,
BEGIN DESCRIPTION:
W 43rd STREET
Structure ID: E100-00-00-33
END DESCRIPTION:
Bridge Culvert--1,0,-1,-1, 0
Deck Dist Width WeirC Skew NumUp NumDn MinLoCord MaxHiCord MaxSubmerge Is_Ogee
10,92,2.6,0, 144, 144, , , 0.95, 0, ,,,
  3716.2  3769.7  3786.2  3799.7  3816.2  3896.2  3919.7  3956.2  3959.7  3999.7
  4136.2  4149.7  4179.7  4186.2  4249.7  4306.2  4336.2  4349.7  4389.7  4449.7
  4619.7  4639.7  4676.9  4682.4  4738.3  4770.7  4773.1  4838.3  4851.1  4866.3
 4887.49  4887.6 4887.71  4896.4  4901.6  4901.9 4902.01  4902.1  4908.1  4925.4
  4942.7  4943.2  4943.3  4956.5  4975.1  4982.6  4992.4  4993.6  4994.1  4997.4
  5000.2  5002.7  5006.4  5007.6  5023.5  5024.9    5043  5056.6  5056.7  5063.2
  5077.6  5100.2 5103.19  5103.3  5103.4  5104.3  5115.1  5117.6 5117.69  5117.8
 5117.91  5157.9  5158.7  5214.3  5219.9  5230.6  5360.6    5373    5584    5624
    5644    5654    5664    5674    5684    5714    5734    5774  5779.2    5804
    5824    5854  5860.6  5892.6  5932.3  5962.3  6102.3  6122.6  6162.6  6332.3
  6472.6  6552.6  6642.3  6662.3  6702.3  6742.3  6782.6  6862.3  6882.6  6912.6
  6922.3  6952.6  6972.3  7012.3  7012.6  7052.3  7062.6  7092.3  7132.3  7262.6
  7306.7  7386.7    7387    7497    7587  7756.7  7796.7    7797    7817    7847
  8306.7  8446.7    8477    8637  8686.7  8706.7  8746.7    8747    8817    8967
  9036.7  9096.7  9096.8  9126.1
    74.5   74.81   74.75   74.71    74.5    73.5   73.21   71.39   71.21   71.11
   71.66   71.71   70.51   70.65   72.01   71.84   71.75   71.71   70.31   69.11
   67.23   67.14   66.97   66.95    66.7   67.07    67.1   68.12    68.3   68.51
   68.81   70.91   70.91   71.04   71.11   71.13   71.13   71.13    71.2   71.38
   71.56   71.56   71.57    71.7    71.9   71.98   72.08   72.09    72.1   72.09
   72.08   72.07   72.06   72.06   72.01   72.01   71.95   71.91   71.91   71.89
   71.85   71.78   71.77   71.77   71.77   71.78   71.67   71.64   71.64   71.64
   69.54   69.14   69.13   68.33   68.25    68.4    66.2   66.14   65.17   64.99
    64.9   64.85    64.8   64.76   64.71   64.57   64.48    64.3   64.27   64.16
   64.07   65.41   65.46   65.71   65.64   65.59    66.1   65.99   65.76    65.4
   66.31   65.79    66.2   66.02   66.35   66.68   67.01    66.8   66.36   65.71
    65.5   65.62    65.7    66.6   66.59   67.04   67.31   67.35   67.41   67.61
   67.75   68.21   68.21   69.34   70.27   72.01    71.3    71.3   71.05   71.27
   74.51   75.61    75.5    75.1   74.71   74.34    73.9    73.9    75.4      76
   76.26   76.49   76.49    76.6
                                                                                
                                                                                
                                                                                
                                                           64.69    64.5   64.68
   64.86   64.86   64.87      65    65.2   65.28   65.38   65.39    65.4   65.39
   65.38   65.37   65.36   65.36   65.31   65.31   65.25   65.21   65.21   65.19
   65.15   65.08   65.07   64.31
                                                                                
                                                                                
                                                                                
                                                                                
                                                                                
                                                                                
                                                                                
                                
  3716.2  3769.7  3786.2  3799.7  3816.2  3896.2  3919.7  3956.2  3959.7  3999.7
  4136.2  4149.7  4179.7  4186.2  4249.7  4306.2  4336.2  4349.7  4389.7  4449.7
  4619.7  4639.7  4676.9  4682.4  4738.3  4770.7  4773.1  4838.3  4851.1  4866.3
 4887.49  4887.6 4887.71  4896.4  4901.6  4901.9 4902.01  4902.1  4908.1  4925.4
  4942.7  4943.2  4943.3  4956.5  4975.1  4982.6  4992.4  4993.6  4994.1  4997.4
  5000.2  5002.7  5006.4  5007.6  5023.5  5024.9    5043  5056.6  5056.7  5063.2
  5077.6  5100.2 5103.19  5103.3  5103.4  5104.3  5115.1  5117.6 5117.69  5117.8
 5117.91  5157.9  5158.7  5214.3  5219.9  5230.6  5360.6    5373    5584    5624
    5644    5654    5664    5674    5684    5714    5734    5774  5779.2    5804
    5824    5854  5860.6  5892.6  5932.3  5962.3  6102.3  6122.6  6162.6  6332.3
  6472.6  6552.6  6642.3  6662.3  6702.3  6742.3  6782.6  6862.3  6882.6  6912.6
  6922.3  6952.6  6972.3  7012.3  7012.6  7052.3  7062.6  7092.3  7132.3  7262.6
  7306.7  7386.7    7387    7497    7587  7756.7  7796.7    7797    7817    7847
  8306.7  8446.7    8477    8637  8686.7  8706.7  8746.7    8747    8817    8967
  9036.7  9096.7  9096.8  9126.1
    74.5   74.81   74.75   74.71    74.5    73.5   73.21   71.39   71.21   71.11
   71.66   71.71   70.51   70.65   72.01   71.84   71.75   71.71   70.31   69.11
   67.23   67.14   66.97   66.95    66.7   67.07    67.1   68.12    68.3   68.51
   68.81   70.91   70.91   71.04   71.11   71.13   71.13   71.13    71.2   71.38
   71.56   71.56   71.57    71.7    71.9   71.98   72.08   72.09    72.1   72.09
   72.08   72.07   72.06   72.06   72.01   72.01   71.95   71.91   71.91   71.89
   71.85   71.78   71.77   71.77   71.77   71.78   71.67   71.64   71.64   71.64
   69.54   69.14   69.13   68.33   68.25    68.4    66.2   66.14   65.17   64.99
    64.9   64.85    64.8   64.76   64.71   64.57   64.48    64.3   64.27   64.16
   64.07   65.41   65.46   65.71   65.64   65.59    66.1   65.99   65.76    65.4
   66.31   65.79    66.2   66.02   66.35   66.68   67.01    66.8   66.36   65.71
    65.5   65.62    65.7    66.6   66.59   67.04   67.31   67.35   67.41   67.61
   67.75   68.21   68.21   69.34   70.27   72.01    71.3    71.3   71.05   71.27
   74.51   75.61    75.5    75.1   74.71   74.34    73.9    73.9    75.4      76
   76.26   76.49   76.49    76.6
                                                                                
                                                                                
                                                                                
                                                           64.69    64.5   64.68
   64.86   64.86   64.87      65    65.2   65.28   65.38   65.39    65.4   65.39
   65.38   65.37   65.36   65.36   65.31   65.31   65.25   65.21   65.21   65.19
   65.15   65.08   65.07   64.31
                                                                                
                                                                                
                                                                                
                                                                                
                                                                                
                                                                                
                                                                                
                                
Pier Skew, UpSta & Num, DnSta & Num=  ,4942.7, 2 ,4942.7, 2 , 0 , 0 , 0 ,,
       2       2
   49.65   65.87
       2       2
   49.78      66
Pier Skew, UpSta & Num, DnSta & Num=  ,4982.6, 2 ,4982.6, 2 , 0 , 0 , 0 ,,
       2       2
   38.62   66.29
       2       2
   38.75   66.42
Pier Skew, UpSta & Num, DnSta & Num=  ,5023.5, 2 ,5023.5, 2 , 0 , 0 , 0 ,,
       2       2
   38.85   66.31
       2       2
   38.98   66.44
Pier Skew, UpSta & Num, DnSta & Num=  ,5063.2, 2 ,5063.2, 2 , 0 , 0 , 0 ,,
       2       2
    51.2   66.19
       2       2
   51.33   66.32
Abutment Skew #Up #Dn= , 2 , 2
  4901.9  4943.3
   64.69   50.71
  4901.9  4943.3
   64.82   50.84
Abutment Skew #Up #Dn= , 2 , 2
  5056.7 5103.39
   49.67   65.07
  5056.7 5103.39
    49.8    65.2
BR Coef= 1 , 1 , 0 ,1.25, 0 ,,,0.8,-1,1.2,0,
WSPro=,,,, 1 ,,,, 0 ,,,, 0 ,,,,-1 ,-1 ,-1 , 0 , 0 , 0 , 0 , 0
BC Design=,, 0 ,, 0 ,,,,,,
BC HTab HWMax=76.61
BC Use User HTab Curves=0
BC User HTab FreeFlow(D)= 0

Type RM Length L Ch R = 1 ,50808.0 ,113,114,157.1
BEGIN DESCRIPTION:
Downstream Section of Bridge/Culvert/Weir
END DESCRIPTION:
XS GIS Cut Line= 6
      3094082.86     13867488.89      3092971.43     13867259.85
      3092776.79     13867253.86       3091964.1     13867230.56
      3091042.12     13868312.43      3089402.42     13869012.77
#Sta/Elev= 30
  3765.3   74.81  3959.7   71.21  4349.7   71.71  4676.9   66.29  4866.3   65.49
  4896.4   66.42  4943.3   50.83  4956.5   48.87  4975.1   39.95  4992.4   39.58
  4997.4   37.52  5024.9   40.03    5043   48.84  5056.6   49.74  5100.2   64.63
  5115.1   63.12  5157.9   64.96    5373   66.14    5584   64.11    5684   57.31
    5714   61.61  5779.2   63.47  5892.6   65.71  6162.6   64.31  6782.6   67.01
  6912.6   65.31  8446.7   75.61    8747   73.91  9096.7   76.31  9112.3   76.61
#Mann= 8 ,-1 , 0
  3765.3     .08       0  4676.9     .05       0  4866.3     .04       0
  4956.5    .015       0    5043     .04       0  5115.1     .05       0
  5779.2     .08       0  9096.7     .99       0
#XS Ineff= 2 , 0
       0 4889.73    66.7 5103.28       0   65.06
Permanent Ineff=
       F       F
Bank Sta=4896.4,5100.2
XS Rating Curve= 0 ,0
Exp/Cntr=0.5,0.3

Type RM Length L Ch R = 1 ,50694.  ,933.5,870,224.5
BEGIN DESCRIPTION:
W 43rd Street - D/S - XS 1
END DESCRIPTION:
XS GIS Cut Line= 6
      3094088.52     13867387.01      3092982.73     13867133.42
      3092782.45     13867151.99      3091969.76     13867128.68
       3090988.5     13868334.39      3089392.66     13868995.72
#Sta/Elev= 30
  3756.4    71.9  4686.4      65  4890.9   64.19  4910.9   61.27  4960.9   46.16
 4975.35   39.85 4992.42   39.47 4997.35   37.44 5024.49   39.91  5040.9   46.41
    5102   62.39    5122   63.62    5192   60.16    5252    60.5    5302    56.9
    5402   57.38    5492   60.79    5562   50.28    5592   48.69    5672   64.03
    5802   64.67  6185.1   66.08  6475.1   64.83  6765.1   66.77  6965.1    65.3
  7075.1   67.43  7245.1   65.69  7949.6   72.05  8799.6   73.94  9187.1   76.64
#Mann= 7 ,-1 , 0
  3756.4     .08       0  4686.4     .05       0  4890.9     .04       0
  4960.9    .015       0  5040.9     .04       0    5102     .05       0
    5802     .08       0
Bank Sta=4890.9,5102
XS Rating Curve= 0 ,0
Exp/Cntr=0.3,0.1

Type RM Length L Ch R = 1 ,49824.0 ,47,260,317.2
BEGIN DESCRIPTION:
Cross Section E100-00-00-X34
END DESCRIPTION:
XS GIS Cut Line= 6
      3094952.39     13867109.06      3093391.23     13866317.32
      3092487.98     13866311.75      3092178.31     13866736.65
      3090986.85     13868333.28      3089360.09     13868982.45
#Sta/Elev= 30
  1830.4    73.8  2530.4    72.1  2650.4    69.3  3080.4      68  3130.4    65.7
  3330.4    64.4  3580.8    65.5  4197.4   63.58  4753.9   64.17  4869.9   62.69
  4907.5   63.72  4936.1   51.98  4958.4    47.4  4975.3   39.12    4997   36.84
  5024.5   39.06  5042.5   47.35  5058.5   48.08  5095.5   59.79  5104.9   58.76
  5120.2   57.97  5179.8    63.4    5225   64.54  5382.4   64.21  5599.3    65.9
  6529.3    65.8  6649.3    67.6  6799.3    65.8  7502.1    72.2  8753.6    76.5
#Mann= 7 ,-1 , 0
  1830.4     .08       0  4197.4      .1       0  4869.9     .04       0
  4958.4    .015       0  5042.5     .04       0  5104.9     .05       0
  5382.4     .08       0
Bank Sta=4907.5,5095.5
XS Rating Curve= 0 ,0
Exp/Cntr=0.3,0.1

Type RM Length L Ch R = 1 ,49564.  ,67.6,107,121.9
BEGIN DESCRIPTION:
PL_33a - U/S - XS 4
END DESCRIPTION:
XS GIS Cut Line= 6
      3095017.46     13867094.51      3093448.33      13866283.6
      3092501.17     13866269.94      3091868.22     13866643.34
        3090798.     13868077.13      3089333.71     13868899.18
#Sta/Elev= 30
  1710.5   73.65  1880.5    75.2  2440.5   70.17  2550.5    71.3  3190.5    64.8
  4226.8   64.01  4891.9   62.96  4911.9   59.86  4961.9   43.97 4974.51   38.91
 4992.37   38.29 4997.36   36.36 5021.87   38.65  5041.9   45.66  5061.9   49.62
  5081.9   56.18  5101.9   59.48  5161.5   64.04  5281.5   63.52  5421.5   65.59
  5551.5   63.76  5851.5   66.49  6081.5   65.29  6611.5   67.84  6661.5   66.51
  7020.7    71.2  7140.7   70.21  7300.7   72.54  8490.7   74.55  8629.9    76.2
#Mann= 7 ,-1 , 0
  1710.5     .08       0  4226.8      .1       0  4891.9     .04       0
  4961.9    .015       0  5041.9     .04       0  5101.9     .05       0
  5281.5     .08       0
Bank Sta=4891.9,5101.9
XS Rating Curve= 0 ,0
Exp/Cntr=0.5,0.3

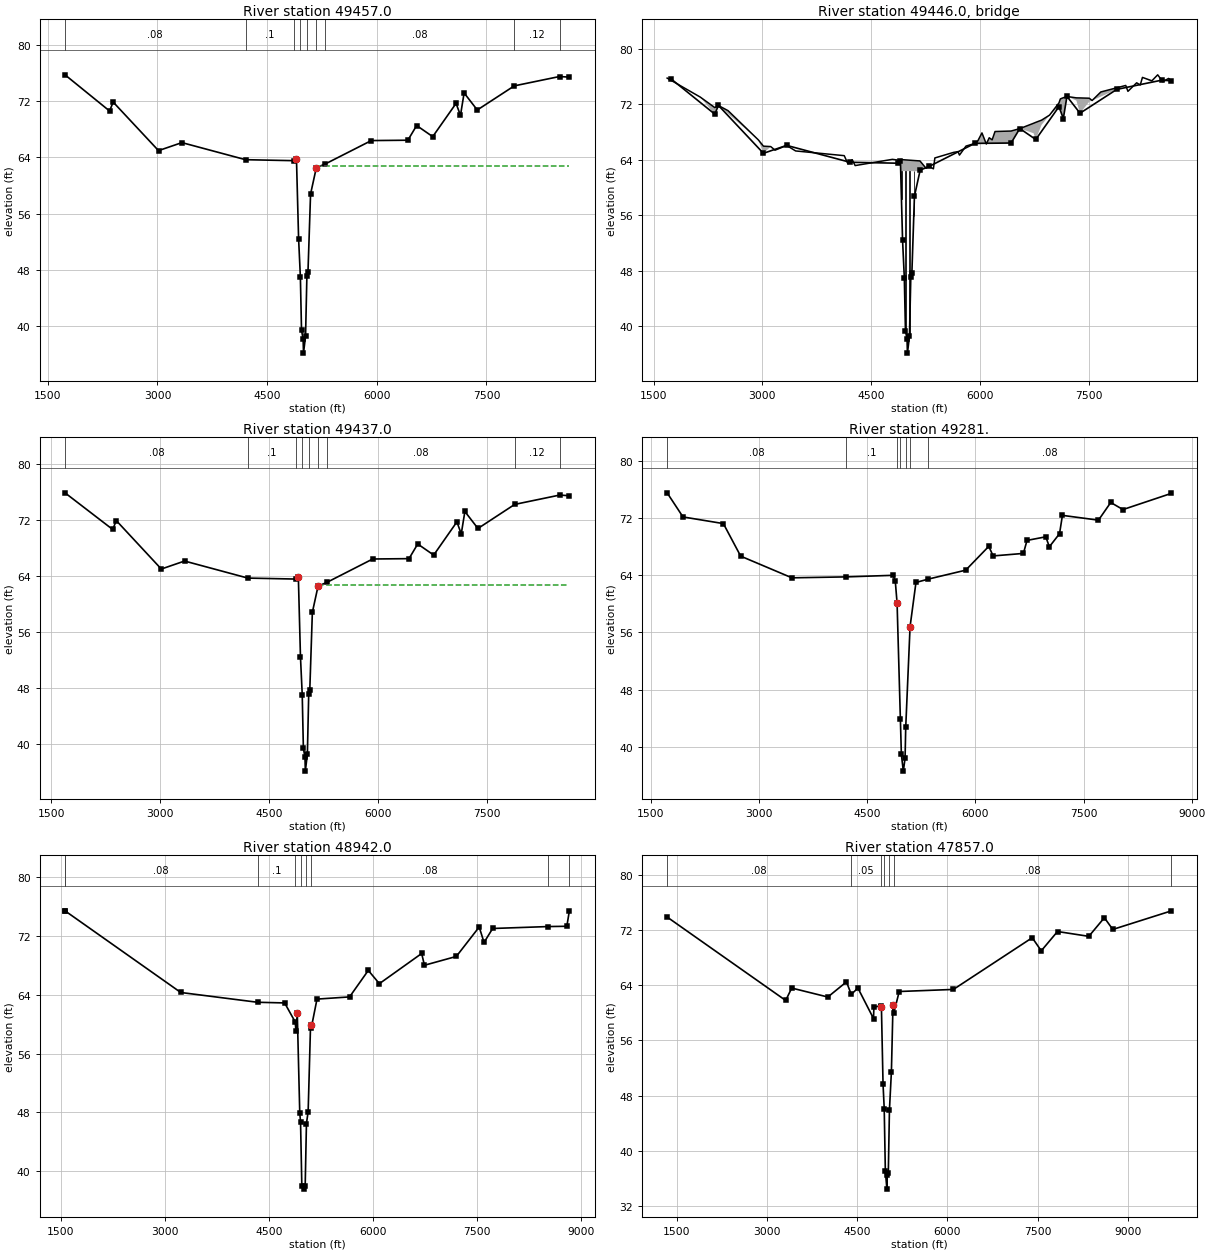
Type RM Length L Ch R = 1 ,49457.0 ,22.9,20,19
BEGIN DESCRIPTION:
Upstream Section of Bridge/Culvert/Weir
END DESCRIPTION:
XS GIS Cut Line= 6
      3094972.19     13867003.95      3093437.25     13866220.43
      3092467.48     13866214.01      3091754.66     13866601.45
      3090752.72     13867986.57      3089288.43     13868808.62
#Sta/Elev= 30
  1734.8   75.74    2344    70.6    2394   71.86    3014   64.96    3334    66.1
  4205.2   63.67  4871.3   63.53 4901.31   63.78 4930.41   52.46 4954.71   47.03
 4970.41   39.42 4992.41   38.15 4997.51   36.16 5025.61   38.59 5043.91   47.12
 5058.71   47.69 5094.11   58.78 5172.81   62.53  5296.7   63.07  5925.4   66.39
  6425.4   66.44  6545.4   68.53  6765.4   66.95  7084.9   71.68  7144.9   69.97
  7194.9   73.16  7374.9   70.74  7881.3   74.17  8500.3    75.5    8635   75.41
#Mann= 9 ,-1 , 0
  1734.8     .08       0  4205.2      .1       0  4871.3     .04       0
 4954.71    .015       0 5043.91     .04       0 5172.81     .05       0
  5296.7     .08       0  7881.3     .12       0  8500.3     .99       0
#XS Ineff= 2 , 0
       0 4891.31   63.13 5182.81       0   62.72
Permanent Ineff=
       F       F
Bank Sta=4901.31,5172.81
XS Rating Curve= 0 ,0
Exp/Cntr=0.5,0.3

Type RM Length L Ch R = 3 ,49446.0 ,,,
BEGIN DESCRIPTION:
PL1_E100-00-00-33a
END DESCRIPTION:
Bridge Culvert--1,0,-1,-1, 0
Deck Dist Width WeirC Skew NumUp NumDn MinLoCord MaxHiCord MaxSubmerge Is_Ogee
10,2,2.6,0, 60, 60, , , 0.95, 0, ,,,
  1687.4    2144    2344    2394  2527.4    2944    3014    3114    3174    3334
  3457.3  4127.3  4177.3  4237.3  4277.3 4791.21 4901.31 4905.12 5170.01  5254.2
 5286.21  5355.4  5375.4  5635.4  5694.2  5714.2  5804.2  5925.4  5965.4  6024.2
  6084.2  6124.2  6164.2  6204.2  6425.4  6545.4  6735.4  6765.4  6845.4  6954.9
  7084.9  7104.2  7124.9  7144.9  7194.9  7324.9  7374.9  7501.6  7541.6  7661.6
  8004.9  8034.9  8154.9  8204.9  8234.9  8364.9  8444.9  8514.9  8594.9  8634.2
    75.8   73.06   71.55   71.85    71.1   66.89   65.99   65.93   65.41   66.09
    65.3   64.62   63.45   64.03   63.19   64.09   63.93   64.06   63.86    62.8
   63.14   62.72   64.29    65.1    65.2    64.7      66   66.38   66.72    67.9
    66.3    67.2    66.9    68.1   68.17   68.52   69.29   69.42   69.74   70.46
   72.22    72.8   72.89   72.97   73.15   72.95   72.94    72.9   72.57    73.8
   74.74   73.89   75.12   74.81    75.9   75.41   76.27   75.28   75.75   75.39
    75.8   73.05   70.58   71.84   70.64   66.88   64.94   65.92   65.37   66.08
   65.29   64.61   63.32   64.02    63.1   64.08   63.76   62.41   62.37   62.77
   63.13   62.63   64.28   65.09   64.53   64.69   65.41   66.37   65.43   66.03
   66.27   66.29    66.3   66.32   66.42   68.51   67.85   66.93   69.06   70.45
   71.66   70.82   69.91   69.95   73.14   72.56   70.72   72.38   72.56   73.13
   74.73   73.88   75.11    74.8   75.89      75   76.26   75.28   75.75   75.39
  1687.4    2144    2344    2394  2527.4    2944    3014    3114    3174    3334
  3457.3  4127.3  4177.3  4237.3  4277.3 4791.21 4901.31 4905.12 5170.01  5254.2
 5286.21  5355.4  5375.4  5635.4  5694.2  5714.2  5804.2  5925.4  5965.4  6024.2
  6084.2  6124.2  6164.2  6204.2  6425.4  6545.4  6735.4  6765.4  6845.4  6954.9
  7084.9  7104.2  7124.9  7144.9  7194.9  7324.9  7374.9  7501.6  7541.6  7661.6
  8004.9  8034.9  8154.9  8204.9  8234.9  8364.9  8444.9  8514.9  8594.9  8634.2
    75.8   73.06   71.55   71.85    71.1   66.89   65.99   65.93   65.41   66.09
    65.3   64.62   63.45   64.03   63.19   64.09   63.93   64.06   63.86    62.8
   63.14   62.72   64.29    65.1    65.2    64.7      66   66.38   66.72    67.9
    66.3    67.2    66.9    68.1   68.17   68.52   69.29   69.42   69.74   70.46
   72.22    72.8   72.89   72.97   73.15   72.95   72.94    72.9   72.57    73.8
   74.74   73.89   75.12   74.81    75.9   75.41   76.27   75.28   75.75   75.39
    75.8   73.05   70.58   71.84   70.64   66.88   64.94   65.92   65.37   66.08
   65.29   64.61   63.32   64.02    63.1   64.08   63.76   62.41   62.37   62.77
   63.13   62.63   64.28   65.09   64.53   64.69   65.41   66.37   65.43   66.03
   66.27   66.29    66.3   66.32   66.42   68.51   67.85   66.93   69.06   70.45
   71.66   70.82   69.91   69.95   73.14   72.56   70.72   72.38   72.56   73.13
   74.73   73.88   75.11    74.8   75.89      75   76.26   75.28   75.75   75.39
Pier Skew, UpSta & Num, DnSta & Num=  ,4915.3, 2 ,4915.3, 2 , 0 , 0 , 0 ,,
     1.5     1.5
   57.51   63.55
     1.5     1.5
   57.51   63.55
Pier Skew, UpSta & Num, DnSta & Num=  ,4970.4, 2 ,4970.4, 2 , 0 , 0 , 0 ,,
     1.5     1.5
   38.28   63.51
     1.5     1.5
   38.28   63.51
Pier Skew, UpSta & Num, DnSta & Num=  ,5025.6, 2 ,5025.6, 2 , 0 , 0 , 0 ,,
     1.5     1.5
   37.55   63.47
     1.5     1.5
   37.55   63.47
Pier Skew, UpSta & Num, DnSta & Num=  ,5085, 2 ,5085, 2 , 0 , 0 , 0 ,,
     1.5     1.5
   54.04   63.42
     1.5     1.5
   54.04   63.42
BR Coef= 1 , 1 , 0 ,1.25, 0 ,,,0.8,-1,2,0,
WSPro=,,,, 1 ,,,, 0 ,,,, 0 ,,,,-1 ,-1 ,-1 , 0 , 0 , 0 , 0 , 0
BC Design=,, 0 ,, 0 ,,,,,,
BC HTab HWMax=76.28
BC Use User HTab Curves=0
BC User HTab FreeFlow(D)= 0

Type RM Length L Ch R = 1 ,49437.0 ,116.2,156,244.6
BEGIN DESCRIPTION:
Downstream Section of Bridge/Culvert/Weir
END DESCRIPTION:
XS GIS Cut Line= 6
      3094989.15     13866987.75      3093447.88       13866201.
      3092465.04     13866194.49      3091736.28     13866590.78
       3090735.6     13867974.16      3089277.07     13868792.98
#Sta/Elev= 30
  1687.4   75.83    2344   70.61    2394   71.87    3014   64.97    3334   66.11
  4205.2   63.68  4871.3   63.54 4901.31   63.79 4930.41   52.47 4954.71   47.04
 4970.41   39.43 4992.41   38.16 4997.51   36.17 5025.61    38.6 5043.91   47.13
 5058.71    47.7 5094.11   58.79 5172.81   62.54  5296.7   63.08  5925.4    66.4
  6425.4   66.45  6545.4   68.54  6765.4   66.96  7084.9   71.69  7144.9   69.98
  7194.9   73.17  7374.9   70.75  7881.3   74.18  8500.3   75.51  8634.2   75.42
#Mann= 9 ,-1 , 0
  1687.4     .08       0  4205.2      .1       0  4871.3     .04       0
 4954.71    .015       0 5043.91     .04       0 5172.81     .05       0
  5296.7     .08       0  7881.3     .12       0  8500.3     .99       0
#XS Ineff= 2 , 0
       0 4894.64   63.13 5179.48       0   62.72
Permanent Ineff=
       F       F
Bank Sta=4901.31,5172.81
XS Rating Curve= 0 ,0
Exp/Cntr=0.5,0.3

Type RM Length L Ch R = 1 ,49281.  ,134,339,380
BEGIN DESCRIPTION:
PL_33a - D/S - XS 1
END DESCRIPTION:
XS GIS Cut Line= 6
      3094960.85      13866888.7      3093419.58     13866101.95
      3092436.74     13866095.44      3091745.27     13866306.37
       3090707.3     13867875.11      3089248.77     13868693.94
#Sta/Elev= 30
  1725.2   75.51  1945.2   72.14  2505.2   71.21  2745.2   66.66  3455.7   63.63
  4205.7   63.76  4858.5   63.98  4888.5   63.25  4914.2    60.1    4960   43.85
 4973.63   38.94 5000.82   36.61 5024.82    38.4  5034.2   42.76  5094.2    56.8
    5176   62.98    5346   63.45    5866    64.7    6186   68.03    6246   66.69
    6666   67.04    6716   68.86    6976   69.36    7026   67.97    7167    69.8
    7207   72.36    7707   71.69    7877   74.16    8047   73.17  8719.7   75.44
#Mann= 7 ,-1 , 0
  1725.2     .08       0  4205.7      .1       0  4914.2     .04       0
    4960    .015       0  5034.2     .04       0  5094.2     .05       0
    5346     .08       0
Bank Sta=4914.2,5094.2
XS Rating Curve= 0 ,0
Exp/Cntr=0.3,0.1

Type RM Length L Ch R = 1 ,48942.0 ,913.5,1085,1086
BEGIN DESCRIPTION:
Cross Section E100-00-00-X33
END DESCRIPTION:
XS GIS Cut Line= 6
      3095164.26       13866847.      3093536.19     13866032.97
      3091918.93     13865942.79      3091724.13     13865932.61
      3090323.54     13867911.14       3089198.4     13868374.71
#Sta/Elev= 30
    1560    75.4  1560.1    75.4  3230.1    64.3  4337.2   62.97  4728.4   62.88
  4880.7    60.3  4891.6   59.07  4910.8   61.47  4946.5   47.94  4957.9   46.69
  4976.5   37.98    5008   37.57  5024.8   38.02    5043   46.48  5067.6   48.12
  5102.2   59.83  5112.2   59.46  5195.2    63.4  5665.2    63.7  5935.2    67.3
  6095.2    65.5  6705.2    69.6  6745.2      68  7205.2    69.2  7535.2    73.2
  7605.2    71.1  7729.3      73  8523.1   73.26  8799.3    73.3  8836.2    75.4
#Mann= 9 ,-1 , 0
    1560     .99       0  1560.1     .08       0  4337.2      .1       0
  4880.7     .04       0  4957.9    .015       0    5043     .04       0
  5112.2     .08       0  8523.1     .12       0  8836.2     .99       0
Bank Sta=4910.8,5102.2
XS Rating Curve= 0 ,0
Exp/Cntr=0.3,0.1

Type RM Length L Ch R = 1 ,47857.0 ,612.3,1030,1330.8
BEGIN DESCRIPTION:
Cross Section E100-00-00-X32
END DESCRIPTION:
XS GIS Cut Line= 6
      3095253.47     13866400.96      3092214.65     13864870.47
      3091958.23     13864858.11       3091801.7      13864846.3
      3090076.45     13867716.18       3088969.8     13868218.59
#Sta/Elev= 30
  1343.4    73.9  3313.4    61.8  3413.4    63.6  4013.4    62.3  4323.4    64.5
  4402.7   62.68  4513.4    63.6  4772.4   59.18  4778.9   60.81  4897.3   61.07
  4903.8   60.87  4930.9   49.65  4950.4   46.11    4969   37.11  4994.6   34.44
  5001.5   36.51  5018.3   36.76  5037.1    45.9  5069.8   51.48  5096.2   61.12
  5109.6   59.97  5199.6    63.1  6099.6    63.4  7409.6    70.9  7559.6      69
  7829.6    71.8  8349.6    71.1  8608.1    73.8  8748.1    72.1  9723.5    74.8
#Mann= 7 ,-1 , 0
  1343.4     .08       0  4402.7     .05       0  4897.3     .04       0
  4950.4    .015       0  5037.1     .04       0  5109.6     .08       0
  9723.5     .99       0
Bank Sta=4903.8,5096.2
XS Rating Curve= 0 ,0
Exp/Cntr=0.3,0.1