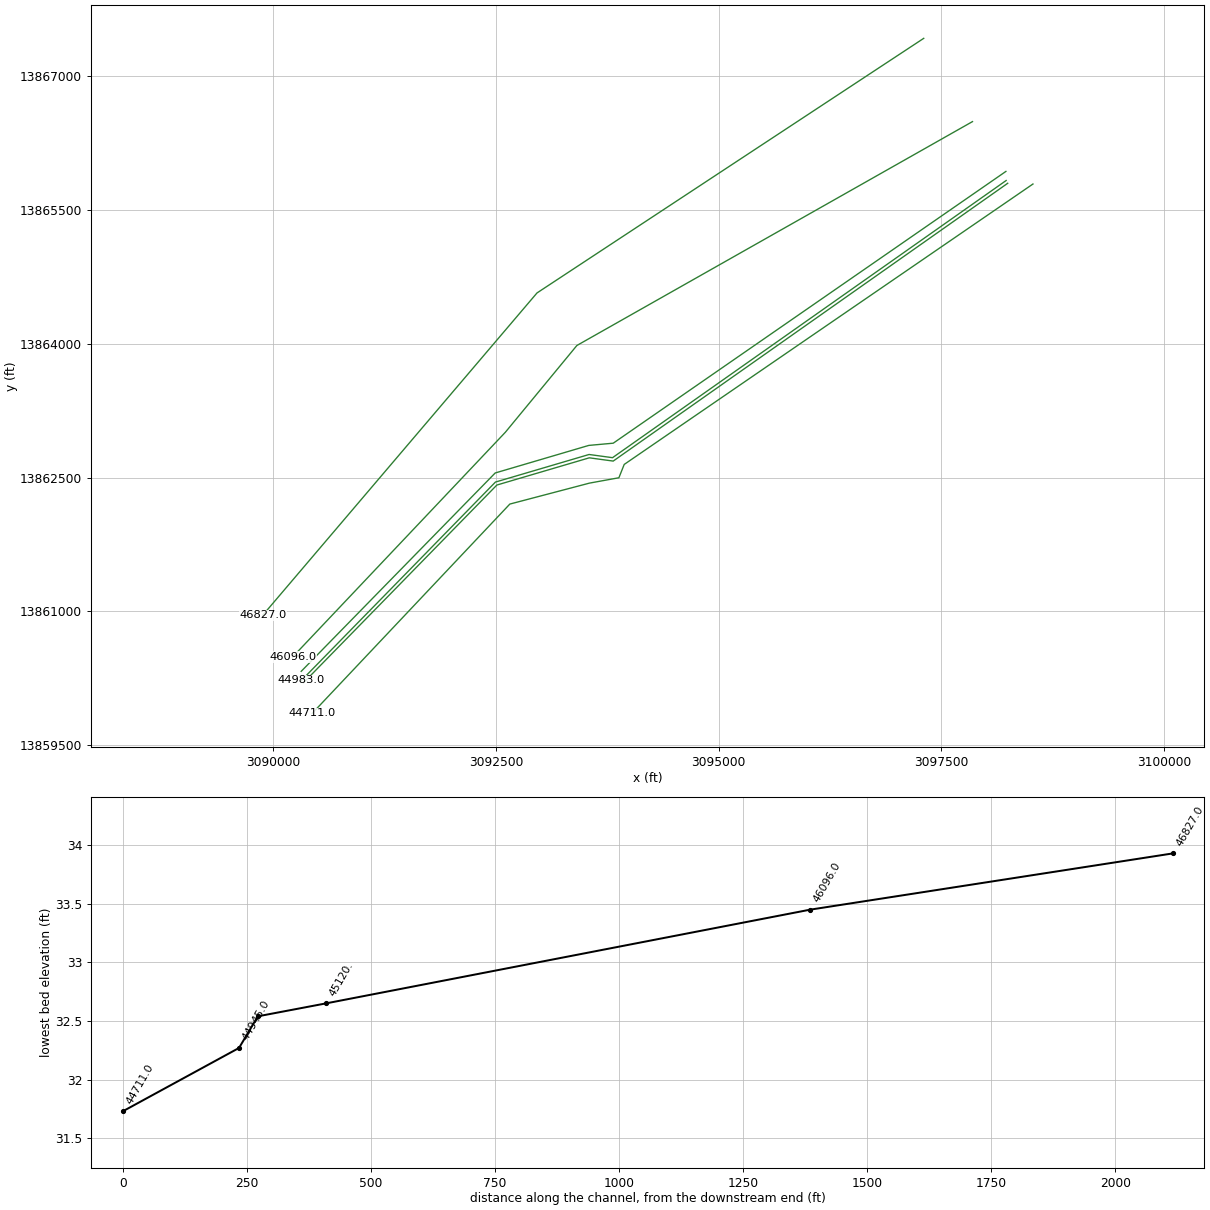
HEC-RAS study E100-00-00.prj: E100-00-00

--- E100-00-00.g02 (geometry) --- (continued)

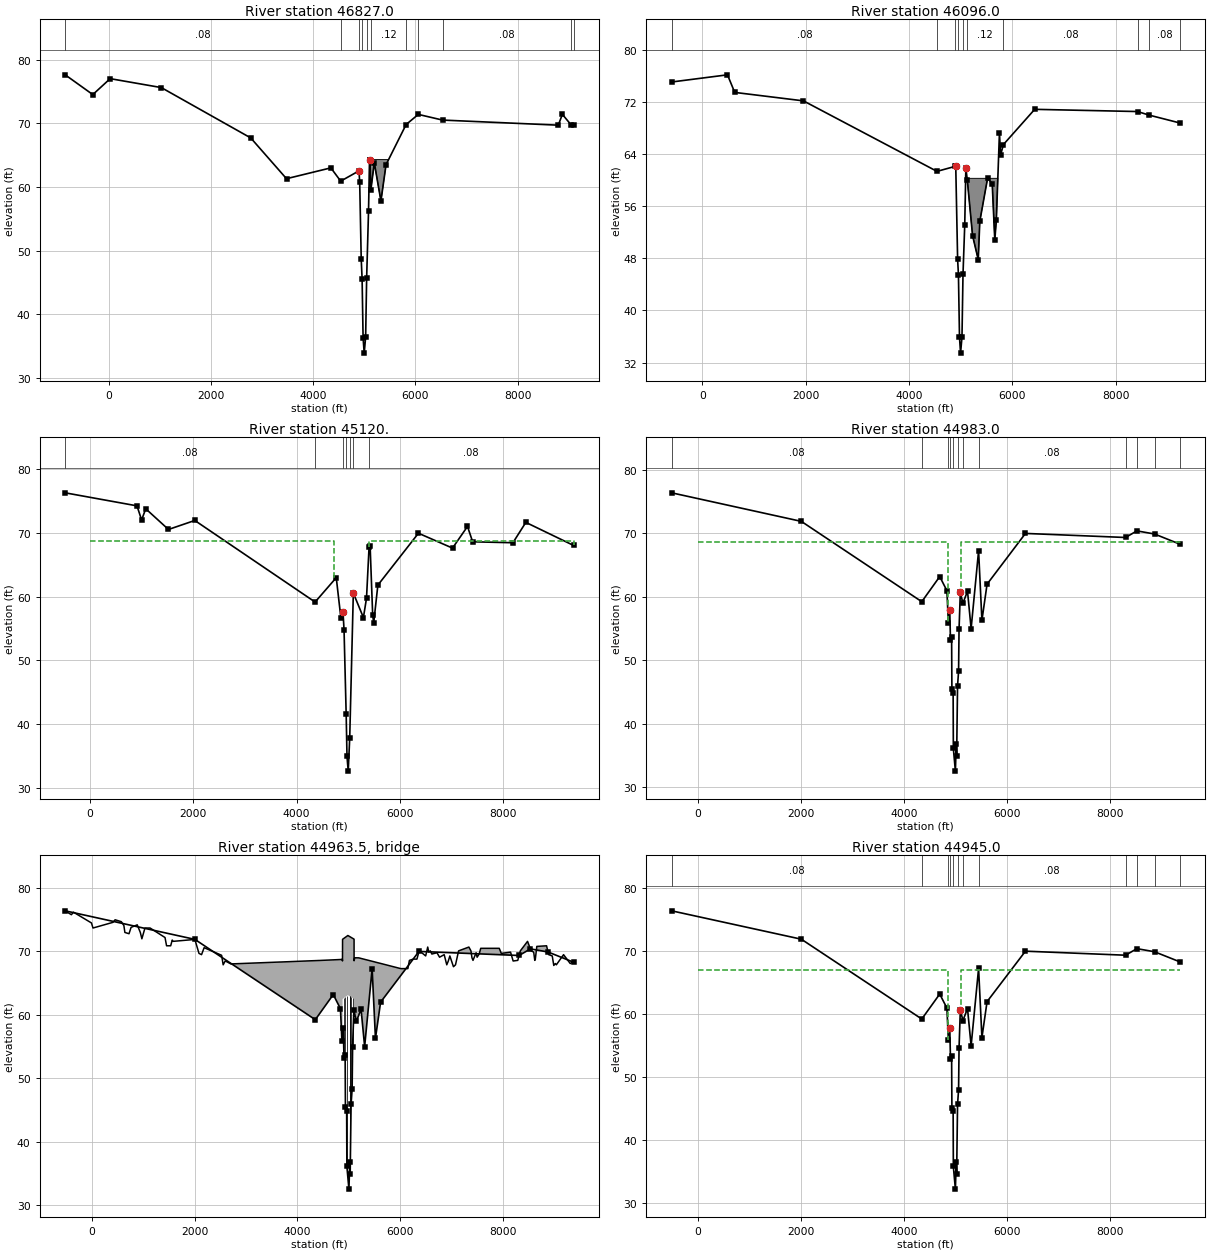
Type RM Length L Ch R = 1 ,46827.0 ,768.5,731,730
BEGIN DESCRIPTION:
Cross Section E100-00-00-X31
END DESCRIPTION:
XS GIS Cut Line= 3
      3097302.07     13867426.39      3092959.29      13864570.4
      3089880.02     13860955.68
#Sta/Elev= 30
  -853.6    77.6  -313.6    74.5    26.4      77  1026.4    75.6  2776.4    67.7
  3476.4    61.3  4344.1      63    4537   60.92  4894.9   62.53  4908.5   60.73
  4938.5   48.66  4955.5   45.62  4974.9   36.35  4996.7   33.93  5024.9   36.47
  5044.3   45.65  5081.3   56.19  5100.7   64.28  5109.4    64.3  5126.1   59.48
  5194.1    63.8  5324.1    57.8  5424.1    63.5  5816.6    69.8  6055.4   71.39
  6529.2    70.5  8794.1    69.7  8874.1    71.4  9043.3   69.76  9092.6    69.7
#Mann= 11 ,-1 , 0
  -853.6     .08       0    4537     .05       0  4894.9     .04       0
  4955.5    .015       0  5044.3     .04       0  5126.1     .12       0
  5816.6     .08       0  6055.4     .12       0  6529.2     .08       0
  9043.3     .05       0  9092.6     .99       0
#Block Obstruct= 2 ,-1
  5105.8  5478.4    64.3  5478.9  5479.9    59.9
Bank Sta=4894.9,5100.7
XS Rating Curve= 0 ,0
Exp/Cntr=0.3,0.1

Type RM Length L Ch R = 1 ,46096.0 ,1212.3,976,736.9
BEGIN DESCRIPTION:
Cross Section E100-00-00-X30
END DESCRIPTION:
XS GIS Cut Line= 4
      3097849.57     13866492.42      3093407.06       13863981.
      3092603.56     13863007.32      3090215.49     13860487.38
#Sta/Elev= 30
  -593.8    75.1   486.2    76.2   626.2    73.5  1956.2    72.2    4541   61.37
  4897.3   62.15  4903.6   62.26  4940.1   47.84  4955.9   45.51  4976.1   35.89
  4996.9   33.45  5024.4   35.91    5044   45.54  5077.8   53.17  5099.2   61.87
  5127.5   60.03  5229.4    51.5  5339.4    47.8  5369.4    53.7  5519.4    60.3
  5609.4    59.5  5659.4    50.8  5689.4    53.9  5749.4    67.3  5771.8    63.9
  5826.1   65.49  6431.8    70.9  8422.2   70.56    8647   70.01  9243.6    68.8
#Mann= 10 ,-1 , 0
  -593.8     .08       0    4541     .05       0  4897.3     .04       0
  4955.9    .015       0    5044     .04       0  5127.5     .12       0
  5826.1     .08       0  8422.2     .05       0    8647     .08       0
  9243.6     .99       0
#Block Obstruct= 2 ,-1
  5101.9  5737.9    60.3  5738.9  5739.9    59.9
Bank Sta=4903.6,5099.2
XS Rating Curve= 0 ,0
Exp/Cntr=0.3,0.1

Type RM Length L Ch R = 1 ,45120.  ,162.9,137,102.6
BEGIN DESCRIPTION:
Burlington Northern RR - U/S - XS 4
END DESCRIPTION:
XS GIS Cut Line= 5
      3098224.76     13865933.57      3093815.29      13862885.1
      3093541.33     13862860.27      3092489.81     13862550.94
      3090311.41     13860325.94
#Sta/Elev= 30
  -481.9   76.25   908.1   74.21   998.1      72  1078.1   73.75  1518.1   70.51
  2028.1   71.92  4358.1   59.14  4768.1   62.96  4858.1   56.62  4898.7   57.54
  4918.7   54.82    4960   41.59 4975.91   34.95 4999.88   32.65  5028.7   37.85
  5098.7   60.55  5293.8   56.71  5353.8   59.73  5403.8   67.78  5423.8   67.94
  5473.8   57.04  5493.8    55.9  5573.8   61.79  6359.9   69.92  7019.9   67.59
  7309.9   70.98  7409.9   68.58  8189.9   68.43  8439.9   71.62  9363.8   68.01
#Mann= 7 ,-1 , 0
  -481.9     .08       0  4358.1     .05       0  4898.7     .04       0
    4960    .015       0  5028.7     .04       0  5098.7     .12       0
  5403.8     .08       0
#XS Ineff= 2 , 0
       0    4730    68.7    5411       0    68.7
Permanent Ineff=
       F       F
Bank Sta=4898.7,5098.7
XS Rating Curve= 0 ,0
Exp/Cntr=0.5,0.3

Type RM Length L Ch R = 1 ,44983.0 ,49.4,38,36.5
BEGIN DESCRIPTION:
Upstream Section of Bridge/Culvert/Weir
END DESCRIPTION:
XS GIS Cut Line= 5
      3098227.59     13865831.69      3093807.38     13862722.49
      3093544.16     13862758.39      3092492.64     13862449.06
      3090314.24     13860224.06
#Sta/Elev= 30
    -514   76.41    2006   71.91    4347   59.25    4696   63.21  4835.6   60.98
  4864.1   55.85  4890.8   57.87  4904.8    53.2  4926.8   53.65  4932.4   45.45
  4956.5   44.86  4960.6   36.14  5000.3   32.54  5016.7   36.87  5024.6   34.87
  5042.2   45.99  5062.4   48.28  5071.2   54.87  5096.2   60.71  5146.3      59
  5235.9   60.91  5305.9   55.01  5451.2   67.27  5515.9   56.31  5615.9   62.01
  6361.9   70.01  8307.3   69.37    8528   70.41  8870.3   69.92  9365.8   68.31
#Mann= 12 ,-1 , 0
    -514     .08       0    4347     .05       0  4864.1     .12       0
  4890.8     .04       0  4956.5    .015       0  5042.2     .04       0
  5146.3     .12       0  5451.2     .08       0  8307.3     .05       0
    8528      .1       0  8870.3     .08       0  9365.8     .99       0
#XS Ineff= 2 , 0
       0    4866    68.7    5109       0    68.7
Permanent Ineff=
       F       F
Bank Sta=4890.8,5096.2
XS Rating Curve= 0 ,0
Exp/Cntr=0.5,0.3

Type RM Length L Ch R = 3 ,44963.5 ,,,
BEGIN DESCRIPTION:
BURLINGTON NORTHERN RAILROAD
Structure ID: E100-00-00-32
END DESCRIPTION:
Bridge Culvert--1,0,-1,-1, 0
Deck Dist Width WeirC Skew NumUp NumDn MinLoCord MaxHiCord MaxSubmerge Is_Ogee
10,19,2.6,0, 178, 178, , , 0.95, 0, ,,,
    -514    -394    -354      -4      26     416     456     576     626     646
     726     766     886     946     976    1036    1136    1426    1456    1536
    1566    1586    2006    2086    2136    2186    2526    2556  2571.8    2596
    2706    2856    3256    3286    3576    3596    3626    3656    3696    3956
    4216    4296    4326    4347    4386    4406    4436    4446    4656    4696
  4785.1  4818.9  4825.5  4835.6  4848.3  4862.8  4864.1  4871.7  4871.8 4875.19
  4875.3 4875.41 4876.61  4876.7  4890.8  4904.8  4926.8  4932.4    4947  4956.5
  4960.6  4975.9    4980  4992.9  4993.1  4996.9  5000.3  5003.2    5007  5007.3
  5013.4  5016.7  5024.6  5042.2  5045.3  5054.1  5062.4  5071.2  5080.3  5096.2
 5098.99  5099.1 5100.29  5100.4 5100.51  5112.8  5112.9  5137.5  5146.3  5172.1
  5190.1  5195.9  5235.9  5295.9  5305.9  5325.9  5355.9  5375.9  5415.9  5435.9
  5445.9  5451.2  5455.9  5475.9  5505.9  5515.9  5555.9  5565.9  5575.9  5595.9
  5615.9  5785.9  5865.9  5895.9  6009.1  6145.9  6175.9  6251.9  6321.9  6361.9
  6401.9  6491.9  6531.9  6551.9  6581.9  6611.9  6711.9  6761.9  6851.9  6901.9
  6931.9  6961.9  7031.9  7071.9  7131.9  7331.9  7371.9  7391.9  7411.9  7471.9
  7491.9  7531.9  7561.9  7921.9  7961.9  8141.9  8191.9  8281.9  8307.3  8331.9
  8471.9    8528  8541.9  8591.9  8611.9  8621.9  8651.9  8841.9  8870.3  8881.9
  8951.9  8981.9  9011.9  9031.9  9171.9  9301.9  9361.9  9365.8
    76.4    75.8    76.2    74.5    73.7    74.6      75    74.7    74.1      73
    72.8    73.8    74.2      73      72    73.7    73.7    72.2    70.9    70.9
    71.8    71.6    71.9    69.7    69.5    70.6    69.4    67.9   68.15   68.51
   68.04   68.09   68.22   68.22   68.32   68.32   68.33   68.34   68.35   68.44
   68.52   68.54   68.55   68.56   68.57   68.58   68.59   68.59   68.66   68.67
    68.7   68.71   68.71   68.72   68.74   68.76   68.76   68.77   68.76   68.51
   71.91   71.91   71.92   71.92      72   72.08   72.21   72.24   72.33   72.38
   72.41    72.5   72.52   72.46   72.46   72.44   72.42   72.41   72.39   72.39
   72.36   72.34    72.3   72.22   72.21   72.16   72.12   72.08   72.04   71.96
   71.95   71.95   71.94   71.94   68.54   69.01   69.01   69.01   69.01      69
      69   68.99    68.9   68.78   68.76   68.72   68.66   68.61   68.53   68.49
   68.47   68.46   68.45   68.41   68.34   68.32   68.24   68.22    68.2   68.16
   68.12   67.76    67.6   67.53    67.3    67.3    68.6    68.8    68.8      70
    69.9    69.3    70.7    69.9    70.1    69.6    69.8    69.1    69.5    67.9
    68.5    69.3    67.6    67.9    70.1    70.7    70.1      69    68.6    69.8
    69.1    69.6    70.5    70.5    69.7    69.9    68.5    68.6   69.36    70.1
    71.6    70.4    70.1    69.9    68.6    68.7    70.8    70.9   69.91    69.5
    69.3    67.8    68.1    67.9    69.5    68.1    68.4    68.3
                                                                                
                                                                                
                                                                                
                                                                                
                                                                                
                                                                                
                           62.51   62.59   62.67    62.8   62.83   62.92   62.97
      63   63.09   63.11   63.05   63.05   63.03   63.01      63   62.98   62.98
   62.95   62.93   62.89   62.81    62.8   62.75   62.71   62.67   62.63   62.55
   62.54
                                                                                
                                                                                
                                                                                
                                                                                
                                                                                
                                                                                
                                                                                
                                                                
    -514    -394    -354      -4      26     416     456     576     626     646
     726     766     886     946     976    1036    1136    1426    1456    1536
    1566    1586    2006    2086    2136    2186    2526    2556  2571.8    2596
    2706    2856    3256    3286    3576    3596    3626    3656    3696    3956
    4216    4296    4326    4347    4386    4406    4436    4446    4656    4696
  4785.1  4818.9  4825.5  4835.6  4848.3  4862.8  4864.1  4871.7  4871.8 4875.19
  4875.3 4875.41 4876.61  4876.7  4890.8  4904.8  4926.8  4932.4    4947  4956.5
  4960.6  4975.9    4980  4992.9  4993.1  4996.9  5000.3  5003.2    5007  5007.3
  5013.4  5016.7  5024.6  5042.2  5045.3  5054.1  5062.4  5071.2  5080.3  5096.2
 5098.99  5099.1 5100.29  5100.4 5100.51  5112.8  5112.9  5137.5  5146.3  5172.1
  5190.1  5195.9  5235.9  5295.9  5305.9  5325.9  5355.9  5375.9  5415.9  5435.9
  5445.9  5451.2  5455.9  5475.9  5505.9  5515.9  5555.9  5565.9  5575.9  5595.9
  5615.9  5785.9  5865.9  5895.9  6009.1  6145.9  6175.9  6251.9  6321.9  6361.9
  6401.9  6491.9  6531.9  6551.9  6581.9  6611.9  6711.9  6761.9  6851.9  6901.9
  6931.9  6961.9  7031.9  7071.9  7131.9  7331.9  7371.9  7391.9  7411.9  7471.9
  7491.9  7531.9  7561.9  7921.9  7961.9  8141.9  8191.9  8281.9  8307.3  8331.9
  8471.9    8528  8541.9  8591.9  8611.9  8621.9  8651.9  8841.9  8870.3  8881.9
  8951.9  8981.9  9011.9  9031.9  9171.9  9301.9  9361.9  9365.8
    76.4    75.8    76.2    74.5    73.7    74.6      75    74.7    74.1      73
    72.8    73.8    74.2      73      72    73.7    73.7    72.2    70.9    70.9
    71.8    71.6    71.9    69.7    69.5    70.6    69.4    67.9   68.15   68.51
   68.04   68.09   68.22   68.22   68.32   68.32   68.33   68.34   68.35   68.44
   68.52   68.54   68.55   68.56   68.57   68.58   68.59   68.59   68.66   68.67
    68.7   68.71   68.71   68.72   68.74   68.76   68.76   68.77   68.76   68.51
   71.91   71.91   71.92   71.92      72   72.08   72.21   72.24   72.33   72.38
   72.41    72.5   72.52   72.46   72.46   72.44   72.42   72.41   72.39   72.39
   72.36   72.34    72.3   72.22   72.21   72.16   72.12   72.08   72.04   71.96
   71.95   71.95   71.94   71.94   68.54   69.01   69.01   69.01   69.01      69
      69   68.99    68.9   68.78   68.76   68.72   68.66   68.61   68.53   68.49
   68.47   68.46   68.45   68.41   68.34   68.32   68.24   68.22    68.2   68.16
   68.12   67.76    67.6   67.53    67.3    67.3    68.6    68.8    68.8      70
    69.9    69.3    70.7    69.9    70.1    69.6    69.8    69.1    69.5    67.9
    68.5    69.3    67.6    67.9    70.1    70.7    70.1      69    68.6    69.8
    69.1    69.6    70.5    70.5    69.7    69.9    68.5    68.6   69.36    70.1
    71.6    70.4    70.1    69.9    68.6    68.7    70.8    70.9   69.91    69.5
    69.3    67.8    68.1    67.9    69.5    68.1    68.4    68.3
                                                                                
                                                                                
                                                                                
                                                                                
                                                                                
                                                                                
                           62.51   62.59   62.67    62.8   62.83   62.92   62.97
      63   63.09   63.11   63.05   63.05   63.03   63.01      63   62.98   62.98
   62.95   62.93   62.89   62.81    62.8   62.75   62.71   62.67   62.63   62.55
   62.54
                                                                                
                                                                                
                                                                                
                                                                                
                                                                                
                                                                                
                                                                                
                                                                
Pier Skew, UpSta & Num, DnSta & Num=  ,4904.8, 2 ,4904.8, 2 , 0 , 0 , 0 ,,
     1.3     1.3
   52.19   63.67
     1.3     1.3
   51.96   63.44
Pier Skew, UpSta & Num, DnSta & Num=  ,4932.4, 2 ,4932.4, 2 , 0 , 0 , 0 ,,
     1.3     1.3
   44.48   63.83
     1.3     1.3
   44.25    63.6
Pier Skew, UpSta & Num, DnSta & Num=  ,4960.6, 2 ,4960.6, 2 , 0 , 0 , 0 ,,
     1.3     1.3
   35.06      64
     1.3     1.3
   34.83   63.77
Pier Skew, UpSta & Num, DnSta & Num=  ,5013.4, 2 ,5013.4, 2 , 0 , 0 , 0 ,,
     1.3     1.3
   34.54   63.95
     1.3     1.3
   34.31   63.72
Pier Skew, UpSta & Num, DnSta & Num=  ,5016.7, 2 ,5016.7, 2 , 0 , 0 , 0 ,,
     1.3     1.3
   35.62   63.93
     1.3     1.3
   35.39    63.7
Pier Skew, UpSta & Num, DnSta & Num=  ,5042.2, 2 ,5042.2, 2 , 0 , 0 , 0 ,,
     1.3     1.3
   44.56   63.81
     1.3     1.3
   44.33   63.58
Pier Skew, UpSta & Num, DnSta & Num=  ,5071.2, 2 ,5071.2, 2 , 0 , 0 , 0 ,,
     1.3     1.3
   53.36   63.67
     1.3     1.3
   53.13   63.44
BR Coef= 1 , 1 , 0 ,1.25, 0 ,,,0.8,-1,1.2,0,
WSPro=,,,, 1 ,,,, 0 ,,,, 0 ,,,,-1 ,-1 ,-1 , 0 , 0 , 0 , 0 , 0
BC Design=,, 0 ,, 0 ,,,,,,
BC HTab HWMax=76.41
BC Use User HTab Curves=0
BC User HTab FreeFlow(D)= 0

Type RM Length L Ch R = 1 ,44945.0 ,217.2,234,275.6
BEGIN DESCRIPTION:
Downstream Section of Bridge/Culvert/Weir
END DESCRIPTION:
XS GIS Cut Line= 5
      3098244.85     13865800.38        3093815.      13862684.4
      3093546.46     13862721.02      3092508.61     13862415.71
      3090335.68      13860196.3
#Sta/Elev= 30
    -514   76.41    2006   71.91    4347   59.25    4696   63.21  4835.6   60.98
  4864.1   55.85  4890.8   57.87  4904.8   52.93  4926.8   53.38  4932.4   45.18
  4956.5   44.59  4960.6   35.87  5000.3   32.27  5016.7    36.6  5024.6    34.6
  5042.2   45.72  5062.4   48.01  5071.2    54.6  5096.2   60.71  5146.3      59
  5235.9   60.91  5305.9   55.01  5451.2   67.27  5515.9   56.31  5615.9   62.01
  6361.9   70.01  8307.3   69.37    8528   70.41  8870.3   69.92  9365.8   68.31
#Mann= 12 ,-1 , 0
    -514     .08       0    4347     .05       0  4864.1     .12       0
  4890.8     .04       0  4956.5    .015       0  5042.2     .04       0
  5146.3     .12       0  5451.2     .08       0  8307.3     .05       0
    8528      .1       0  8870.3     .08       0  9365.8     .99       0
#XS Ineff= 2 , 0
       0    4866      67    5109       0      67
Permanent Ineff=
       F       F
Bank Sta=4890.8,5096.2
XS Rating Curve= 0 ,0
Exp/Cntr=0.5,0.3

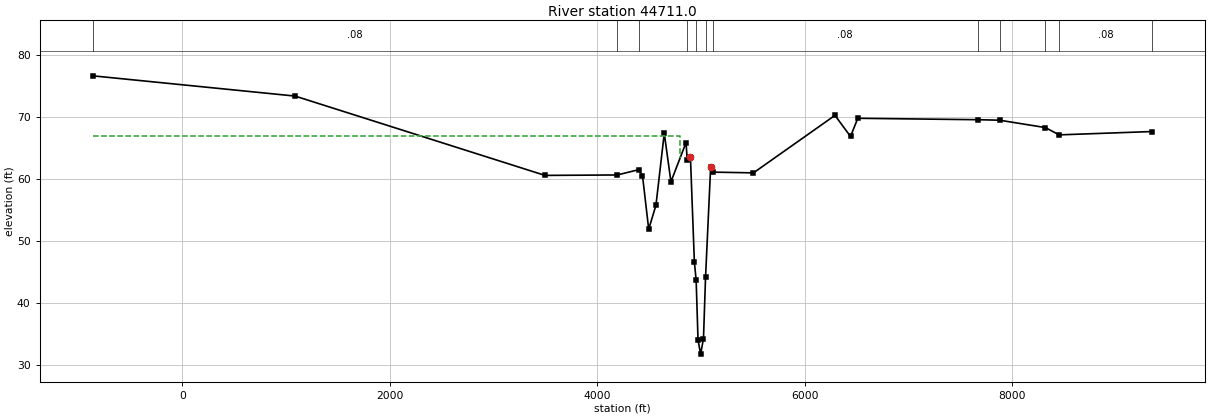
Type RM Length L Ch R = 1 ,44711.0 ,22.3,23,23.2
BEGIN DESCRIPTION:
Upstream Section of Bridge/Culvert/Weir
END DESCRIPTION:
XS GIS Cut Line= 6
      3098528.67     13865792.41      3093938.62     13862646.88
       3093878.8     13862497.32      3093549.77     13862437.49
      3092654.18     13862202.24      3090434.82     13859854.42
#Sta/Elev= 30
  -862.9    76.7  1087.1   73.43  3497.1   60.61  4193.9   60.68  4399.8   61.53
  4437.1   60.59  4497.1   51.91  4567.1    55.8  4647.1   67.42  4711.5   59.58
 4857.28   65.92  4868.4   63.07 4899.48   63.61 4937.48   46.63 4954.58   43.65
 4972.58   34.04 4997.48   31.73 5025.28   34.25 5045.08   44.14 5094.48   62.01
  5114.4   61.14    5507   61.02    6293   70.31    6443    66.9    6513   69.84
  7667.2   69.61  7879.6   69.53  8321.1   68.34  8454.9   67.16  9353.8    67.7
#Mann= 12 ,-1 , 0
  -862.9     .08       0  4193.9     .05       0  4399.8     .12       0
  4868.4     .04       0 4954.58    .015       0 5045.08     .04       0
  5114.4     .08       0  7667.2     .05       0  7879.6     .08       0
  8321.1      .1       0  8454.9     .08       0  9353.8     .99       0
#XS Ineff= 2 ,-1
  -862.9    4800      67 5094.44  9353.8   61.98
Permanent Ineff=
       T       F
Bank Sta=4899.48,5094.48
XS Rating Curve= 0 ,0
Exp/Cntr=0.5,0.3