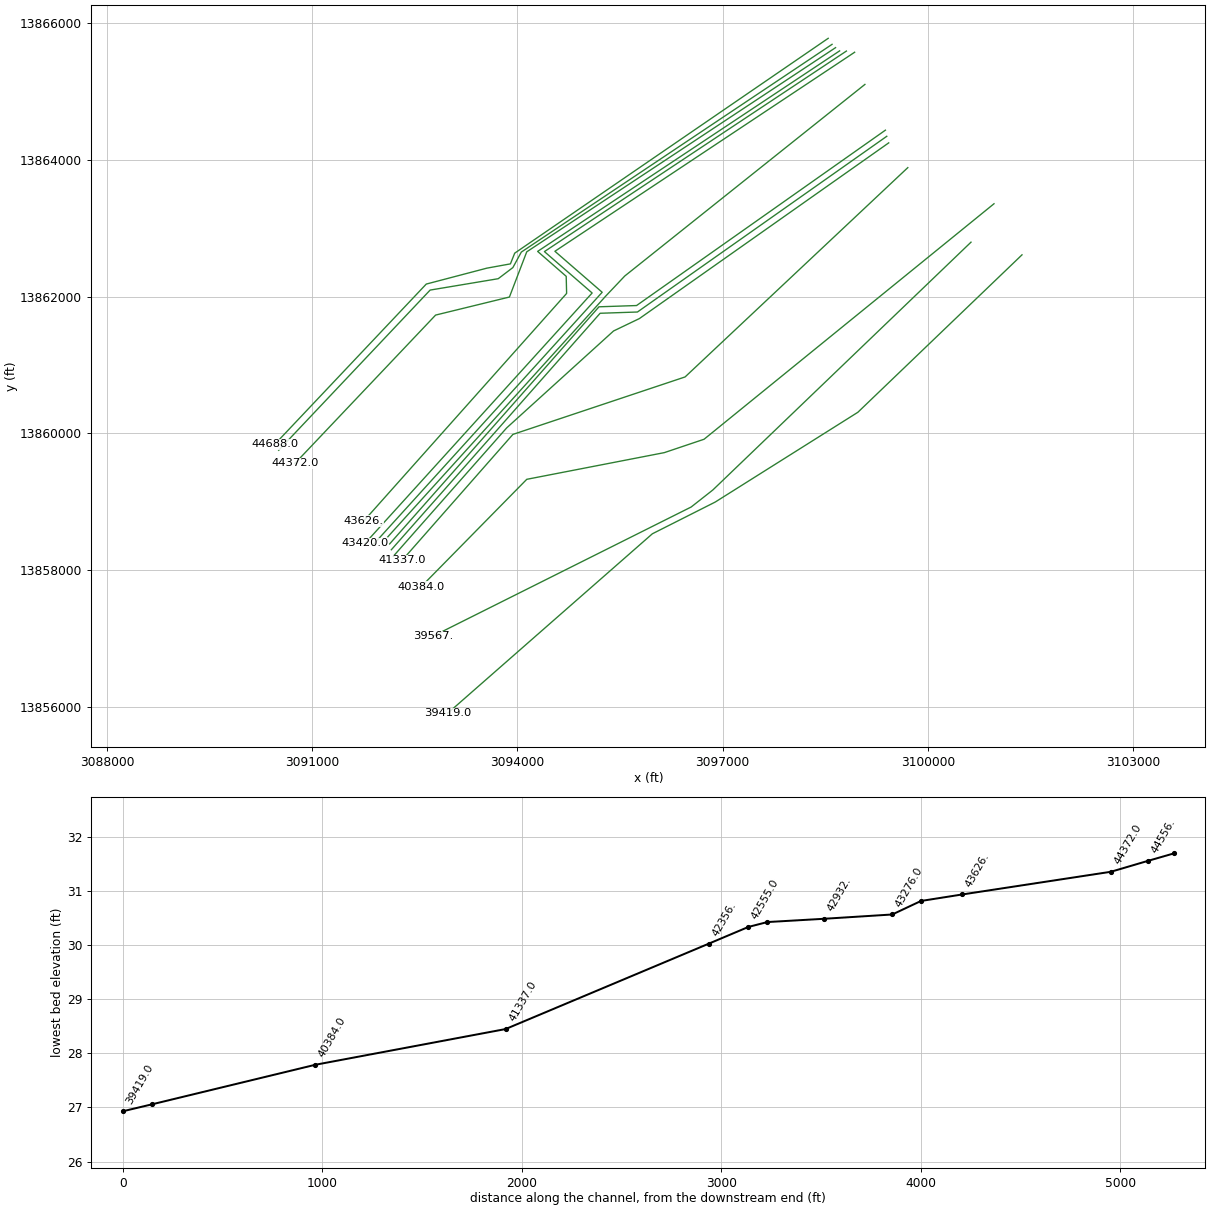
HEC-RAS study E100-00-00.prj: E100-00-00

--- E100-00-00.g02 (geometry) --- (continued)

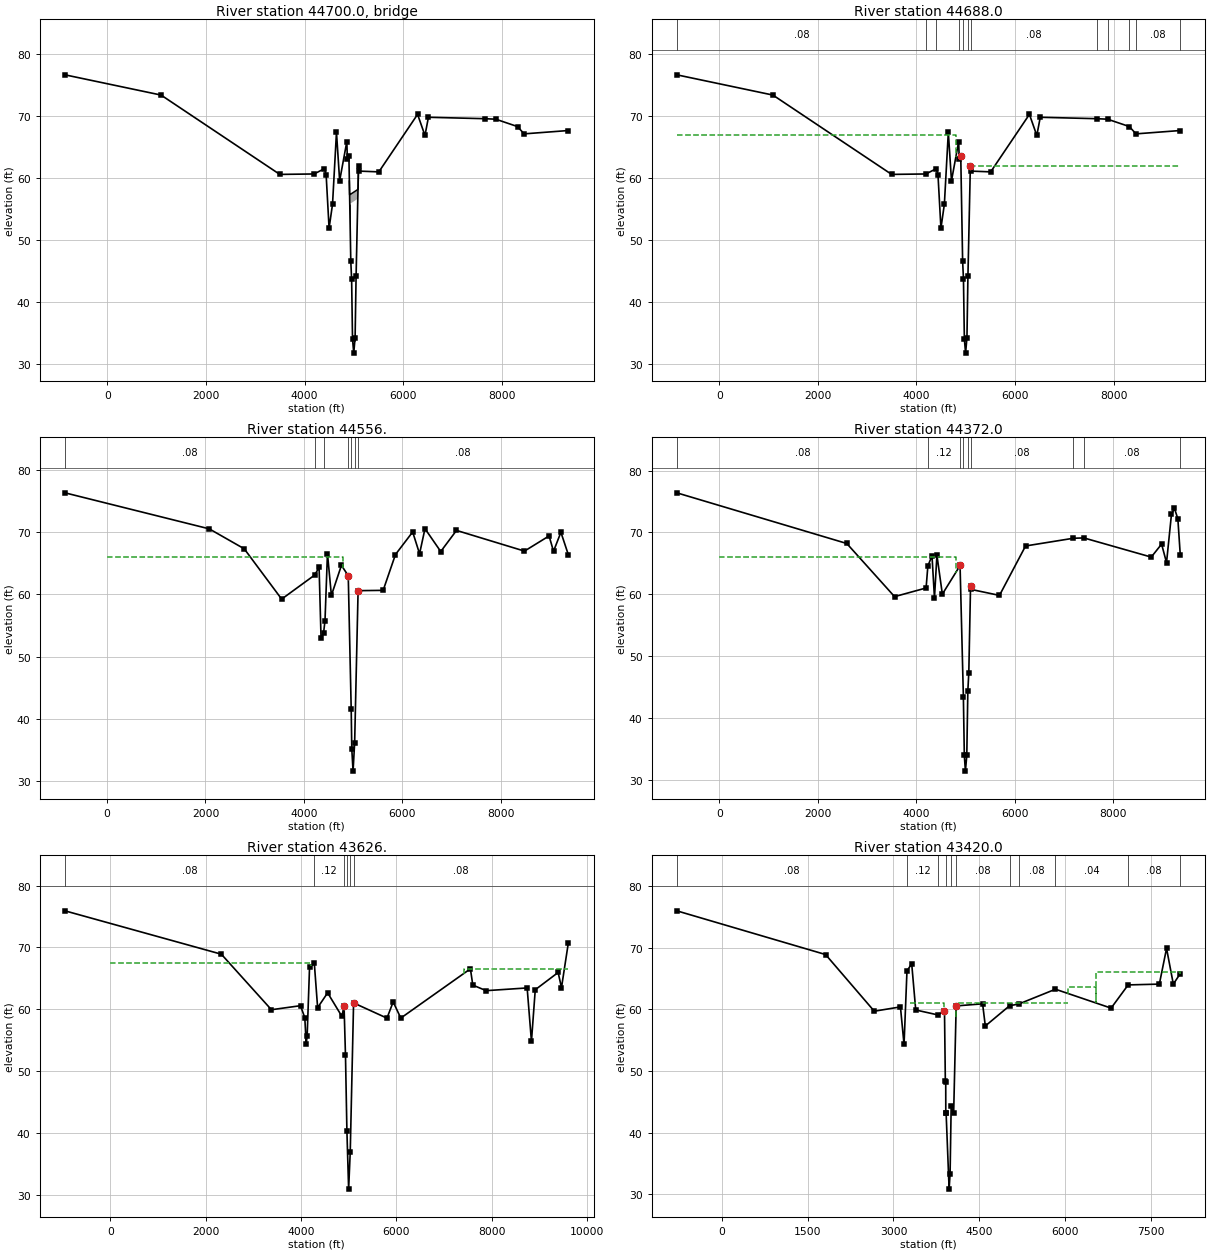
Type RM Length L Ch R = 3 ,44700.0 ,,,
BEGIN DESCRIPTION:
PL1_E100-00-00-31a
END DESCRIPTION:
Bridge Culvert--1,0,-1,-1, 0
Deck Dist Width WeirC Skew NumUp NumDn MinLoCord MaxHiCord MaxSubmerge Is_Ogee
10,2,2.6,0, 22, 22, , , 0.95, 0, ,,,
 4908.48 4913.38 4916.89 4916.98 4919.78 4928.58 4937.48 4954.58 4972.58 4990.98
 4997.48 5000.58 5003.88 5009.08 5025.28 5045.08 5059.68 5072.48 5083.17 5083.28
 5087.38  5093.1
   59.52   57.33   57.32   57.32   57.34   57.38   57.43   57.52   57.61   57.71
   57.74   57.76   57.78    57.8   57.89   57.99   58.07   58.13   58.19   58.19
    58.6   61.32
                           55.82   55.84   55.88   55.93   56.02   56.11   56.21
   56.24   56.26   56.28    56.3   56.39   56.49   56.57   56.63   56.69
                
 4908.48 4913.38 4916.89 4916.98 4919.78 4928.58 4937.48 4954.58 4972.58 4990.98
 4997.48 5000.58 5003.88 5009.08 5025.28 5045.08 5059.68 5072.48 5083.17 5083.28
 5087.38  5093.1
   59.52   57.33   57.32   57.32   57.34   57.38   57.43   57.52   57.61   57.71
   57.74   57.76   57.78    57.8   57.89   57.99   58.07   58.13   58.19   58.19
    58.6   61.32
                           55.82   55.84   55.88   55.93   56.02   56.11   56.21
   56.24   56.26   56.28    56.3   56.39   56.49   56.57   56.63   56.69
                
Pier Skew, UpSta & Num, DnSta & Num=  ,4928.6, 2 ,4928.6, 2 , 0 , 0 , 0 ,,
      .7      .7
   49.27   56.88
      .7      .7
   49.27   56.88
Pier Skew, UpSta & Num, DnSta & Num=  ,5072.5, 2 ,5072.5, 2 , 0 , 0 , 0 ,,
      .7      .7
   50.32   57.63
      .7      .7
   50.32   57.63
BR Coef= 1 , 1 , 0 ,1.25, 0 ,,,0.8,-1,2,0,
WSPro=,,,, 1 ,,,, 0 ,,,, 0 ,,,,-1 ,-1 ,-1 , 0 , 0 , 0 , 0 , 0
BR U #Sta/Elev= 30
  -862.9    76.7  1087.1   73.43  3497.1   60.61  4193.9   60.68  4399.8   61.53
  4437.1   60.59  4497.1   51.91  4567.1    55.8  4647.1   67.42  4711.5   59.58
 4857.28   65.92  4868.4   63.07 4899.48   63.61 4937.48   46.63 4954.58   43.65
 4972.58   34.04 4997.48   31.73 5025.28   34.25 5045.08   44.14 5094.48   62.01
  5114.4   61.14    5507   61.02    6293   70.31    6443    66.9    6513   69.84
  7667.2   69.61  7879.6   69.53  8321.1   68.34  8454.9   67.16  9353.8    67.7
BR U #Mann= 11
  -862.9     .08  4193.9     .05  4399.8     .12  4868.4     .04 4954.58    .015
 5045.08     .04  5114.4     .08  7667.2     .05  7879.6     .08  8321.1      .1
  8454.9     .08
BC Design=,, 0 ,, 0 ,,,,,,
BC HTab HWMax=76.7
BC Use User HTab Curves=0
BC User HTab FreeFlow(D)= 0

Type RM Length L Ch R = 1 ,44688.0 ,95.5,132,190.7
BEGIN DESCRIPTION:
Downstream Section of Bridge/Culvert/Weir
END DESCRIPTION:
XS GIS Cut Line= 6
      3098542.05     13865774.83      3093959.51     13862634.44
      3093896.91     13862477.93      3093552.69     13862415.35
      3092666.51     13862182.57      3090453.04     13859840.98
#Sta/Elev= 30
  -862.9   76.67  1087.1    73.4  3497.1   60.58  4193.9   60.65  4399.8    61.5
  4437.1   60.56  4497.1   51.88  4567.1   55.77  4647.1   67.39  4711.5   59.55
 4857.28   65.89  4868.4   63.04 4899.48   63.58 4937.48    46.6 4954.58   43.62
 4972.58   34.01 4997.48    31.7 5025.28   34.22 5045.08   44.11 5094.48   61.98
  5114.4   61.11    5507   60.99    6293   70.28    6443   66.87    6513   69.81
  7667.2   69.58  7879.6    69.5  8321.1   68.31  8454.9   67.13  9353.8   67.67
#Mann= 12 ,-1 , 0
  -862.9     .08       0  4193.9     .05       0  4399.8     .12       0
  4868.4     .04       0 4954.58    .015       0 5045.08     .04       0
  5114.4     .08       0  7667.2     .05       0  7879.6     .08       0
  8321.1      .1       0  8454.9     .08       0  9353.8     .99       0
#XS Ineff= 2 ,-1
  -862.9    4800      67 5094.44  9353.8   61.98
Permanent Ineff=
       T       F
Bank Sta=4899.48,5094.48
XS Rating Curve= 0 ,0
Exp/Cntr=0.5,0.3

Type RM Length L Ch R = 1 ,44556.  ,146.5,184,338.9
BEGIN DESCRIPTION:
PL_31a - D/S - XS 1
END DESCRIPTION:
XS GIS Cut Line= 6
      3098598.65      13865687.1      3094056.24     13862650.33
      3093932.68     13862423.79       3093718.5      13862261.1
      3092723.11     13862094.84      3090509.64     13859753.25
#Sta/Elev= 30
  -852.7   76.36  2077.3   70.56  2787.3   67.35  3547.3   59.25  4217.3   63.12
  4307.3   64.35  4347.3   52.95  4397.3   53.75  4427.3   55.75  4477.3   66.59
  4557.3   59.85  4761.3   64.69  4899.4   63.01  4959.4   41.55 4971.23   35.13
 4997.28   31.56  5029.4   36.15  5099.4   60.61  5608.3   60.66  5858.3   66.43
  6207.5   70.06  6347.5   66.55  6457.5   70.59  6777.5   66.91  7097.5   70.31
  8477.5   66.98  8977.5   69.42  9067.5   66.95  9217.5   70.01  9369.7   66.37
#Mann= 7 ,-1 , 0
  -852.7     .08       0  4217.3     .05       0  4397.3     .12       0
  4899.4     .04       0  4959.4    .015       0  5029.4     .04       0
  5099.4     .08       0
#XS Ineff= 2 , 0
       0    4800      66               0
Permanent Ineff=
       F       F
Bank Sta=4899.4,5099.4
XS Rating Curve= 0 ,0
Exp/Cntr=0.3,0.1

Type RM Length L Ch R = 1 ,44372.0 ,747,746,597
BEGIN DESCRIPTION:
Cross Section E100-00-00-X29
END DESCRIPTION:
XS GIS Cut Line= 5
      3098649.92     13865638.64       3094135.4     13862653.93
      3093882.47     13861993.24      3092803.33     13861729.39
       3090746.8     13859561.01
#Sta/Elev= 30
  -861.1    76.4  2588.9    68.2  3558.9    59.6  4198.9      61    4235   64.57
  4318.9    66.2  4368.9    59.4  4418.9    66.3  4528.9      60  4887.1   64.61
  4888.2    64.7  4955.9   43.38    4975    33.9    4997   31.36    5025    33.9
  5046.4   44.38    5066    47.3  5101.2   61.26  5110.5   60.77  5688.3    59.8
  6218.3    67.8  7190.2   69.05    7402    69.1  8769.3      66  8979.3    68.1
  9079.3    65.1  9179.3    72.9  9239.3    73.9  9309.3    72.2  9357.8    66.4
#Mann= 9 ,-1 , 0
  -861.1     .08       0    4235     .12       0  4887.1     .04       0
  4955.9    .015       0  5046.4     .04       0  5110.5     .08       0
  7190.2     .05       0    7402     .08       0  9357.8     .99       0
#XS Ineff= 2 , 0
       0    4800      66               0
Permanent Ineff=
       T       F
Bank Sta=4888.2,5101.2
XS Rating Curve= 0 ,0
Exp/Cntr=0.3,0.1

Type RM Length L Ch R = 1 ,43626.  ,85.5,206,268.6
BEGIN DESCRIPTION:
TC Jester_3 - U/S - XS 4
END DESCRIPTION:
XS GIS Cut Line= 5
      3098709.16     13865591.58      3094294.72     13862660.26
      3094712.36     13862295.85      3094718.32     13862045.65
      3091753.82     13858720.02
#Sta/Elev= 30
  -951.6   75.91  2328.4    68.9  3378.4   59.93  3988.4   60.58  4078.4   58.64
  4108.4   54.41  4128.4   55.76  4178.4   66.86  4278.4   67.41  4347.5   60.26
  4557.5   62.66  4857.5   58.84  4901.7   60.57  4931.7   52.59  4961.7   40.34
  4997.9   30.94  5031.7   36.99  5101.7   61.03    5802   58.57    5932   61.19
    6092   58.58    7552   66.54    7602   63.91    7882   63.01    8742   63.45
    8832   54.81    8912   63.16    9392   65.95    9462   63.49  9607.1   70.79
#Mann= 6 ,-1 , 0
  -951.6     .08       0  4278.4     .12       0  4901.7     .04       0
  4961.7    .015       0  5031.7     .04       0  5101.7     .08       0
#XS Ineff= 2 , 0
       0    4217    67.4    7410       0   66.45
Permanent Ineff=
       F       F
Bank Sta=4901.7,5101.7
XS Rating Curve= 0 ,0
Exp/Cntr=0.5,0.3

Type RM Length L Ch R = 1 ,43420.0 ,145,144,102
BEGIN DESCRIPTION:
Upstream Section of Bridge/Culvert/Weir
END DESCRIPTION:
XS GIS Cut Line= 4
      3098808.21     13865588.75      3094393.77     13862657.43
      3095091.39     13862052.41      3091770.15     13858390.61
#Sta/Elev= 30
-785.962   76.011814.474   68.912665.525   59.713122.572   60.413185.613   54.31
3236.833   66.263319.574   67.413389.786   59.913776.384   59.113892.694   59.74
3907.351   48.393914.286   48.243915.231    43.23920.826    43.23973.544   30.82
3990.565   33.354009.163   44.254052.582   43.114096.868   60.574558.721   60.91
4606.002   57.315030.424    60.65191.494   60.885831.595   63.286804.552   60.21
7102.419   63.987647.723   64.117773.805   69.917892.006   64.118013.045   65.81
#Mann= 11 ,-1 , 0
-785.962     .08       03236.833     .12       03776.384     .04       0
3920.826    .015       04009.163     .04       04096.868     .08       0
5030.424     .05       05191.494     .08       05831.595     .04       0
7102.419     .08       08013.045     .99       0
#XS Ineff= 5 ,-1
 -785.96    3297      66    65408013.045      66    6056    6540    63.6
 4092.14    6056      61    3297  3891.2      61
Permanent Ineff=
       T       F       F       F       F
Bank Sta=3892.694,4096.868
XS Rating Curve= 0 ,0
Skew Angle= 38
Exp/Cntr=0.5,0.3

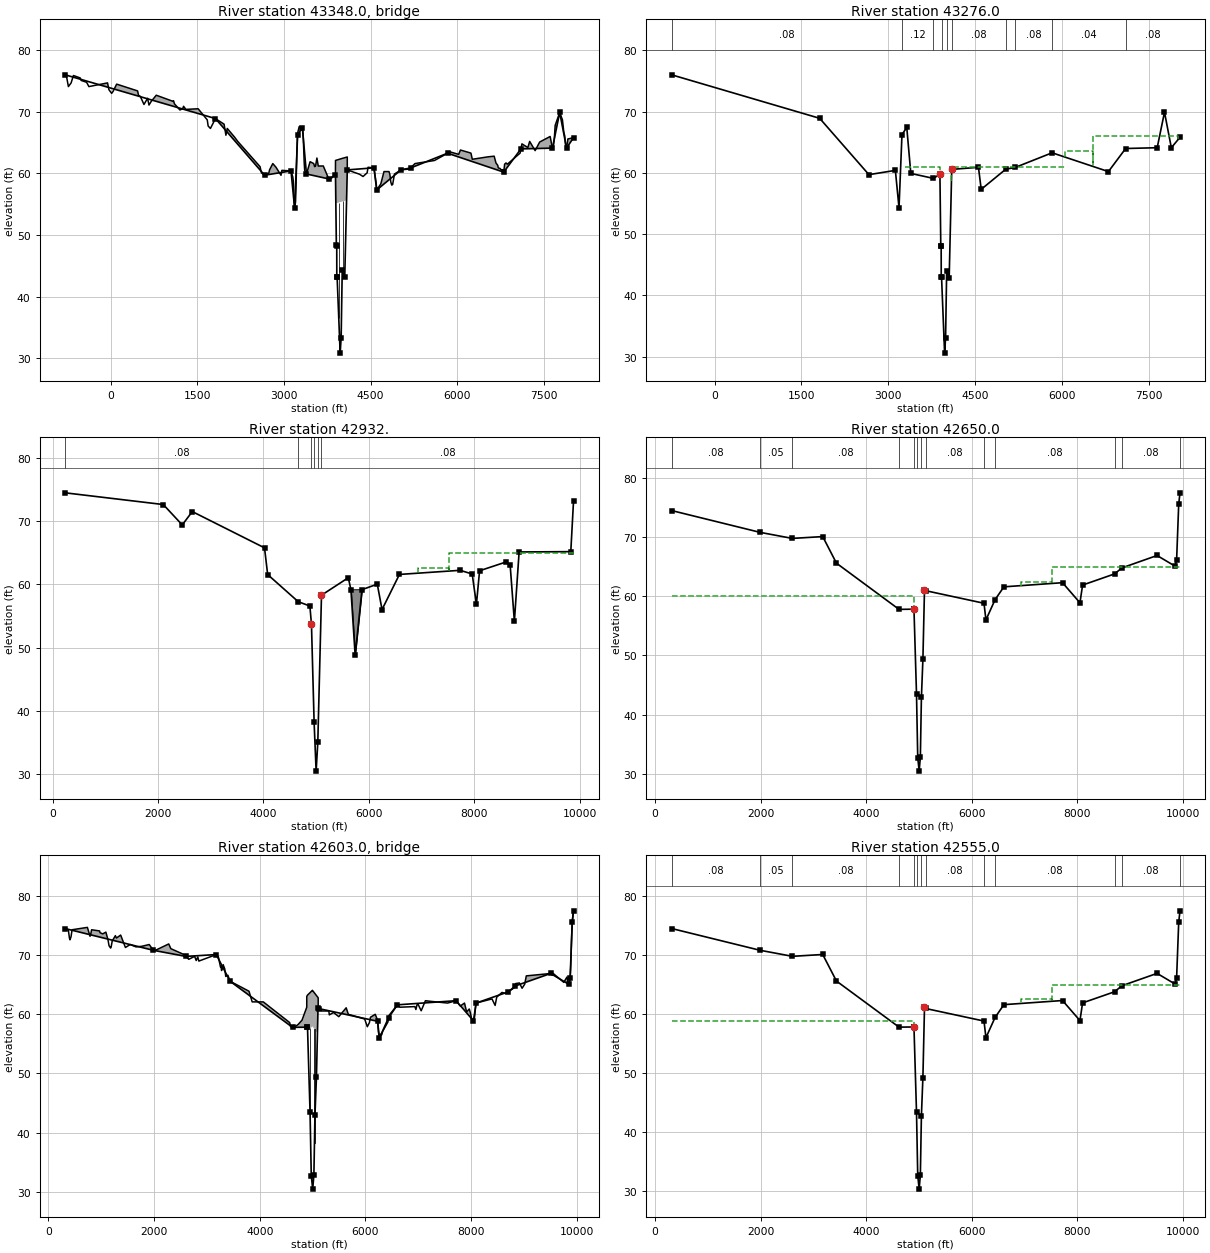
Type RM Length L Ch R = 3 ,43348.0 ,,,
BEGIN DESCRIPTION:
TC JESTER
Structure ID: E100-00-00-31
Bridge has 38 degree skew with channel.
END DESCRIPTION:
Bridge Culvert--1,0,-1,-1, 0
Deck Dist Width WeirC Skew NumUp NumDn MinLoCord MaxHiCord MaxSubmerge Is_Ogee
10,124,2.6,38, 173, 173, , , 0.95, 0, ,,,
 -785.96 -762.32  -730.8 -683.52 -644.12 -525.92 -510.16  -415.6  -376.2  -53.11
  -29.47   17.81   41.45  104.49  466.98  482.74  514.26   577.3  640.34  663.98
  703.38  790.06 1081.62  1089.5 1105.26 1199.83 1247.11 1262.87 1302.27 1515.03
 1672.63 1688.39 1727.79 1814.47  1964.2 1995.72 2019.36 2145.44  2200.6 2586.72
 2610.37 2665.53 2736.45 2752.21 2807.37 2862.53 2949.21 2964.97 3122.57 3154.09
 3161.97 3177.73 3185.61 3201.37 3209.25 3225.01 3232.89 3236.83 3240.77 3264.41
 3319.57 3327.45 3335.33  3351.1 3358.98 3389.79 3452.83 3515.87 3531.63 3547.39
 3571.03 3594.67 3626.66 3681.35 3765.12 3775.91 3776.38 3790.96    3799 3825.48
 3842.34 3868.74 3891.58 3891.67 3891.76 3892.69 3899.31 3899.79 3899.87 3907.35
 3913.97 3914.29 3915.23 3920.83 3964.72 3970.94 3971.26 3973.54 3975.36 3976.22
  3976.7 3977.33 3990.57 4005.77 4009.16 4052.58 4084.17 4084.26 4096.62 4096.71
  4096.8 4096.87  4206.4 4274.41 4308.29  4369.6 4440.52 4456.28 4558.72 4598.12
    4606 4676.92 4732.08 4818.77 4834.53 4850.29 4866.05 4881.81 4913.33 5030.42
 5031.53 5173.37 5191.49 5267.93 5606.78  5831.6  5874.7 6024.42 6055.94 6237.18
 6260.83 6536.63 6639.07 6670.59 6702.11 6709.99 6741.51 6757.27 6788.79 6804.55
 6820.31 6843.95 6867.59 7088.24 7102.42 7119.76  7222.2 7253.72 7348.28 7427.08
 7608.32 7647.72 7663.48 7679.24    7695 7773.81 7821.09 7844.73 7860.49 7876.25
 7892.01 7915.65 8013.05
      76    75.7    74.1    74.7    75.9    75.5    75.1    74.8    74.1    74.7
    73.6      73    73.3    74.5    73.4    72.7    72.5    71.2    72.2    71.1
    71.7    72.7    71.7    71.8    71.3    70.3    70.5    70.9    70.4    70.5
    68.7    67.7    67.3    68.9      68    66.2    67.3    65.9    65.2    61.1
    60.1    59.7      60    60.6    61.6      61    59.7    60.5    60.4    59.4
    58.8    55.3    54.3    55.4    57.8    63.7    65.8   66.25    66.7    67.6
    67.4      67    65.7    61.7    60.5    59.9    61.9    61.6    61.1    61.2
    62.5    61.2   61.21   61.21   59.35   59.11   59.11      59   59.05   59.23
   59.46   59.61   59.73   62.11   62.11   62.11   62.13   62.14   62.14   62.16
   62.18   62.18   62.18    62.2   62.32   62.33   62.33   62.34   62.34   62.35
   62.35   62.35   62.39   62.43   62.44   62.55   62.64   62.64   62.67   62.67
   60.54   60.57   60.21   59.99   59.87    59.5    60.1      61    60.9    58.3
    57.3    58.3    60.3    60.3    59.8    58.6    58.1    58.2    59.9   60.59
    60.6    60.7   60.87    61.6    62.1   63.27    63.5    63.1    63.8    63.3
    62.3    62.7    62.8    61.7    61.3    60.9    60.8    60.6    60.6    60.2
    61.5    61.7    61.5    63.3   63.97    64.8    64.2    65.2    63.7    65.1
      66    64.1    64.4    65.5    67.8    69.9    68.7    66.7    66.1    64.5
    64.1    65.6    65.8
                                                                                
                                                                                
                                                                                
                                                                                
                                                                                
                                                                                
                                                                                
                                                                                
                                                                   55.19   55.16
   55.18   55.18   55.18    55.2   55.32   55.33   55.33   55.34   55.34   55.35
   55.35   55.35   55.39   55.43   55.44   55.55   55.64
                                                                                
                                                                                
                                                                                
                                                                                
                                                                                
                                                                                
                        
 -785.96 -762.32  -730.8 -683.52 -644.12 -525.92 -510.16  -415.6  -376.2  -53.11
  -29.47   17.81   41.45  104.49  466.98  482.74  514.26   577.3  640.34  663.98
  703.38  790.06 1081.62  1089.5 1105.26 1199.83 1247.11 1262.87 1302.27 1515.03
 1672.63 1688.39 1727.79 1814.47  1964.2 1995.72 2019.36 2145.44  2200.6 2586.72
 2610.37 2665.53 2736.45 2752.21 2807.37 2862.53 2949.21 2964.97 3122.57 3154.09
 3161.97 3177.73 3185.61 3201.37 3209.25 3225.01 3232.89 3236.83 3240.77 3264.41
 3319.57 3327.45 3335.33  3351.1 3358.98 3389.79 3452.83 3515.87 3531.63 3547.39
 3571.03 3594.67 3626.66 3681.35 3765.12 3775.91 3776.38 3790.96    3799 3825.48
 3842.34 3868.74 3891.58 3891.67 3891.76 3892.69 3899.31 3899.79 3899.87 3907.35
 3913.97 3914.29 3915.23 3920.83 3964.72 3970.94 3971.26 3973.54 3975.36 3976.22
  3976.7 3977.33 3990.57 4005.77 4009.16 4052.58 4084.17 4084.26 4096.62 4096.71
  4096.8 4096.87  4206.4 4274.41 4308.29  4369.6 4440.52 4456.28 4558.72 4598.12
    4606 4676.92 4732.08 4818.77 4834.53 4850.29 4866.05 4881.81 4913.33 5030.42
 5031.53 5173.37 5191.49 5267.93 5606.78  5831.6  5874.7 6024.42 6055.94 6237.18
 6260.83 6536.63 6639.07 6670.59 6702.11 6709.99 6741.51 6757.27 6788.79 6804.55
 6820.31 6843.95 6867.59 7088.24 7102.42 7119.76  7222.2 7253.72 7348.28 7427.08
 7608.32 7647.72 7663.48 7679.24    7695 7773.81 7821.09 7844.73 7860.49 7876.25
 7892.01 7915.65 8013.05
      76    75.7    74.1    74.7    75.9    75.5    75.1    74.8    74.1    74.7
    73.6      73    73.3    74.5    73.4    72.7    72.5    71.2    72.2    71.1
    71.7    72.7    71.7    71.8    71.3    70.3    70.5    70.9    70.4    70.5
    68.7    67.7    67.3    68.9      68    66.2    67.3    65.9    65.2    61.1
    60.1    59.7      60    60.6    61.6      61    59.7    60.5    60.4    59.4
    58.8    55.3    54.3    55.4    57.8    63.7    65.8   66.25    66.7    67.6
    67.4      67    65.7    61.7    60.5    59.9    61.9    61.6    61.1    61.2
    62.5    61.2   61.21   61.21   59.35   59.11   59.11      59   59.05   59.23
   59.46   59.61   59.73   62.11   62.11   62.11   62.13   62.14   62.14   62.16
   62.18   62.18   62.18    62.2   62.32   62.33   62.33   62.34   62.34   62.35
   62.35   62.35   62.39   62.43   62.44   62.55   62.64   62.64   62.67   62.67
   60.54   60.57   60.21   59.99   59.87    59.5    60.1      61    60.9    58.3
    57.3    58.3    60.3    60.3    59.8    58.6    58.1    58.2    59.9   60.59
    60.6    60.7   60.87    61.6    62.1   63.27    63.5    63.1    63.8    63.3
    62.3    62.7    62.8    61.7    61.3    60.9    60.8    60.6    60.6    60.2
    61.5    61.7    61.5    63.3   63.97    64.8    64.2    65.2    63.7    65.1
      66    64.1    64.4    65.5    67.8    69.9    68.7    66.7    66.1    64.5
    64.1    65.6    65.8
                                                                                
                                                                                
                                                                                
                                                                                
                                                                                
                                                                                
                                                                                
                                                                                
                                                                   55.19   55.16
   55.18   55.18   55.18    55.2   55.32   55.33   55.33   55.34   55.34   55.35
   55.35   55.35   55.39   55.43   55.44   55.55   55.64
                                                                                
                                                                                
                                                                                
                                                                                
                                                                                
                                                                                
                        
Pier Skew, UpSta & Num, DnSta & Num=  ,3948.958, 2 ,3948.958, 2 , 0 , 0 , 0 ,,
       3       3
   35.55   56.28
       3       3
   35.31   56.04
Pier Skew, UpSta & Num, DnSta & Num=  ,4018.697, 2 ,4018.697, 2 , 0 , 0 , 0 ,,
       3       3
   42.96   56.47
       3       3
   42.72   56.23
BR Coef= 1 , 1 , 0 ,1.25, 0 ,,,0.8,0,1.2,0,
WSPro=,,,, 1 ,,,, 0 ,,,, 0 ,,,,-1 ,-1 ,-1 , 0 , 0 , 0 , 0 , 0
BR D #Sta/Elev= 173
 -785.96   76.01 -762.32   75.71  -730.8   74.11 -683.52   74.71 -644.12   75.91
 -525.92   75.51 -510.16   75.11  -415.6   74.81  -376.2   74.11  -53.11   74.71
  -29.47   73.61   17.81   73.01   41.45   73.31  104.49   74.51  466.98   73.41
  482.74   72.71  514.26   72.51   577.3   71.21  640.34   72.21  663.98   71.11
  703.38   71.71  790.06   72.71 1081.62   71.71  1089.5   71.81 1105.26   71.31
 1199.83   70.31 1247.11   70.51 1262.87   70.91 1302.27   70.41 1515.03   70.51
 1672.63   68.71 1688.39   67.71 1727.79   67.31 1814.47   68.91  1964.2   68.01
 1995.72   66.21 2019.36   67.31 2145.44   65.91  2200.6   65.21 2586.72   61.11
 2610.37   60.11 2665.53   59.71 2736.45   60.01 2752.21   60.61 2807.37   61.61
 2862.53   61.01 2949.21   59.71 2964.97   60.51 3122.57   60.41 3154.09   59.41
 3161.97   58.81 3177.73   55.31 3185.61   54.31 3201.37   55.41 3209.25   57.81
 3225.01   63.71 3232.89   65.81 3236.83   66.26 3240.77   66.71 3264.41   67.61
 3319.57   67.41 3327.45   67.01 3335.33   65.71  3351.1   61.71 3358.98   60.51
 3389.79   59.91 3452.83   61.91 3515.87   61.61 3531.63   61.11 3547.39   61.21
 3571.03   62.51 3594.67   61.21 3626.66   61.21 3681.35   61.21 3765.12   59.35
 3775.91   59.11 3776.38   59.11 3790.96   58.98    3799   58.86 3825.48   59.23
 3842.34   59.46 3868.74   59.61 3891.58   59.73 3891.67   59.73 3891.76   59.73
 3892.69   59.49 3899.31   55.45 3899.79   55.01 3899.87   54.95 3907.35   48.14
 3913.97      48 3914.29   47.99 3915.23   42.95 3920.83   42.95 3964.72   33.01
 3970.94    32.5 3971.26   32.01 3973.54   30.57 3975.36    30.6 3976.22   30.57
  3976.7   32.11 3977.33   32.57 3990.57    33.1 4005.77   42.89 4009.16      44
 4052.58   42.86 4084.17   55.32 4084.26   55.35 4096.62   60.22 4096.71   60.26
  4096.8   60.29 4096.87   60.32  4206.4   60.21 4274.41   59.99 4308.29   59.88
  4369.6   59.51 4440.52   60.11 4456.28   61.01 4558.72   60.91 4598.12   58.31
    4606   57.31 4676.92   58.31 4732.08   60.31 4818.77   60.31 4834.53   59.81
 4850.29   58.61 4866.05   58.11 4881.81   58.21 4913.33   59.91 5030.42    60.6
 5031.53   60.61 5173.37   60.71 5191.49   60.88 5267.93   61.61 5606.78   62.11
  5831.6   63.28  5874.7   63.51 6024.42   63.11 6055.94   63.81 6237.18   63.31
 6260.83   62.31 6536.63   62.71 6639.07   62.81 6670.59   61.71 6702.11   61.31
 6709.99   60.91 6741.51   60.81 6757.27   60.61 6788.79   60.61 6804.55   60.21
 6820.31   61.51 6843.95   61.71 6867.59   61.51 7088.24   63.31 7102.42   63.98
 7119.76   64.81  7222.2   64.21 7253.72   65.21 7348.28   63.71 7427.08   65.11
 7608.32   66.01 7647.72   64.11 7663.48   64.41 7679.24   65.51    7695   67.81
 7773.81   69.91 7821.09   68.71 7844.73   66.71 7860.49   66.11 7876.25   64.51
 7892.01   64.11 7915.65   65.61 8013.05   65.81
BR D #Mann= 10
 -785.96     .08 3236.83     .12 3776.38     .04 3920.83    .015 4009.16     .04
 4096.87     .08 5030.42     .05 5191.49     .08  5831.6     .04 7102.42     .08
BR D Banks=3892.69,4096.87
BC Design=,, 0 ,, 0 ,,,,,,
BC HTab HWMax=76.01
BC Use User HTab Curves=0
BC User HTab FreeFlow(D)= 0

Type RM Length L Ch R = 1 ,43276.0 ,625.3,344,77
BEGIN DESCRIPTION:
Downstream Section of Bridge/Culvert/Weir
END DESCRIPTION:
XS GIS Cut Line= 4
      3098928.72     13865571.52      3094547.14     13862662.02
      3095238.14     13862062.74      3091896.29     13858378.22
#Sta/Elev= 30
-743.409   76.011814.474   68.912665.525   59.713122.572   60.413185.613   54.31
3236.833   66.263319.574   67.413389.786   59.913776.384   59.113892.694   59.74
3907.351   48.143914.286   47.993915.231   42.953920.826   42.953973.544   30.57
3990.565    33.14009.163      444052.582   42.864096.868   60.574558.721   60.91
4606.002   57.315030.424    60.65191.495   60.885831.595   63.286804.552   60.21
7102.419   63.987647.723   64.117773.805   69.917892.006   64.118041.808   65.81
#Mann= 10 ,-1 , 0
-743.409     .08       03236.833     .12       03776.384     .04       0
3920.826    .015       04009.163     .04       04096.868     .08       0
5030.424     .05       05191.495     .08       05831.595     .04       0
7102.419     .08       0
#XS Ineff= 5 ,-1
-743.409    3297      66    6540 8013.05      66    6056    6540    63.6
 4092.14    6056      61    32973891.199      61
Permanent Ineff=
       T       F       F       F       F
Bank Sta=3892.694,4096.868
XS Rating Curve= 0 ,0
Skew Angle= 38
Exp/Cntr=0.5,0.3

Type RM Length L Ch R = 1 ,42932.  ,474.1,282,40.1
BEGIN DESCRIPTION:
W. 34th - U/S - XS 4
END DESCRIPTION:
XS GIS Cut Line= 4
      3099078.89     13865101.18      3095568.48     13862300.65
      3095287.64     13862004.21      3092105.47     13858488.49
#Sta/Elev= 30
   239.9   74.45  2099.9    72.6  2459.9   69.38  2649.9   71.49  4019.9   65.76
  4079.9   61.54  4659.9   57.25  4880.6   56.57  4910.6   53.66  4960.6   38.22
  4998.8   30.49  5030.6   35.02  5100.6   58.28  5608.9   61.04  5658.9   59.14
  5738.9   48.82  5868.9   59.16  6158.9   60.02  6248.9   56.01  6578.9   61.56
  7728.9   62.21  7958.9   61.63  8038.9   56.83  8098.9   62.14  8598.9   63.52
  8678.9   63.04  8758.9   54.14  8848.9   65.11  9828.9   65.16  9880.9   73.18
#Mann= 6 ,-1 , 0
   239.9     .08       0  4659.9     .05       0  4910.6     .04       0
  4960.6    .015       0  5030.6     .04       0  5100.6     .08       0
#XS Ineff= 2 ,-1
    7515  9880.9      65    6930    7515    62.5
Permanent Ineff=
       F       F
#Block Obstruct= 1 ,-1
    5654    5868   59.22
Bank Sta=4910.6,5100.6
XS Rating Curve= 0 ,0
Exp/Cntr=0.5,0.3

Type RM Length L Ch R = 1 ,42650.0 ,96,95,75.1
BEGIN DESCRIPTION:
Upstream Section of Bridge/Culvert/Weir
END DESCRIPTION:
XS GIS Cut Line= 4
      3099378.46     13864432.46      3095740.91     13861868.88
      3095191.45     13861850.36      3092130.94     13858383.78
#Sta/Elev= 30
   316.9    74.5  1987.2   70.82  2601.5   69.79  3176.9    70.1  3436.9    65.6
  4621.2   57.79  4901.6   57.82  4904.1   57.88  4952.3    43.5  4975.6   32.73
  5002.7   30.43  5025.3   32.85  5045.2    42.9  5073.4   49.34  5103.6   61.14
  5125.1   60.95  6230.3   58.82  6266.8      56  6440.3   59.44  6606.8    61.6
  7716.8    62.3  8046.8    58.9  8096.8    61.9  8703.8   63.79  8840.1    64.8
  9506.8    66.9  9846.8    65.1  9876.8    66.1  9916.8    75.6  9941.1    77.5
#Mann= 13 ,-1 , 0
   316.9     .08       0  1987.2     .05       0  2601.5     .08       0
  4621.2     .05       0  4901.6     .04       0  4952.3    .015       0
  5045.2     .04       0  5125.1     .08       0  6230.3     .05       0
  6440.3     .08       0  8703.8     .04       0  8840.1     .08       0
  9941.1     .99       0
#XS Ineff= 4 ,-1
    7515  9941.1      65    6930    7515    62.5    5101    6930      60
   316.9    4896      60
Permanent Ineff=
       F       F       F       F
Bank Sta=4904.1,5103.6
XS Rating Curve= 0 ,0
Exp/Cntr=0.5,0.3

Type RM Length L Ch R = 3 ,42603.0 ,,,
BEGIN DESCRIPTION:
W. 34TH STREET
Structure ID: E100-00-00-30
END DESCRIPTION:
Bridge Culvert--1,0,-1,-1, 0
Deck Dist Width WeirC Skew NumUp NumDn MinLoCord MaxHiCord MaxSubmerge Is_Ogee
10,74,2.6,0, 175, 175, , , 0.95, 0, ,,,
   316.9   376.9   396.9   406.9   426.9   446.9   736.9   786.9   796.9   816.9
   966.9   976.9  1026.9  1086.9  1126.9  1146.9  1176.9  1186.9  1206.9  1266.9
  1286.9  1366.9  1456.9  1546.9  1656.9  1766.9  1906.9  1987.2  1996.9  2276.9
  2316.9  2566.9  2601.5  2656.9  2766.9  2796.9  2826.9  2846.9  3176.9  3216.9
  3256.9  3266.9  3276.9  3296.9  3306.9  3336.9  3356.9  3396.9  3436.9  3796.9
  3856.9  4066.9  4566.9  4581.4  4596.9  4621.2  4636.9  4666.9    4684  4684.1
  4729.6  4731.6  4784.3  4800.3  4829.4 4889.89    4890 4890.11  4898.9  4901.6
  4904.1 4905.91 4906.05  4917.5  4931.6  4941.7  4952.3  4959.2  4975.6    4993
  4994.6  4997.6  4997.9  5000.1  5002.7  5005.4  5007.4  5025.3  5036.1  5045.2
  5051.6  5073.4  5090.3 5091.57  5091.7  5094.5  5103.6 5106.59  5106.7 5106.81
  5125.1  5142.6  5144.5  5180.3  5274.3  5308.7  5308.8  5316.8  5396.8  5496.8
  5636.8  5676.8  5986.8  6036.8  6076.8  6096.8  6186.8  6226.8  6230.3  6236.8
  6246.8  6266.8  6296.8  6306.8  6326.8  6426.8  6440.3  6446.8  6606.8  6656.8
  6936.8  6956.8  6976.8  6996.8  7056.8  7136.8  7226.8  7556.8  7716.8  7796.8
  7876.8  7916.8  7966.8  7986.8  8016.8  8046.8  8066.8  8086.8  8096.8  8396.8
  8456.8  8486.8  8586.8  8656.8  8703.8  8836.8  8840.1  8846.8  8916.8  8966.8
  9016.8  9046.8  9506.8  9536.8  9556.8  9756.8  9816.8  9846.8  9866.8  9876.8
  9886.8  9906.8  9916.8  9936.8  9941.1
    74.5    74.2    72.9    72.6    73.1    74.3    74.7    73.2    73.4    74.3
    74.1    73.8    73.6    73.9    72.6    71.6    71.2    71.4    72.4    73.3
    72.9    73.4    71.3    71.8    71.4    71.5    71.8   70.82    70.7    71.9
    71.1    70.1   69.79    69.3    69.8    69.1    69.7      69    70.1    69.7
      68    68.1    67.4    67.9    68.4    67.7    66.4    66.6    65.6    63.9
    62.1    62.1    58.6   57.98   57.83   57.87   58.11   58.01   57.99   57.99
    58.3   58.32   58.85   59.01   59.72   61.19   62.99   62.99    63.2   63.22
   63.25   63.26   63.26   63.36   63.48   63.57   63.66   63.72   63.87   64.02
   64.03   64.06   64.06   64.03      64   63.97   63.94   63.73    63.6   63.49
   63.41   63.15   62.94   62.93   62.92   62.89   62.81   62.79   62.79   61.12
   60.96    60.8   60.78   60.56   60.55   60.56   60.56    59.9    60.3    59.6
    61.1      60    59.2    57.9    58.6    59.5      60    59.1   58.82    58.3
      57      56    56.7    56.5    57.1    58.7   59.44    59.8    61.6    61.2
    61.3    60.8    61.6    61.7    60.6    62.3    62.2    61.9    62.3    61.4
    61.9    60.4    60.9    60.3      59    58.9    59.5    61.3    61.9    62.6
    61.5    62.9    63.7    63.5   63.79    64.6    64.8    65.2    65.3    64.4
    65.1    66.5    66.9    66.6    66.9    65.4    66.3    65.1    65.4    66.1
    67.9    73.6    75.6    77.4    77.5
                                                                                
                                                                                
                                                                                
                                                                                
                                                                                
                                                                                
                                                                                
                   57.29   57.26   57.38   57.47   57.56   57.62   57.77   57.92
   57.93   57.96   57.96   57.93    57.9   57.87   57.84   57.63    57.5   57.39
   57.31   57.05   56.84   56.83
                                                                                
                                                                                
                                                                                
                                                                                
                                                                                
                                                                                
                                                                                
                                        
   316.9   376.9   396.9   406.9   426.9   446.9   736.9   786.9   796.9   816.9
   966.9   976.9  1026.9  1086.9  1126.9  1146.9  1176.9  1186.9  1206.9  1266.9
  1286.9  1366.9  1456.9  1546.9  1656.9  1766.9  1906.9  1987.2  1996.9  2276.9
  2316.9  2566.9  2601.5  2656.9  2766.9  2796.9  2826.9  2846.9  3176.9  3216.9
  3256.9  3266.9  3276.9  3296.9  3306.9  3336.9  3356.9  3396.9  3436.9  3796.9
  3856.9  4066.9  4566.9  4581.4  4596.9  4621.2  4636.9  4666.9    4684  4684.1
  4729.6  4731.6  4784.3  4800.3  4829.4 4889.89    4890 4890.11  4898.9  4901.6
  4904.1 4905.91 4906.04  4917.5  4931.6  4941.7  4952.3  4959.2  4975.6    4993
  4994.6  4997.6  4997.9  5000.1  5002.7  5005.4  5007.4  5025.3  5036.1  5045.2
  5051.6  5073.4  5090.3 5091.58  5091.7  5094.5  5103.6 5106.59  5106.7 5106.81
  5125.1  5142.6  5144.5  5180.3  5274.3  5308.7  5308.8  5316.8  5396.8  5496.8
  5636.8  5676.8  5986.8  6036.8  6076.8  6096.8  6186.8  6226.8  6230.3  6236.8
  6246.8  6266.8  6296.8  6306.8  6326.8  6426.8  6440.3  6446.8  6606.8  6656.8
  6936.8  6956.8  6976.8  6996.8  7056.8  7136.8  7226.8  7556.8  7716.8  7796.8
  7876.8  7916.8  7966.8  7986.8  8016.8  8046.8  8066.8  8086.8  8096.8  8396.8
  8456.8  8486.8  8586.8  8656.8  8703.8  8836.8  8840.1  8846.8  8916.8  8966.8
  9016.8  9046.8  9506.8  9536.8  9556.8  9756.8  9816.8  9846.8  9866.8  9876.8
  9886.8  9906.8  9916.8  9936.8  9941.1
    74.5    74.2    72.9    72.6    73.1    74.3    74.7    73.2    73.4    74.3
    74.1    73.8    73.6    73.9    72.6    71.6    71.2    71.4    72.4    73.3
    72.9    73.4    71.3    71.8    71.4    71.5    71.8   70.82    70.7    71.9
    71.1    70.1   69.79    69.3    69.8    69.1    69.7      69    70.1    69.7
      68    68.1    67.4    67.9    68.4    67.7    66.4    66.6    65.6    63.9
    62.1    62.1    58.6   57.98   57.83   57.87   58.11   58.01   57.99   57.99
    58.3   58.32   58.85   59.01   59.72   61.19   62.99   62.99    63.2   63.22
   63.25   63.26   63.26   63.36   63.48   63.57   63.66   63.72   63.87   64.02
   64.03   64.06   64.06   64.03      64   63.97   63.94   63.73    63.6   63.49
   63.41   63.15   62.94   62.93   62.92   62.89   62.81   62.79   62.79   61.12
   60.96    60.8   60.78   60.56   60.55   60.56   60.56    59.9    60.3    59.6
    61.1      60    59.2    57.9    58.6    59.5      60    59.1   58.82    58.3
      57      56    56.7    56.5    57.1    58.7   59.44    59.8    61.6    61.2
    61.3    60.8    61.6    61.7    60.6    62.3    62.2    61.9    62.3    61.4
    61.9    60.4    60.9    60.3      59    58.9    59.5    61.3    61.9    62.6
    61.5    62.9    63.7    63.5   63.79    64.6    64.8    65.2    65.3    64.4
    65.1    66.5    66.9    66.6    66.9    65.4    66.3    65.1    65.4    66.1
    67.9    73.6    75.6    77.4    77.5
                                                                                
                                                                                
                                                                                
                                                                                
                                                                                
                                                                                
                                                                                
                   57.29   57.26   57.38   57.47   57.56   57.62   57.77   57.92
   57.93   57.96   57.96   57.93    57.9   57.87   57.84   57.63    57.5   57.39
   57.31   57.05   56.84   56.83
                                                                                
                                                                                
                                                                                
                                                                                
                                                                                
                                                                                
                                                                                
                                        
Pier Skew, UpSta & Num, DnSta & Num=  ,4959.2, 2 ,4959.2, 2 , 0 , 0 , 0 ,,
       3       3
   37.88   58.63
       3       3
   37.81   58.56
Pier Skew, UpSta & Num, DnSta & Num=  ,5036.1, 2 ,5036.1, 2 , 0 , 0 , 0 ,,
       3       3
   37.46   58.52
       3       3
   37.39   58.45
BR Coef= 1 , 1 , 0 ,1.25, 0 ,,,0.8,0,1.2,0,
WSPro=,,,, 1 ,,,, 0 ,,,, 0 ,,,,-1 ,-1 ,-1 , 0 , 0 , 0 , 0 , 0
BC Design=,, 0 ,, 0 ,,,,,,
BC HTab HWMax=77.5
BC Use User HTab Curves=0
BC User HTab FreeFlow(D)= 0

Type RM Length L Ch R = 1 ,42555.0 ,95.6,199,261
BEGIN DESCRIPTION:
Downstream Section of Bridge/Culvert/Weir
END DESCRIPTION:
XS GIS Cut Line= 4
      3099398.47     13864342.96      3095753.61     13861774.23
      3095208.12     13861755.84      3092156.17     13858298.95
#Sta/Elev= 30
   316.9    74.5  1987.2   70.82  2601.5   69.79  3176.9    70.1  3436.9    65.6
  4621.2   57.79  4901.6   57.82  4904.1   57.88  4952.3   43.41  4975.6   32.64
  5002.7   30.34  5025.3   32.76  5045.2   42.81  5073.4   49.25  5103.6   61.14
  5125.1   60.95  6230.3   58.82  6266.8      56  6440.3   59.44  6606.8    61.6
  7716.8    62.3  8046.8    58.9  8096.8    61.9  8703.8   63.79  8840.1    64.8
  9506.8    66.9  9846.8    65.1  9876.8    66.1  9916.8    75.6  9941.1    77.5
#Mann= 13 ,-1 , 0
   316.9     .08       0  1987.2     .05       0  2601.5     .08       0
  4621.2     .05       0  4901.6     .04       0  4952.3    .015       0
  5045.2     .04       0  5125.1     .08       0  6230.3     .05       0
  6440.3     .08       0  8703.8     .04       0  8840.1     .08       0
  9941.1     .99       0
#XS Ineff= 4 ,-1
    7515  9941.1      65    6930    7515    62.5    5101    6930    58.9
   316.9    4896    58.9
Permanent Ineff=
       F       F       F       F
Bank Sta=4904.1,5103.6
XS Rating Curve= 0 ,0
Exp/Cntr=0.5,0.3

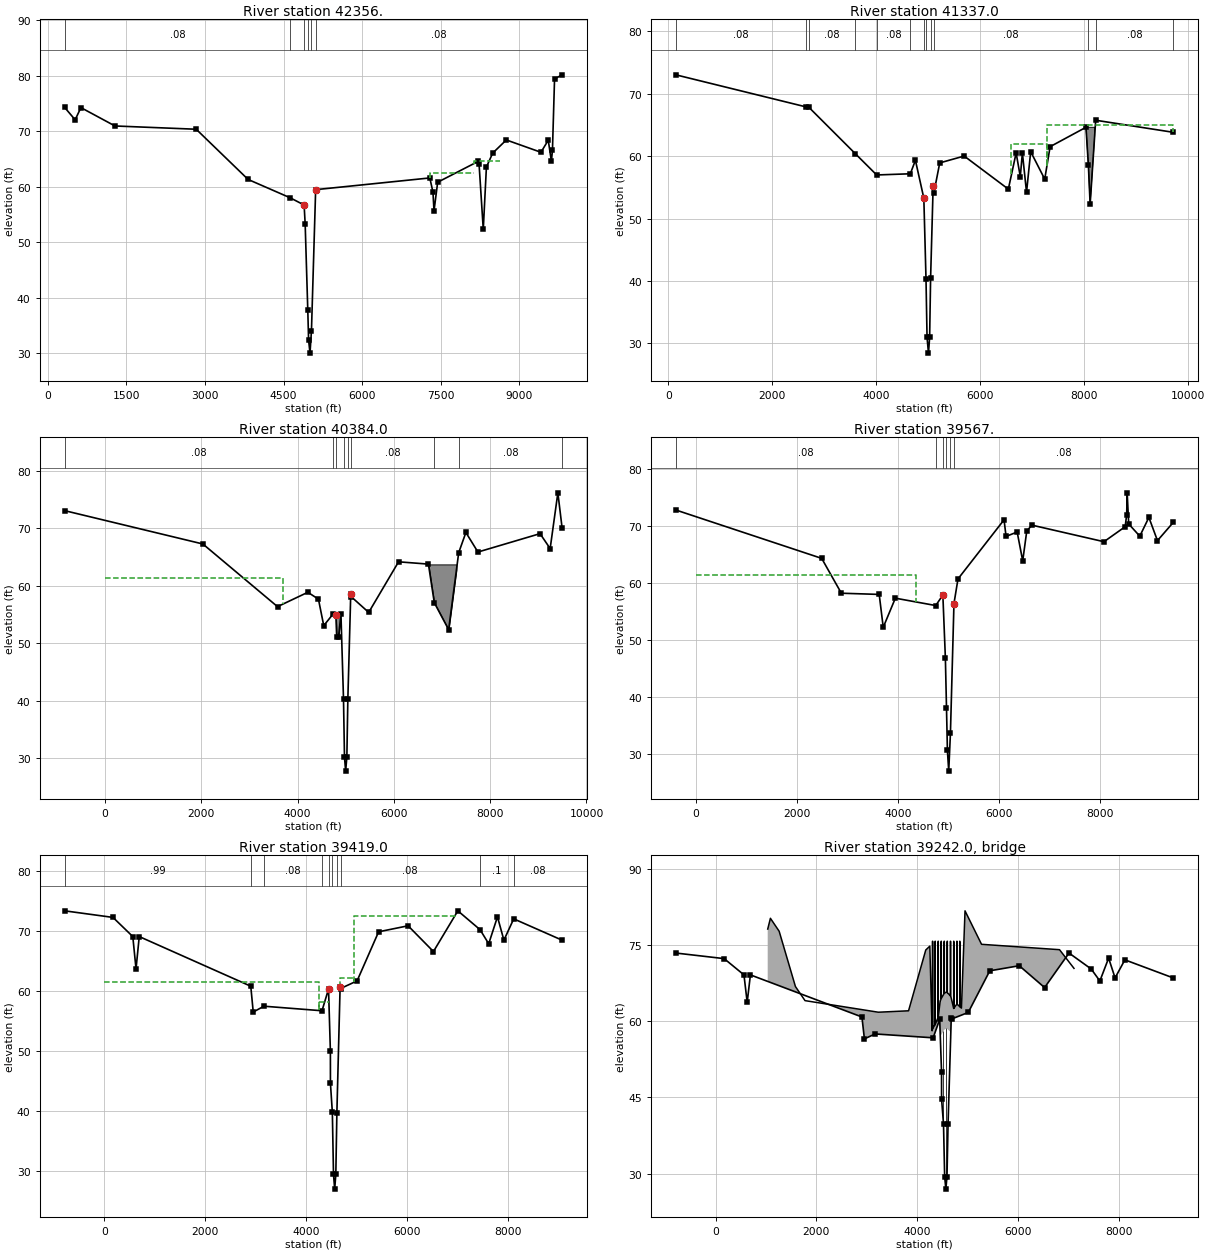
Type RM Length L Ch R = 1 ,42356.  ,1074.9,1019,840.5
BEGIN DESCRIPTION:
W. 34th - D/S - XS 1
END DESCRIPTION:
XS GIS Cut Line= 5
      3099426.77     13864246.74       3095781.9     13861678.01
      3095404.66     13861497.15      3093841.69     13860079.84
      3092184.47     13858202.73
#Sta/Elev= 30
   321.5   74.32   521.5   72.09   631.5   74.29  1281.5   70.98  2831.5   70.39
  3821.5   61.34    4625   58.03  4890.6   56.73  4910.6   53.27  4960.6   37.74
 4976.02   32.35 5002.72   30.03  5030.6   34.08  5110.6    59.5  7288.9   61.61
  7348.8   59.05  7368.8   55.67  7438.8   60.84  8208.8   64.58  8228.8   64.07
  8308.8   52.34  8368.8   63.57  8488.8   66.09  8748.8   68.46  9408.8   66.24
  9548.8   68.41  9608.8   64.61  9628.8    66.6  9668.8   79.45  9812.8    80.2
#Mann= 6 ,-1 , 0
   321.5     .08       0    4625     .05       0  4890.6     .04       0
  4960.6    .015       0  5030.6     .04       0  5110.6     .08       0
#XS Ineff= 2 ,-1
    8132    8620   64.66    7286    8132   62.59
Permanent Ineff=
       F       F
Bank Sta=4890.6,5110.6
XS Rating Curve= 0 ,0
Exp/Cntr=0.3,0.1

Type RM Length L Ch R = 1 ,41337.0 ,917,953,958
BEGIN DESCRIPTION:
Cross Section E100-00-00-X28
END DESCRIPTION:
XS GIS Cut Line= 4
      3099705.72     13863884.66      3096450.08     13860824.98
      3093932.91     13859985.03      3092315.16     13858145.91
#Sta/Elev= 30
   141.5      73  2650.2   67.86    2697   67.84  3596.8   60.36  4005.9   56.97
  4653.6   57.16  4751.3   59.32  4913.3   53.25  4954.9   40.39  4975.1   30.97
  5002.8   28.45  5024.9   30.99  5043.7   40.53    5093   55.28  5106.8   54.12
  5219.3    58.9  5689.3      60  6539.3    54.7  6689.3    60.5  6769.3    56.7
  6809.3    60.5  6889.3    54.2  6969.3    60.7  7239.3    56.3  7342.9    61.5
  8032.9    64.6  8079.3   58.53  8112.9    52.3    8220   65.73  9712.3    63.8
#Mann= 13 ,-1 , 0
   141.5     .08       0  2650.2     .07       0    2697     .08       0
  3596.8     .05       0  4005.9     .08       0  4653.6     .05       0
  4913.3     .04       0  4954.9    .015       0  5043.7     .04       0
  5106.8     .08       0  8079.3     .04       0    8220     .08       0
  9712.3     .99       0
#XS Ineff= 2 ,-1
    7280  9712.3      65    6600    7280      62
Permanent Ineff=
       F       F
#Block Obstruct= 2 ,-1
  8028.6    8200    64.6    8201    8202      62
Bank Sta=4913.3,5093
XS Rating Curve= 0 ,0
Exp/Cntr=0.3,0.1

Type RM Length L Ch R = 1 ,40384.0 ,816,817,1656.8
BEGIN DESCRIPTION:
Cross Section E100-00-00-X27
Located At: US 610 N.LOOP
END DESCRIPTION:
XS GIS Cut Line= 5
      3100965.86     13863356.76      3096727.58     13859914.22
      3096146.26     13859718.55      3094135.79     13859328.49
      3092587.62     13857754.24
#Sta/Elev= 30
  -835.4    73.1  2034.6    67.3  3584.6    56.4  4214.6    58.9  4434.6    57.7
  4544.6    53.1  4738.3   55.12  4796.6   54.87  4813.9   51.14  4851.4   51.15
    4902   55.04  4954.9   40.35  4975.2   30.26  4999.4   27.79  5024.7   30.26
  5045.1   40.33  5105.2    58.6    5116   58.12  5478.2    55.4  6098.2    64.2
  6718.2    63.8  6840.3   57.09  7138.2    52.4  7346.8   65.78  7496.2    69.3
  7746.2    65.9  9036.2    69.1  9246.2    66.5  9406.2    76.2  9494.1    70.1
#Mann= 9 ,-1 , 0
  -835.4     .08       0  4738.3     .05       0  4796.6     .04       0
  4954.9    .015       0  5045.1     .04       0    5116     .08       0
  6840.3     .04       0  7346.8     .08       0  9494.1     .99       0
#XS Ineff= 2 , 0
       0    3700   61.46               0
Permanent Ineff=
       F       F
#Block Obstruct= 2 ,-1
    4790  4887.5    54.9    6721    7300   63.75
Bank Sta=4796.6,5105.2
XS Rating Curve= 0 ,0
Exp/Cntr=0.3,0.1

Type RM Length L Ch R = 1 ,39567.  ,147,148,632.1
BEGIN DESCRIPTION:
Loop 610 EB Access Rd - U/S - XS 4
END DESCRIPTION:
XS GIS Cut Line= 4
      3100629.75     13862795.17      3096855.63     13859172.47
      3096539.23     13858923.84      3092762.46     13857034.54
#Sta/Elev= 30
  -401.4   72.84  2488.6   64.36  2878.6   58.25  3628.6   58.04  3708.6   52.27
  3948.6   57.38  4748.6   56.09    4890   57.93    4940   46.86 4962.07   38.15
 4980.16   30.69 5006.22   27.06    5040   33.68    5110   56.43    5190   60.76
  6102.4   71.12  6142.4   68.21  6362.4   68.98  6472.4   63.92  6552.4   69.13
  6652.4   70.19  8082.4   67.28  8502.4   69.91  8532.4   72.01  8542.4   75.85
  8572.4   70.39  8792.4   68.25  8972.4   71.54  9142.4   67.47  9455.4   70.66
#Mann= 6 ,-1 , 0
  -401.4     .08       0  4748.6     .05       0    4890     .04       0
 4962.07    .015       0    5040     .04       0    5110     .08       0
#XS Ineff= 2 , 0
       0    4350   61.46               0
Permanent Ineff=
       F       F
Bank Sta=4890,5110
XS Rating Curve= 0 ,0
Exp/Cntr=0.5,0.3

Type RM Length L Ch R = 1 ,39419.0 ,394.8,402,416.5
BEGIN DESCRIPTION:
Upstream Section of Bridge/Culvert/Weir
END DESCRIPTION:
XS GIS Cut Line= 5
      3101375.18     13862610.03      3098975.76     13860308.49
      3096889.91     13858995.76       3095972.2     13858532.61
      3092977.79     13855907.02
#Sta/Elev= 30
-787.842   73.41 170.742   72.31 563.566   69.11 627.514   63.71 691.463   69.11
 2903.43   60.822952.305   56.513165.526   57.484316.045   56.724445.769   60.34
4482.676   49.934483.498   44.62 4521.41   39.764544.159   29.414567.818   26.93
4590.292   29.394611.395    39.7 4675.16   60.664683.291   60.435011.984   61.71
5439.433   69.916024.103   70.916526.551   66.61 7010.73   73.417450.328   70.27
7622.806   67.917796.379   72.417924.276   68.518118.587   72.079078.267   68.51
#Mann= 10 ,-1 , 0
-787.842     .99       0 2903.43     .05       03165.526     .08       0
4316.045     .05       04445.769     .04       0 4521.41    .015       0
4611.395     .04       04683.291     .08       07450.328      .1       0
8118.587     .08       0
#XS Ineff= 4 ,-1
       0    4250   61.46    4250 4445.77    58.1 4675.16 4948.03   62.25
 4948.03    7000    72.5
Permanent Ineff=
       F       F       F       F
Bank Sta=4445.769,4675.16
XS Rating Curve= 0 ,0
Skew Angle= 24
Exp/Cntr=0.5,0.3

Type RM Length L Ch R = 3 ,39242.0 ,,,
BEGIN DESCRIPTION:
LOOP 610
Structure ID: E100-00-00-29
Bridge has 24 degree skew with channel.
END DESCRIPTION:
Bridge Culvert--1,0,-1,-1, 0
Deck Dist Width WeirC Skew NumUp NumDn MinLoCord MaxHiCord MaxSubmerge Is_Ogee
10,334,2.6,24, 60, 60, , , 0.95, 0, ,,,
    1035 1088.34 1261.71 1584.84  1774.6 3228.89 3827.99 4169.47    4250 4295.68
 4303.66 4303.66 4305.96 4305.96 4355.28 4355.28 4357.58 4357.58 4415.28 4415.28
 4417.58 4417.58 4455.27 4455.36 4475.28 4475.28 4477.58 4477.58 4535.28 4535.28
 4537.58 4537.58 4579.06 4595.29 4595.29 4597.58 4597.58 4659.23 4659.23 4661.53
 4661.53 4667.67 4667.76 4723.18 4723.18 4725.48 4725.48 4787.13 4787.13 4789.43
 4789.43 4842.86 4842.86 4845.15 4845.15 4876.89 4948.03 5275.85 6822.44 7109.59
   78.13   80.25    77.7   66.81   64.04   61.76   62.04   74.01   74.77    58.1
   58.45   75.73   75.73   58.55   59.32   75.73   75.73   59.35   60.77   75.73
   75.73   60.86   63.94   63.94   64.44   75.73   75.73   64.49   65.47   75.73
   75.73   65.49   65.73   65.63   75.73   75.73   65.61   64.97   75.73   75.73
   64.93   64.82   64.82    62.5   75.73   75.73   62.53   63.37   75.73   75.73
   63.35   62.88   75.73   75.73   62.85   62.57   81.72   75.13   74.07   70.39
       0       0       0       0       0       0       0       0       0       0
       0       0       0       0       0       0       0       0       0       0
       0       0       0   56.82   57.26   57.26   57.32   57.32   58.29   58.29
   58.32   58.32   58.56   58.46   58.46   58.44   58.44   57.87   57.87   57.86
   57.86   57.88       0       0       0       0       0       0       0       0
       0       0       0       0       0       0       0       0       0       0
    1035 1088.34 1261.71 1584.84  1774.6 3228.89 3827.99 4169.47    4250 4295.68
 4303.66 4303.66 4305.96 4305.96 4355.28 4355.28 4357.58 4357.58 4415.28 4415.28
 4417.58 4417.58 4455.27 4455.36 4475.28 4475.28 4477.58 4477.58 4535.28 4535.28
 4537.58 4537.58 4579.06 4595.29 4595.29 4597.58 4597.58 4659.23 4659.23 4661.53
 4661.53 4667.67 4667.76 4723.18 4723.18 4725.48 4725.48 4787.13 4787.13 4789.43
 4789.43 4842.86 4842.86 4845.15 4845.15 4876.89 4948.03 5275.85 6822.44 7109.59
   78.13   80.25    77.7   66.81   64.04   61.76   62.04   74.01   74.77    58.1
   58.45   75.73   75.73   58.55   59.32   75.73   75.73   59.35   60.77   75.73
   75.73   60.86   63.94   63.94   64.44   75.73   75.73   64.49   65.47   75.73
   75.73   65.49   65.73   65.63   75.73   75.73   65.61   64.97   75.73   75.73
   64.93   64.82   64.82    62.5   75.73   75.73   62.53   63.37   75.73   75.73
   63.35   62.88   75.73   75.73   62.85   62.57   81.72   75.13   74.07   70.39
       0       0       0       0       0       0       0       0       0       0
       0       0       0       0       0       0       0       0       0       0
       0       0       0   56.82   57.26   57.26   57.32   57.32   58.29   58.29
   58.32   58.32   58.56   58.46   58.46   58.44   58.44   57.87   57.87   57.86
   57.86   57.88       0       0       0       0       0       0       0       0
       0       0       0       0       0       0       0       0       0       0
Pier Skew, UpSta & Num, DnSta & Num=  ,4519.492, 2 ,4519.492, 2 , 0 , 0 , 0 ,,
    2.51    2.51
   38.95   59.12
    2.51    2.51
    38.5   58.67
Pier Skew, UpSta & Num, DnSta & Num=  ,4579.055, 2 ,4579.055, 2 , 0 , 0 , 0 ,,
    2.51    2.51
    28.4   59.56
    2.51    2.51
   27.95   59.11
BR Coef= 1 , 1 , 0 ,1.25, 0 ,,,0.8,0,1.2,0,
WSPro=,,,, 1 ,,,, 0 ,,,, 0 ,,,,-1 ,-1 ,-1 , 0 , 0 , 0 , 0 , 0
BC Design=,, 0 ,, 0 ,,,,,,
BC HTab HWMax=74.31
BC Use User HTab Curves=0
BC User HTab FreeFlow(D)= 0