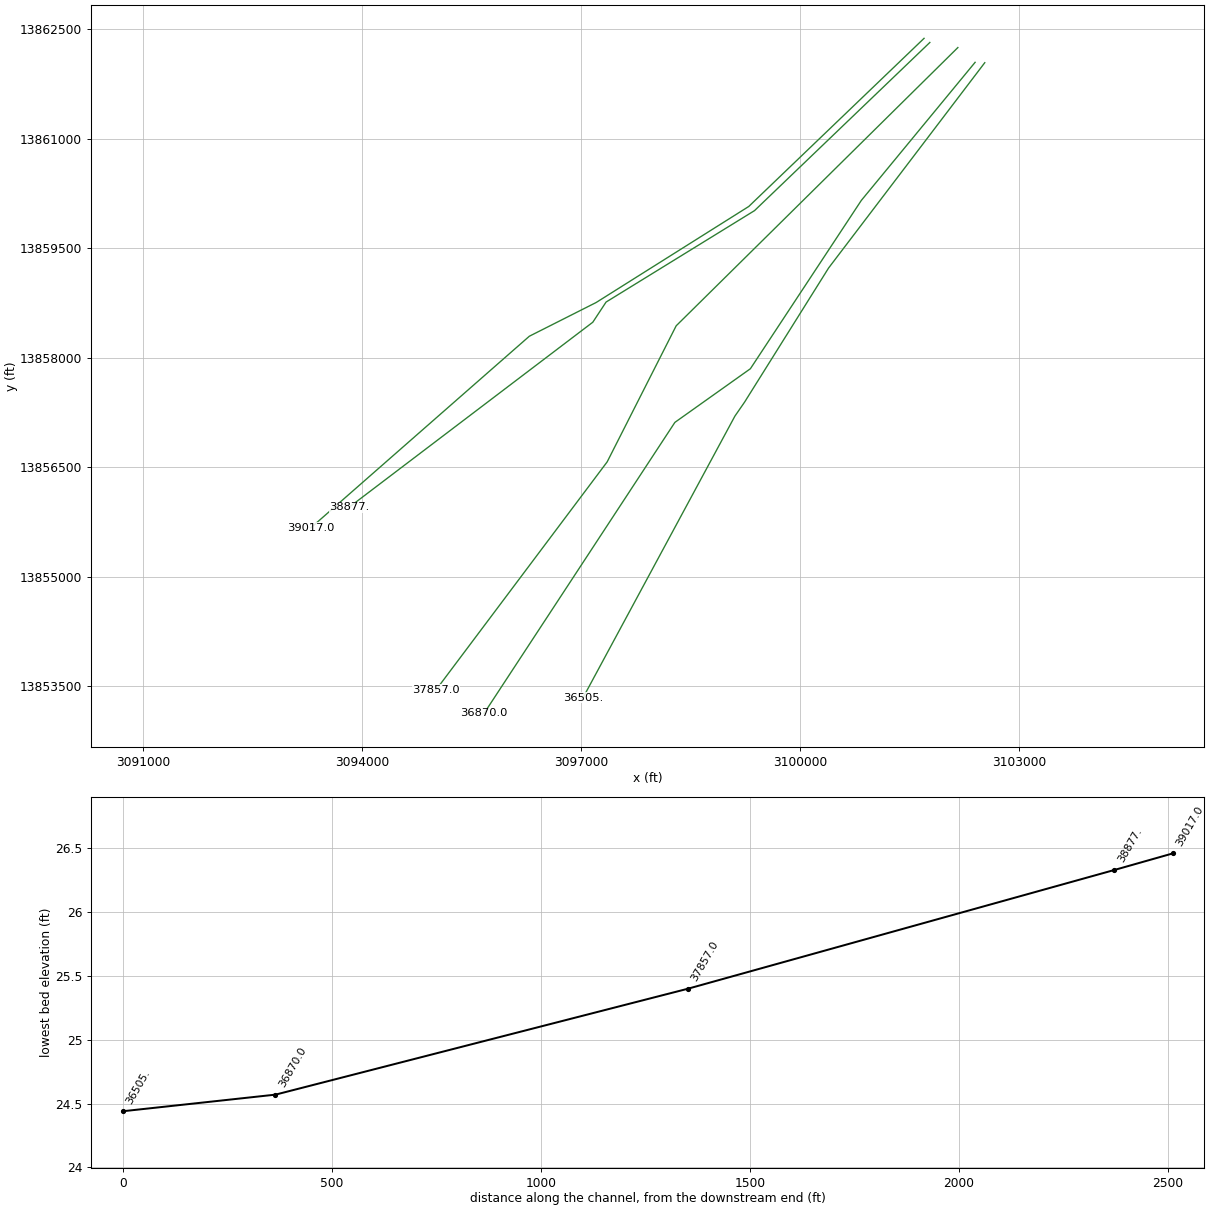
HEC-RAS study E100-00-00.prj: E100-00-00

--- E100-00-00.g02 (geometry) --- (continued)

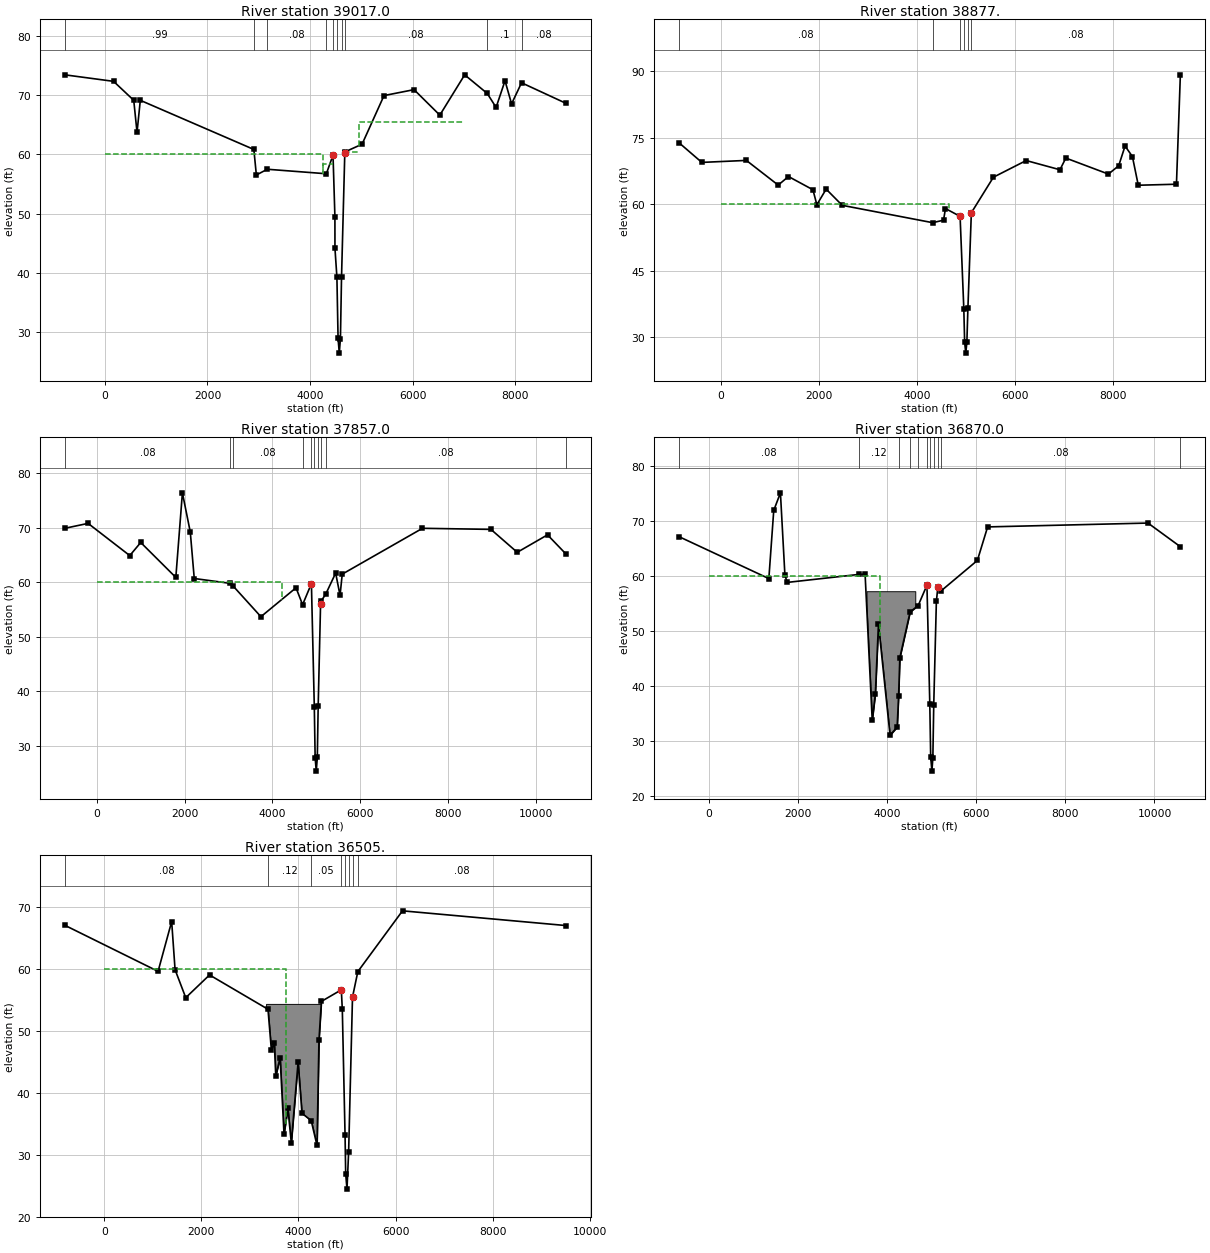
Type RM Length L Ch R = 1 ,39017.0 ,669.7,140,139
BEGIN DESCRIPTION:
Downstream Section of Bridge/Culvert/Weir
END DESCRIPTION:
XS GIS Cut Line= 5
      3101694.93     13862376.36      3099293.31      13860072.7
      3097203.67     13858757.59      3096288.11     13858295.52
      3093296.55     13855672.44
#Sta/Elev= 30
-778.706   73.41 170.742   72.31 563.566   69.11 627.514   63.71 691.463   69.11
 2903.43   60.822952.305   56.513165.526   57.484316.045   56.724445.769   59.87
4482.676   49.464483.498   44.15 4521.41   39.294544.159   28.944567.818   26.46
4590.292   28.924611.395   39.23 4675.16   60.194683.291   60.435011.984   61.71
5439.433   69.916024.103   70.916526.551   66.61 7010.73   73.417450.328   70.27
7622.806   67.917796.379   72.417924.276   68.518118.587   72.078982.526   68.61
#Mann= 10 ,-1 , 0
-778.706     .99       0 2903.43     .05       03165.526     .08       0
4316.045     .05       04445.769     .04       0 4521.41    .015       0
4611.395     .04       04683.291     .08       07450.328      .1       0
8118.587     .08       0
#XS Ineff= 4 ,-1
       0    4250   60.01    4250 4445.77   58.33 4675.16 4948.03    60.4
 4948.03    7000   65.53
Permanent Ineff=
       F       F       F       F
Bank Sta=4445.769,4675.16
XS Rating Curve= 0 ,0
Skew Angle= 24
Exp/Cntr=0.5,0.3

Type RM Length L Ch R = 1 ,38877.  ,1019,1020,1791.2
BEGIN DESCRIPTION:
Loop 610 EB Access Rd - D/S - XS 1
END DESCRIPTION:
XS GIS Cut Line= 5
      3101774.17     13862319.76      3099372.55      13860016.1
        3097339.     13858763.46      3097157.39     13858487.41
 3093820.4294807 13855953.476725
#Sta/Elev= 30
  -852.4   73.81  -392.4   69.43   517.6   69.88  1167.6    64.3  1377.6   66.24
  1877.6   63.25  1957.6   59.86  2147.6   63.39  2475.5   59.73    4322   55.81
  4545.5   56.37  4585.5      59  4883.9   57.24    4960   36.38 4976.85    28.8
 5000.23   26.33 5022.48   28.79  5043.9   36.51  5113.9   58.05  5564.3   66.08
  6234.3   69.85  6924.3   67.77  7044.3   70.41  7914.3   66.79  8124.3   68.67
  8254.3   73.13  8404.3   70.76  8524.3   64.27  9304.3    64.5  9384.3   89.22
#Mann= 6 ,-1 , 0
  -852.4     .08       0    4322     .05       0  4883.9     .04       0
    4960    .015       0  5043.9     .04       0  5113.9     .08       0
#XS Ineff= 2 , 0
       0    4650   60.01               0
Permanent Ineff=
       F       F
Bank Sta=4883.9,5113.9
XS Rating Curve= 0 ,0
Exp/Cntr=0.3,0.1

Type RM Length L Ch R = 1 ,37857.0 ,1155.1,987,879.6
BEGIN DESCRIPTION:
Cross Section E100-00-00-X26
Located At: DS 610 N.LOOP
END DESCRIPTION:
XS GIS Cut Line= 4
      3102157.88     13862249.88      3098299.39      13858438.1
      3097354.42     13856574.54      3095007.86     13853448.05
#Sta/Elev= 30
  -731.1    69.9  -201.1    70.8   748.9    64.9   998.9    67.3  1798.9    60.9
  1948.9    76.4  2128.9    69.2  2218.9    60.7  3040.6   59.81  3099.6   59.37
  3738.9    53.7  4538.9      59  4688.9    55.9    4890   59.76  4955.9   37.19
    4975   27.86  5000.3    25.4  5024.5   27.93    5044   37.26  5098.7   56.04
  5112.4    56.6  5212.7   57.77  5442.7    61.7  5542.7    57.6  5592.7    61.5
  7422.2    69.9  8982.2    69.7  9582.2    65.5 10272.2    68.7 10691.3    65.2
#Mann= 10 ,-1 , 0
  -731.1     .08       0  3040.6     .05       0  3099.6     .08       0
  4688.9     .05       0    4890     .04       0  4955.9    .015       0
    5044     .04       0  5112.4     .05       0  5212.7     .08       0
 10691.3     .99       0
#XS Ineff= 2 , 0
       0    4210   60.01               0
Permanent Ineff=
       F       F
Bank Sta=4890,5098.7
XS Rating Curve= 0 ,0
Exp/Cntr=0.3,0.1

Type RM Length L Ch R = 1 ,36870.0 ,229.7,365,427.4
BEGIN DESCRIPTION:
Cross Section E100-00-00-X25
Located At: 2ND US ELLA BLVD
END DESCRIPTION:
XS GIS Cut Line= 5
      3102394.16     13862047.66      3100835.69     13860156.21
      3099316.01     13857850.13       3098281.7     13857115.22
      3095667.73     13853128.76
#Sta/Elev= 30
  -667.3    67.2  1342.7    59.6  1452.7      72  1602.7    75.2  1702.7    60.3
  1752.7    58.9  3367.5   60.36  3503.5    60.4  3663.5    33.8  3733.5    38.6
  3803.5    51.3  4063.5    31.1  4223.5    32.6  4255.7   38.23  4283.5    45.2
  4514.5   53.54  4695.3    54.7    4892    58.4    4956   36.77  4975.8   27.13
  5003.4   24.57  5024.6   26.98  5044.6   36.65  5103.6   55.45  5136.4   58.01
  5207.7   57.35  6024.1    62.9  6254.1      69  9854.1    69.7 10581.1    65.4
#Mann= 11 ,-1 , 0
  -667.3     .08       0  3367.5     .12       0  4255.7     .05       0
  4514.5     .12       0  4695.3     .05       0    4892     .04       0
    4956    .015       0  5044.6     .04       0  5136.4     .05       0
  5207.7     .08       0 10581.1     .99       0
#XS Ineff= 2 , 0
       0    3830   60.01               0
Permanent Ineff=
       F       F
#Block Obstruct= 2 ,-1
    1000    1001      50    3535    4630    57.3
Bank Sta=4892,5136.4
XS Rating Curve= 0 ,0
Exp/Cntr=0.3,0.1

Type RM Length L Ch R = 1 ,36505.  ,32.4,187,286
BEGIN DESCRIPTION:
PL_28a - U/S - XS 4
END DESCRIPTION:
XS GIS Cut Line= 5
      3102526.45     13862042.54      3100387.31     13859230.01
      3099234.99      13857390.5      3099104.24     13857201.62
      3097022.89     13853342.19
#Sta/Elev= 30
  -810.5   67.11  1109.5   59.66  1389.5   67.72  1459.5   59.93  1679.5    55.4
  2169.5   59.08  3373.1   53.53  3443.1   46.93  3503.1   48.13  3533.1   42.76
  3623.1    45.7  3703.1   33.35  3783.1   37.51  3853.1   31.93  3993.1   44.95
  4073.1   36.71  4263.1   35.52  4383.1    31.5  4423.1   48.52  4473.1    54.8
  4883.1   56.67  4903.7   53.54    4960   33.27 4973.34   26.89    5000   24.44
  5033.7   30.42  5113.7    55.5  5223.4   59.62  6143.4   69.45  9508.3   67.07
#Mann= 8 ,-1 , 0
  -810.5     .08       0  3373.1     .12       0  4263.1     .05       0
  4883.1     .04       0    4960    .015       0  5033.7     .04       0
  5113.7     .05       0  5223.4     .08       0
#XS Ineff= 2 , 0
       0    3735   60.01               0
Permanent Ineff=
       F       F
#Block Obstruct= 1 ,-1
    3334    4483    54.4
Bank Sta=4883.1,5113.7
XS Rating Curve= 0 ,0
Exp/Cntr=0.5,0.3