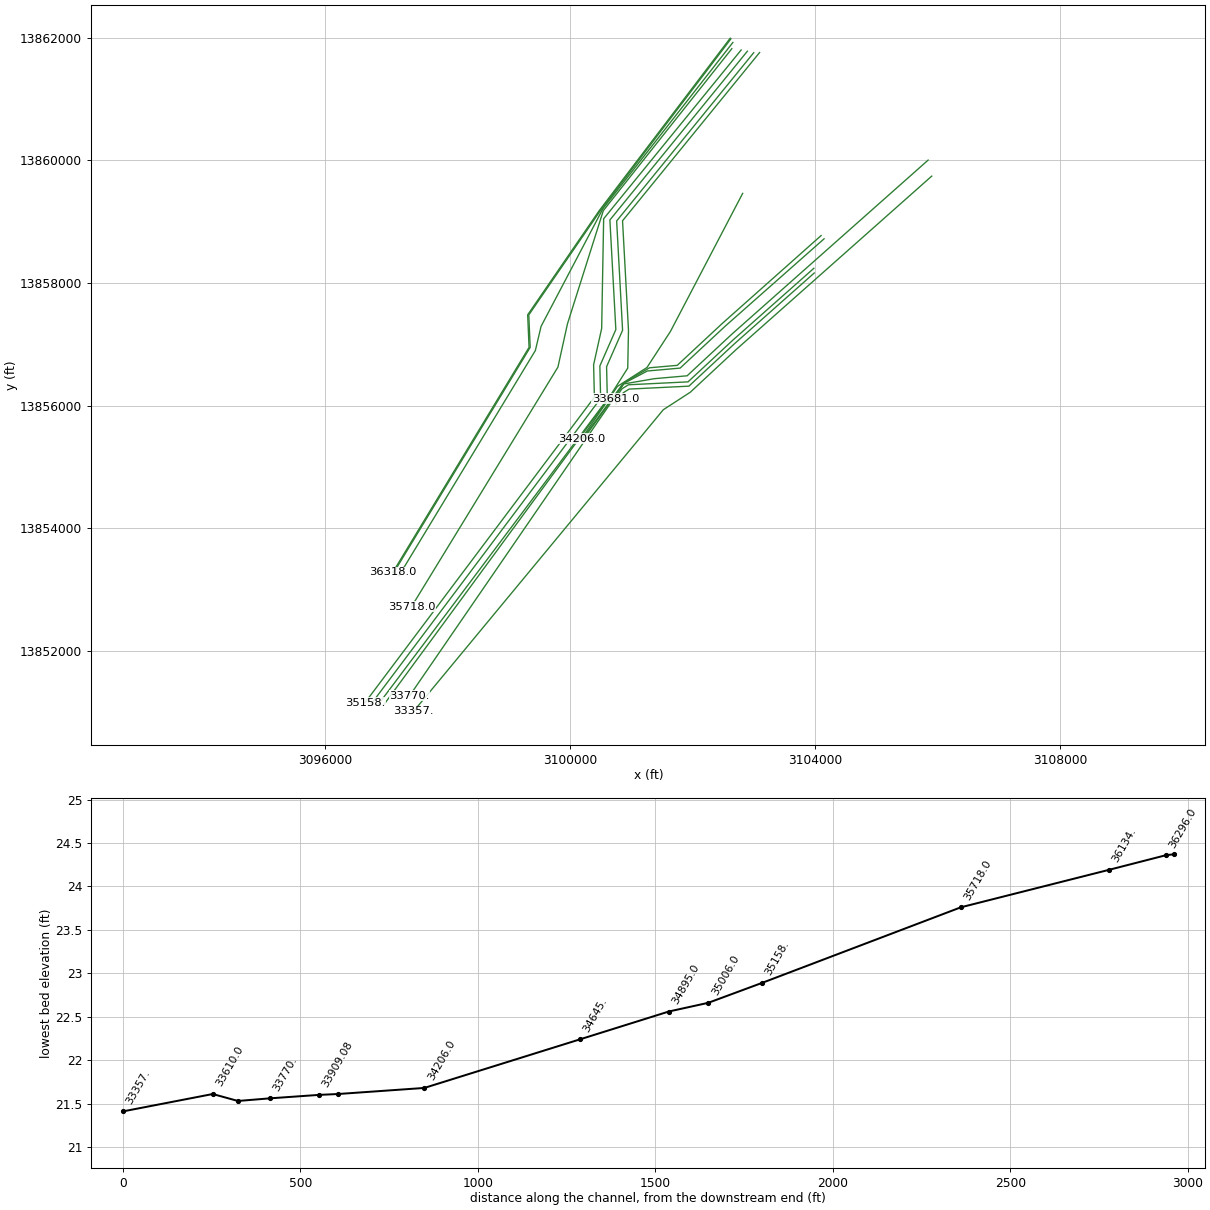
HEC-RAS study E100-00-00.prj: E100-00-00

--- E100-00-00.g02 (geometry) --- (continued)

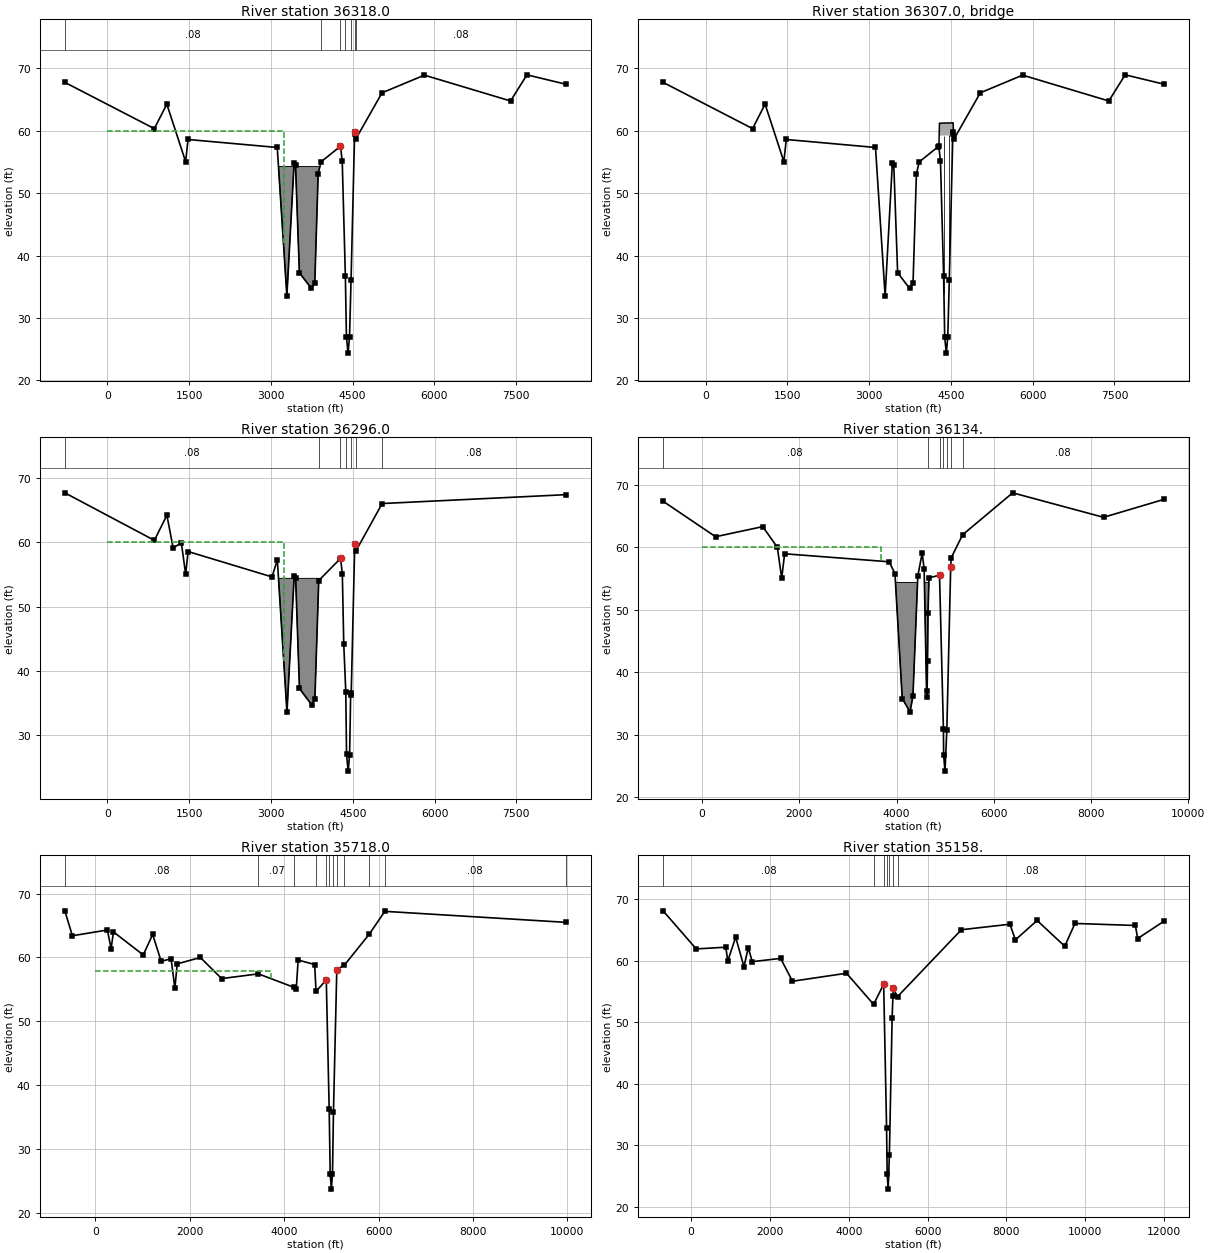
Type RM Length L Ch R = 1 ,36318.0 ,23,22,19.7
BEGIN DESCRIPTION:
Upstream Section of Bridge/Culvert/Weir
END DESCRIPTION:
XS GIS Cut Line= 5
      3102614.18     13861988.77      3100475.04     13859176.24
      3099309.87     13857481.53      3099332.58     13856951.66
      3097110.62     13853288.42
#Sta/Elev= 30
 -778.76   67.75 862.728   60.341092.294   64.261436.644   55.051480.791    58.6
3117.423   57.323294.011   33.533426.455   54.763452.943   54.473523.579   37.25
3744.316   34.733806.122   35.613867.928   53.143920.906   55.024270.199   57.47
4276.521   57.614309.279   55.134366.847   36.734386.538   26.984416.026   24.37
4442.957   26.894471.652   36.164536.813   59.784540.911   59.544556.098   58.65
  5039.6   66.085816.594   68.917397.069   64.777697.271   68.96 8408.31   67.46
#Mann= 7 ,-1 , 0
 -778.76     .08       03920.906     .05       04270.199     .04       0
4366.847    .015       04471.652     .04       04540.911     .05       0
4556.098     .08       0
#XS Ineff= 2 , 0
       0    3235   60.01               0
Permanent Ineff=
       F       F
#Block Obstruct= 1 ,-1
3073.7354008.354   54.26
Bank Sta=4276.521,4536.813
XS Rating Curve= 0 ,0
Skew Angle= 28
Exp/Cntr=0.5,0.3

Type RM Length L Ch R = 3 ,36307.0 ,,,
BEGIN DESCRIPTION:
PL1_E100-00-00-28a
Pipe has 28 degree skew.
END DESCRIPTION:
Bridge Culvert--1,0,-1,-1, 0
Deck Dist Width WeirC Skew NumUp NumDn MinLoCord MaxHiCord MaxSubmerge Is_Ogee
10,2,2.6,28, 21, 21, , , 0.95, 0, ,,,
 4280.05 4290.65 4309.28  4335.5 4359.17 4366.85 4372.59 4386.54 4387.42 4406.93
 4416.03 4422.56 4430.15 4442.96 4462.65 4471.65 4484.19 4516.68 4536.81 4540.91
 4551.02
   57.34   61.21   61.21   61.22   61.23   61.23   61.23   61.23   61.23   61.24
   61.24   61.24   61.24   61.25   61.25   61.25   61.25   61.26   61.27   61.27
   58.95
   55.34   59.21   59.21   59.22   59.23   59.23   59.23   59.23   59.23   59.24
   59.24   59.24   59.24   59.25   59.25   59.25   59.25   59.26   59.27
        
 4280.05 4290.65 4309.28  4335.5 4359.17 4366.85 4372.59 4386.54 4387.42 4406.93
 4416.03 4422.56 4430.15 4442.96 4462.65 4471.65 4484.19 4516.68 4536.81 4540.91
 4551.02
   57.34   61.21   61.21   61.22   61.23   61.23   61.23   61.23   61.23   61.24
   61.24   61.24   61.24   61.25   61.25   61.25   61.25   61.26   61.27   61.27
   58.95
   55.34   59.21   59.21   59.22   59.23   59.23   59.23   59.23   59.23   59.24
   59.24   59.24   59.24   59.25   59.25   59.25   59.25   59.26   59.27
        
Pier Skew, UpSta & Num, DnSta & Num=  ,4372.621, 2 ,4372.621, 2 , 0 , 0 , 0 ,,
     1.5     1.5
   35.29   60.23
     1.5     1.5
   35.29   60.23
Pier Skew, UpSta & Num, DnSta & Num=  ,4471.688, 2 ,4471.688, 2 , 0 , 0 , 0 ,,
     1.5     1.5
   35.19   60.25
     1.5     1.5
   35.19   60.25
BR Coef= 1 , 1 , 0 ,1.25, 0 ,,,0.8,-1,1.2,0,
WSPro=,,,, 1 ,,,, 0 ,,,, 0 ,,,,-1 ,-1 ,-1 , 0 , 0 , 0 , 0 , 0
BC Design=,, 0 ,, 0 ,,,,,,
BC HTab HWMax=68.96
BC Use User HTab Curves=0
BC User HTab FreeFlow(D)= 0

Type RM Length L Ch R = 1 ,36296.0 ,304.4,162,115
BEGIN DESCRIPTION:
Downstream Section of Bridge/Culvert/Weir
END DESCRIPTION:
XS GIS Cut Line= 5
      3102626.76     13861979.91      3100487.98     13859167.85
      3099327.88     13857480.52      3099350.56     13856951.44
      3097124.68     13853281.73
#Sta/Elev= 30
-779.289   67.74 862.728   60.331092.294   64.251207.078   59.141357.179   59.95
1436.644   55.041480.791   58.593020.299   54.633117.423   57.313294.011   33.52
3426.455   54.753452.943   54.463523.579   37.243744.316   34.723806.122    35.6
3876.758   54.074270.199   57.464276.521    57.64309.279   55.124335.502   44.17
4372.586   36.744386.538   26.974416.026   24.364442.957   26.884462.646   36.59
4471.652   36.154536.813   59.774556.098   58.64  5039.6   66.078405.308   67.45
#Mann= 7 ,-1 , 0
-779.289     .08       03876.758     .05       04270.199     .04       0
4372.586    .015       04471.652     .04       04556.098     .05       0
  5039.6     .08       0
#XS Ineff= 2 , 0
       0    3235   60.01               0
Permanent Ineff=
       F       F
#Block Obstruct= 1 ,-1
3120.0013971.339   54.41
Bank Sta=4276.521,4536.813
XS Rating Curve= 0 ,0
Skew Angle= 28
Exp/Cntr=0.5,0.3

Type RM Length L Ch R = 1 ,36134.  ,400.4,416,422.2
BEGIN DESCRIPTION:
PL_28a - D/S - XS 1
END DESCRIPTION:
XS GIS Cut Line= 5
      3102657.92     13861919.89      3100537.77     13859211.37
      3099528.42     13857294.11      3099435.46      13856900.5
      3097209.58     13853230.79
#Sta/Elev= 30
  -802.3    67.4   277.7   61.72  1247.7   63.34  1547.7   60.03  1637.7   55.09
  1697.7   58.99  3847.3   57.71  3967.3   55.82  4117.3   35.81  4277.3   33.68
  4337.3   36.18  4437.3   55.44  4527.3   59.09  4567.3   56.59  4617.3   37.07
  4627.3   36.02  4637.3   41.75  4647.3   49.43  4667.3   55.14  4884.1   55.56
  4964.1   30.94 4969.02   26.73 4996.59   24.19  5034.1   30.72  5114.1   56.95
  5124.1   58.34  5358.5   62.03  6388.5   68.75  8258.5   64.83  9500.5    67.7
#Mann= 7 ,-1 , 0
  -802.3     .08       0  4637.3     .05       0  4884.1     .04       0
  4964.1    .015       0  5034.1     .04       0  5124.1     .05       0
  5358.5     .08       0
#XS Ineff= 2 , 0
       0    3690   60.01               0
Permanent Ineff=
       F       F
#Block Obstruct= 1 ,-1
    3973    4669    54.4
Bank Sta=4884.1,5114.1
XS Rating Curve= 0 ,0
Exp/Cntr=0.3,0.1

Type RM Length L Ch R = 1 ,35718.0 ,577.9,560,559
BEGIN DESCRIPTION:
Cross Section E100-00-00-X24
Located At: US ELLA BLVD.
END DESCRIPTION:
XS GIS Cut Line= 5
       3102640.9     13861818.43      3100543.94     13859179.64
      3099959.06     13857334.76      3099803.62      13856630.1
       3097413.2     13852724.32
#Sta/Elev= 30
  -643.4    67.3  -483.4    63.4   256.6    64.3   336.6    61.4   386.6      64
  1016.6    60.4  1216.6    63.6  1396.6    59.4  1606.6    59.8  1686.6    55.2
  1736.6      59  2226.6      60  2676.6    56.7  3454.9   57.44  4215.4   55.31
  4257.1      55  4297.1    59.6  4647.1    58.9  4676.3    54.7  4893.2   56.48
  4954.8   36.26  4976.1   26.16  5000.4   23.76  5024.8   26.09  5045.3   35.87
  5116.1   58.12  5277.4   58.81  5804.9   63.66  6132.6   67.22  9963.3    65.5
#Mann= 12 ,-1 , 0
  -643.4     .08       0  3454.9     .07       0  4215.4     .12       0
  4676.3     .05       0  4893.2     .04       0  4954.8    .015       0
  5045.3     .04       0  5116.1     .05       0  5277.4     .08       0
  5804.9     .05       0  6132.6     .08       0  9963.3     .99       0
#XS Ineff= 2 , 0
       0    3720    57.9               0
Permanent Ineff=
       F       F
Bank Sta=4893.2,5116.1
XS Rating Curve= 0 ,0
Exp/Cntr=0.3,0.1

Type RM Length L Ch R = 1 ,35158.  ,252.7,152,105.7
BEGIN DESCRIPTION:
Ella Blvd. - U/S - XS 4
END DESCRIPTION:
XS GIS Cut Line= 6
      3102792.88      13861797.4      3100549.45     13859047.08
      3100517.11     13857260.17      3100385.72     13856668.37
      3100398.32     13856139.41      3096657.23     13851163.81
#Sta/Elev= 30
  -705.4   68.11   134.6   61.92   884.6    62.2   934.6   59.97  1134.6   63.82
  1344.6   59.03  1454.6   62.12  1554.6   59.85  2274.6   60.38  2574.6   56.67
  3943.9   57.97  4631.1   52.91 4886.51   56.18    4960   32.86 4975.41   25.32
 5000.32   22.89  5031.1   28.46  5101.1   50.77  5121.1   54.32  5131.1   55.49
  5237.3   54.16  6856.4   65.04  8086.4   65.93  8226.4    63.4  8776.4   66.54
  9476.4   62.36  9736.4   66.06 11266.4   65.73 11326.4   63.61 11991.5   66.42
#Mann= 7 ,-1 , 0
  -705.4     .08       0  4631.1     .05       0 4886.51     .04       0
    4960    .015       0  5031.1     .04       0  5121.1     .05       0
  5237.3     .08       0
#XS Ineff= 2 , 0
       0  3943.9    57.9               0
Permanent Ineff=
       F       F
Bank Sta=4886.51,5131.1
XS Rating Curve= 0 ,0
Exp/Cntr=0.5,0.3

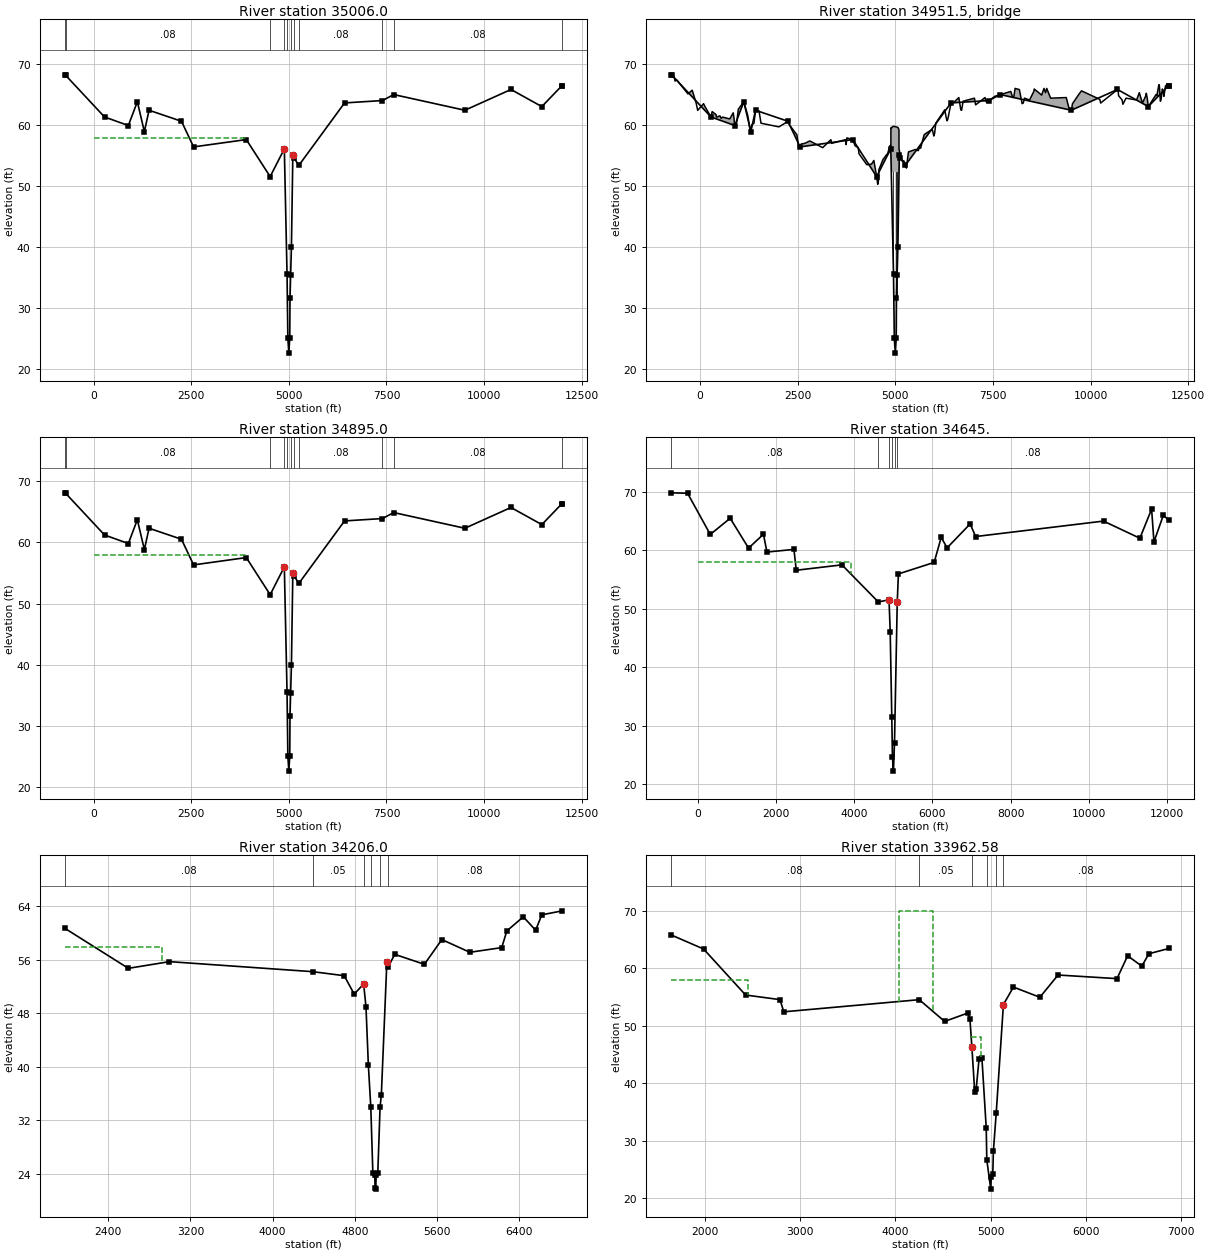
Type RM Length L Ch R = 1 ,35006.0 ,111.8,111,108.8
BEGIN DESCRIPTION:
Upstream Section of Bridge/Culvert/Weir
END DESCRIPTION:
XS GIS Cut Line= 6
      3102894.76     13861777.59      3100651.33     13859027.28
      3100748.47     13857241.45       3100487.6     13856648.56
      3100500.19      13856119.6      3096759.11       13851144.
#Sta/Elev= 30
  -738.3   68.22  -716.1   68.16   281.7   61.32   891.7   59.92  1121.7   63.82
  1301.7   58.92  1421.7   62.42  2251.7   60.62  2561.7   56.42    3911   57.62
  4521.9   51.56  4884.7    56.1    4954   35.59    4975    25.1  5000.3   22.66
  5023.8   25.19  5029.6   31.65  5045.8   35.45  5066.2   39.98  5102.2   55.06
  5123.3   54.66  5258.2   53.41  6426.3   63.62  7397.2   64.01  7685.2   64.99
  9506.3   62.42 10686.3   65.82 11476.3   63.02 11995.1   66.47 12001.4   66.42
#Mann= 11 ,-1 , 0
  -738.3     .99       0  -716.1     .08       0  4521.9     .05       0
  4884.7     .04       0    4954    .015       0  5045.8     .04       0
  5123.3     .05       0  5258.2     .08       0  7397.2     .05       0
  7685.2     .08       0 11995.1     .99       0
#XS Ineff= 3 ,-1
       0    3911    57.9    3911    4887   52.14    5100   12000   52.14
Permanent Ineff=
       F       F       F
Bank Sta=4884.7,5102.2
XS Rating Curve= 0 ,0
Exp/Cntr=0.5,0.3

Type RM Length L Ch R = 3 ,34951.5 ,,,
BEGIN DESCRIPTION:
ELLA
Structure ID: E100-00-00-28
Bridge has 14 degree skew with channel.
END DESCRIPTION:
Bridge Culvert--1,0,-1,-1, 0
Deck Dist Width WeirC Skew NumUp NumDn MinLoCord MaxHiCord MaxSubmerge Is_Ogee
10,89,2.6,0, 198, 198, , , 0.95, 0, ,,,
  -738.3  -716.1  -668.3  -638.3  -598.3  -308.3  -198.3   -98.3   -58.3    91.7
   121.7   281.7   311.7   411.7   421.7   511.7   541.7   581.7   761.7   851.7
   871.7   881.7   891.7   941.7   981.7  1121.7  1221.7  1281.7  1301.7  1321.7
  1381.7  1421.7  1511.7  1561.7  2021.7  2251.7  2291.7  2481.7  2521.7  2561.7
  2571.7  2581.7  2591.7  2681.7    2811    2961    3141    3351    3371    3721
    3741    3761    3911    3971    4051    4071    4271    4391    4451    4511
    4551    4571  4580.5  4599.4  4620.9  4629.4  4650.4  4685.2  4779.8  4795.6
  4836.7  4868.6  4884.7 4886.69  4886.8 4886.91  4890.8 4896.71  4896.8  4905.8
  4926.5  4944.1    4945    4954    4975  4992.8    4994  4996.6  5000.3  5002.2
    5006  5006.8  5012.7  5023.8  5029.6  5045.8  5055.6  5066.2  5071.6  5084.5
  5090.2 5094.29  5094.4 5094.51 5094.89    5095  5102.2  5120.8  5123.3  5123.8
  5173.2  5183.8  5218.2  5220.5  5221.5  5255.5  5258.2  5282.7  5337.2  5517.2
  5587.2  5627.2  5647.2  5737.2  5776.3  5946.3  5986.3  6006.3  6036.3  6266.3
  6306.3  6326.3  6346.3  6426.3  6496.3  6626.3  6676.3  6696.3  6736.3  7026.3
  7056.3  7296.3  7336.3  7397.2  7546.3  7685.2  7956.3  8006.3  8036.3  8066.3
  8176.3  8246.3  8276.3  8306.3  8436.3  8546.3  8556.3  8746.3  8806.3  8846.3
  8876.3  8976.3  9376.3  9456.3  9506.3  9536.3  9706.3  9766.3 10236.3 10256.3
 10686.3 10706.3 10716.3 10806.3 10826.3 10906.3 11176.3 11246.3 11326.3 11406.3
 11426.3 11456.3 11476.3 11676.3 11696.3 11746.3 11756.3 11766.3 11776.3 11786.3
 11806.3 11836.3 11856.3 11876.3 11916.3 11966.3 11995.1 12001.4
    68.2   68.14      68    67.2    67.4    65.1    65.7    63.6    62.4    63.5
    63.1    61.3    62.2    61.7    61.3    61.5    61.1    61.3      61      62
    61.1    60.3    59.9    60.5    62.6    63.8    61.6    59.2    58.9      60
    60.3    62.4    62.3    60.3    59.7    60.6      60    58.4    56.5    56.4
    56.7    56.6    56.9      57    57.4    56.9    56.3    57.6      57    57.6
    56.8    57.9    57.6    56.6    56.3    55.3    53.5    53.6    54.2      52
    50.3      51    52.7      53   53.34   53.48   53.81   54.36   55.17   55.17
   55.99   56.66   56.46   56.43   59.53   59.53   59.49   59.52   59.52   59.58
    59.7    59.8    59.8   59.79   59.77   59.75   59.75   59.75   59.74   59.74
   59.74   59.74   59.73    59.7   59.69   59.65   59.62   59.59   59.58   59.38
   59.29   59.18   59.18   56.08   56.07   56.07   55.86   55.34   55.27   55.26
    54.2   54.07   54.15   54.07   54.07    53.7   53.39   52.95    55.6      56
    55.8    56.5    56.2    58.4    58.6    59.3    58.2    58.6    60.3    62.5
    61.1    60.7      61    63.6    63.7    64.5    62.5    62.4    63.9    64.4
    63.3    64.5    63.7   63.99    64.7   64.97    65.5    64.5    64.7      66
    65.8    63.5    63.6    64.4    64.1    65.5    65.9    64.9      66    65.3
      66    64.4    64.5    62.5    62.4    63.5    65.1    65.6    64.2    63.6
    65.8    65.5    64.8    64.1    63.4    64.4    64.1    65.3    63.6    64.7
    65.2    64.1      63      65    64.8    66.6    66.6      66    64.7    63.9
    64.3    65.9    65.5    64.7    66.4    66.7   66.45    66.4
                                                                                
                                                                                
                                                                                
                                                                                
                                                                                
                                                                                
                                                                                
                                                                   52.22   52.18
    52.3    52.4    52.4   52.39   52.37   52.35   52.35   52.35   52.34   52.34
   52.34   52.34   52.33    52.3   52.29   52.25   52.22   52.19   52.18   51.98
   51.89   51.78   51.78
                                                                                
                                                                                
                                                                                
                                                                                
                                                                                
                                                                                
                                                                                
                                                                                
                                                                
  -738.3  -716.1  -668.3  -638.3  -598.3  -308.3  -198.3   -98.3   -58.3    91.7
   121.7   281.7   311.7   411.7   421.7   511.7   541.7   581.7   761.7   851.7
   871.7   881.7   891.7   941.7   981.7  1121.7  1221.7  1281.7  1301.7  1321.7
  1381.7  1421.7  1511.7  1561.7  2021.7  2251.7  2291.7  2481.7  2521.7  2561.7
  2571.7  2581.7  2591.7  2681.7    2811    2961    3141    3351    3371    3721
    3741    3761    3911    3971    4051    4071    4271    4391    4451    4511
    4551    4571  4580.5  4599.4  4620.9  4629.4  4650.4  4685.2  4779.8  4795.6
  4836.7  4868.6  4884.7 4886.69  4886.8 4886.91  4890.8 4896.71  4896.8  4905.8
  4926.5  4944.1    4945    4954    4975  4992.8    4994  4996.6  5000.3  5002.2
    5006  5006.8  5012.7  5023.8  5029.6  5045.8  5055.6  5066.2  5071.6  5084.5
  5090.2 5094.29  5094.4 5094.51 5094.89    5095  5102.2  5120.8  5123.3  5123.8
  5173.2  5183.8  5218.2  5220.5  5221.5  5255.5  5258.2  5282.7  5337.2  5517.2
  5587.2  5627.2  5647.2  5737.2  5776.3  5946.3  5986.3  6006.3  6036.3  6266.3
  6306.3  6326.3  6346.3  6426.3  6496.3  6626.3  6676.3  6696.3  6736.3  7026.3
  7056.3  7296.3  7336.3  7397.2  7546.3  7685.2  7956.3  8006.3  8036.3  8066.3
  8176.3  8246.3  8276.3  8306.3  8436.3  8546.3  8556.3  8746.3  8806.3  8846.3
  8876.3  8976.3  9376.3  9456.3  9506.3  9536.3  9706.3  9766.3 10236.3 10256.3
 10686.3 10706.3 10716.3 10806.3 10826.3 10906.3 11176.3 11246.3 11326.3 11406.3
 11426.3 11456.3 11476.3 11676.3 11696.3 11746.3 11756.3 11766.3 11776.3 11786.3
 11806.3 11836.3 11856.3 11876.3 11916.3 11966.3 11995.1 12001.4
    68.2   68.14      68    67.2    67.4    65.1    65.7    63.6    62.4    63.5
    63.1    61.3    62.2    61.7    61.3    61.5    61.1    61.3      61      62
    61.1    60.3    59.9    60.5    62.6    63.8    61.6    59.2    58.9      60
    60.3    62.4    62.3    60.3    59.7    60.6      60    58.4    56.5    56.4
    56.7    56.6    56.9      57    57.4    56.9    56.3    57.6      57    57.6
    56.8    57.9    57.6    56.6    56.3    55.3    53.5    53.6    54.2      52
    50.3      51    52.7      53   53.34   53.48   53.81   54.36   55.17   55.17
   55.99   56.66   56.46   56.43   59.53   59.53   59.49   59.52   59.52   59.58
    59.7    59.8    59.8   59.79   59.77   59.75   59.75   59.75   59.74   59.74
   59.74   59.74   59.73    59.7   59.69   59.65   59.62   59.59   59.58   59.38
   59.29   59.18   59.18   56.08   56.07   56.07   55.86   55.34   55.27   55.26
    54.2   54.07   54.15   54.07   54.07    53.7   53.39   52.95    55.6      56
    55.8    56.5    56.2    58.4    58.6    59.3    58.2    58.6    60.3    62.5
    61.1    60.7      61    63.6    63.7    64.5    62.5    62.4    63.9    64.4
    63.3    64.5    63.7   63.99    64.7   64.97    65.5    64.5    64.7      66
    65.8    63.5    63.6    64.4    64.1    65.5    65.9    64.9      66    65.3
      66    64.4    64.5    62.5    62.4    63.5    65.1    65.6    64.2    63.6
    65.8    65.5    64.8    64.1    63.4    64.4    64.1    65.3    63.6    64.7
    65.2    64.1      63      65    64.8    66.6    66.6      66    64.7    63.9
    64.3    65.9    65.5    64.7    66.4    66.7   66.45    66.4
                                                                                
                                                                                
                                                                                
                                                                                
                                                                                
                                                                                
                                                                                
                                                                   52.22   52.18
    52.3    52.4    52.4   52.39   52.37   52.35   52.35   52.35   52.34   52.34
   52.34   52.34   52.33    52.3   52.29   52.25   52.22   52.19   52.18   51.98
   51.89   51.78   51.78
                                                                                
                                                                                
                                                                                
                                                                                
                                                                                
                                                                                
                                                                                
                                                                                
                                                                
Pier Skew, UpSta & Num, DnSta & Num=  ,4949.1, 2 ,4949.1, 2 , 0 , 0 , 0 ,,
       3       3
   34.99    53.4
       3       3
   34.92   53.33
Pier Skew, UpSta & Num, DnSta & Num=  ,5029.6, 2 ,5029.6, 2 , 0 , 0 , 0 ,,
       3       3
   28.96   53.29
       3       3
   28.89   53.22
BR Coef= 1 , 1 , 0 ,1.25, 0 ,,,0.8,-1,1.2,0,
WSPro=,,,, 1 ,,,, 0 ,,,, 0 ,,,,-1 ,-1 ,-1 , 0 , 0 , 0 , 0 , 0
BR D #Sta/Elev= 198
  -738.3   68.12  -716.1   68.06  -668.3   67.92  -638.3   67.12  -598.3   67.32
  -308.3   65.02  -198.3   65.62   -98.3   63.52   -58.3   62.32    91.7   63.42
   121.7   63.02   281.7   61.22   311.7   62.12   411.7   61.62   421.7   61.22
   511.7   61.42   541.7   61.02   581.7   61.22   761.7   60.92   851.7   61.92
   871.7   61.02   881.7   60.22   891.7   59.82   941.7   60.42   981.7   62.52
  1121.7   63.72  1221.7   61.52  1281.7   59.12  1301.7   58.82  1321.7   59.92
  1381.7   60.22  1421.7   62.32  1511.7   62.22  1561.7   60.22  2021.7   59.62
  2251.7   60.52  2291.7   59.92  2481.7   58.32  2521.7   56.42  2561.7   56.32
  2571.7   56.62  2581.7   56.52  2591.7   56.82  2681.7   56.92    2811   57.32
    2961   56.82    3141   56.22    3351   57.52    3371   56.92    3721   57.52
    3741   56.72    3761   57.82    3911   57.52    3971   56.52    4051   56.22
    4071   55.22    4271   53.42    4391   53.52    4451   54.12    4511   51.92
    4551   50.22    4571   50.92  4580.5   51.49  4599.4   52.62  4620.9   53.05
  4629.4   53.22  4650.4   52.72  4685.2   53.35  4779.8   55.08  4795.6   55.08
  4836.7   55.07  4868.6   55.69  4884.7      56 4886.69   55.37  4886.8   55.33
 4886.91    55.3  4890.8   54.05 4896.71   52.17 4896.81   52.14  4905.8   49.27
  4926.5   42.01  4944.1   36.85    4945   36.59    4954   35.49    4975      25
  4992.8   24.59    4994   24.09  4996.6   22.57  5000.3   22.56  5002.2   22.58
    5006   24.11  5006.8   24.57  5012.7   24.75  5023.8   25.09  5029.6   31.55
  5045.8   35.35  5055.6   36.77  5066.2   39.88  5071.6   41.93  5084.5   46.84
  5090.2   49.45 5094.29   51.33  5094.4   51.38 5094.51   51.43 5094.89   51.61
    5095   51.66  5102.2   54.96  5120.8   54.59  5123.3   54.56  5123.8   54.56
  5173.2   53.98  5183.8   53.98  5218.2   53.98  5220.5   53.98  5221.5   53.98
  5255.5   53.36  5258.2   53.31  5282.7   52.87  5337.2   55.52  5517.2   55.92
  5587.2   55.72  5627.2   56.42  5647.2   56.12  5737.2   58.32  5776.3   58.52
  5946.3   59.22  5986.3   58.12  6006.3   58.52  6036.3   60.22  6266.3   62.42
  6306.3   61.02  6326.3   60.62  6346.3   60.92  6426.3   63.52  6496.3   63.62
  6626.3   64.42  6676.3   62.42  6696.3   62.32  6736.3   63.82  7026.3   64.32
  7056.3   63.22  7296.3   64.42  7336.3   63.62  7397.2   63.91  7546.3   64.62
  7685.2   64.89  7956.3   65.42  8006.3   64.42  8036.3   64.62  8066.3   65.92
  8176.3   65.72  8246.3   63.42  8276.3   63.52  8306.3   64.32  8436.3   64.02
  8546.3   65.42  8556.3   65.82  8746.3   64.82  8806.3   65.92  8846.3   65.22
  8876.3   65.92  8976.3   64.32  9376.3   64.42  9456.3   62.42  9506.3   62.32
  9536.3   63.42  9706.3   65.02  9766.3   65.52 10236.3   64.12 10256.3   63.52
 10686.3   65.72 10706.3   65.42 10716.3   64.72 10806.3   64.02 10826.3   63.32
 10906.3   64.32 11176.3   64.02 11246.3   65.22 11326.3   63.52 11406.3   64.62
 11426.3   65.12 11456.3   64.02 11476.3   62.92 11676.3   64.92 11696.3   64.72
 11746.3   66.52 11756.3   66.52 11766.3   65.92 11776.3   64.62 11786.3   63.82
 11806.3   64.22 11836.3   65.82 11856.3   65.42 11876.3   64.62 11916.3   66.32
 11966.3   66.62 11995.1   66.37 12001.4   66.32
BR D #Mann= 11
  -738.3     .99  -716.1     .08  4620.9     .05  4884.7     .04    4954    .015
  5045.8     .04  5123.3     .05  5258.2     .08  7397.2     .05  7685.2     .08
 11995.1     .99
BC Design=,, 0 ,, 0 ,,,,,,
BC HTab HWMax=68.22
BC Use User HTab Curves=0
BC User HTab FreeFlow(D)= 0

Type RM Length L Ch R = 1 ,34895.0 ,98.5,250,330.4
BEGIN DESCRIPTION:
Downstream Section of Bridge/Culvert/Weir
END DESCRIPTION:
XS GIS Cut Line= 6
       3102997.6     13861752.73      3100761.52     13859011.41
      3100858.41     13857230.03      3100597.35      13856636.7
      3100610.03     13856104.01      3096862.68     13851120.08
#Sta/Elev= 30
  -738.3   68.12  -716.1   68.06   281.7   61.22   891.7   59.82  1121.7   63.72
  1301.7   58.82  1421.7   62.32  2251.7   60.52  2561.7   56.32    3911   57.52
  4522.4   51.44  4884.7      56    4954   35.49    4975      25  5000.3   22.56
  5023.8   25.09  5029.6   31.55  5045.8   35.35  5066.2   39.88  5102.2   54.96
  5123.3   54.56  5258.2   53.31  6426.3   63.52  7397.2   63.91  7685.2   64.89
  9506.3   62.32 10686.3   65.72 11476.3   62.92 11995.1   66.37 12001.4   66.32
#Mann= 11 ,-1 , 0
  -738.3     .99       0  -716.1     .08       0  4522.4     .05       0
  4884.7     .04       0    4954    .015       0  5045.8     .04       0
  5123.3     .05       0  5258.2     .08       0  7397.2     .05       0
  7685.2     .08       0 11995.1     .99       0
#XS Ineff= 3 ,-1
       0    3880    57.9    3880    4887   52.14    5100   12000   52.14
Permanent Ineff=
       F       F       F
Bank Sta=4884.7,5102.2
XS Rating Curve= 0 ,0
Exp/Cntr=0.5,0.3

Type RM Length L Ch R = 1 ,34645.  ,803.6,439,215
BEGIN DESCRIPTION:
Ella Blvd. - D/S - XS 1
END DESCRIPTION:
XS GIS Cut Line= 6
      3103093.82     13861755.56      3100857.73     13859014.24
      3100954.63     13857232.86       3100942.6     13856613.96
      3100612.98     13856094.08       3096958.9     13851122.91
#Sta/Elev= 30
  -682.5    69.8  -262.5   69.73   317.5   62.69   827.5   65.45  1297.5   60.35
  1677.5   62.72  1767.5   59.68  2457.5   60.13  2517.5   56.57  3685.1   57.49
  4615.1   51.15  4889.2   51.52  4919.2   46.05    4960   31.45 4976.07   24.65
 5001.53   22.24  5029.2   27.09  5099.2   51.12  5129.2   55.94  6043.7   57.91
  6223.7    62.2  6373.7   60.39  6963.7   64.49  7103.7   62.33 10373.7   64.97
 11303.7   62.04 11603.7   67.01 11663.7   61.41 11903.7   65.98 12043.4   65.11
#Mann= 6 ,-1 , 0
  -682.5     .08       0  4615.1     .05       0  4889.2     .04       0
    4960    .015       0  5029.2     .04       0  5099.2     .08       0
#XS Ineff= 2 , 0
       0    3920    57.9               0
Permanent Ineff=
       F       F
Bank Sta=4889.2,5099.2
XS Rating Curve= 0 ,0
Exp/Cntr=0.3,0.1

Type RM Length L Ch R = 1 ,34206.0 ,619.4,243.42,47.9
BEGIN DESCRIPTION:
Cross Section E100-00-00-X23
Located At: DS ELLA BLVD.
END DESCRIPTION:
XS GIS Cut Line= 5
 3102817.896235813859460.7831871      3101638.73     13857210.23
      3101256.29     13856623.22      3100773.47     13856314.86
  3100190.536846 13855465.697501
#Sta/Elev= 30
  1976.1    60.7  2596.1    54.7  2996.1    55.7  4391.1    54.2  4696.8    53.6
  4794.3   50.85  4886.1   52.35  4908.9   48.99    4932   40.28    4956    33.9
  4975.8   24.15    4994   23.81  4997.8   21.88  5003.7   21.68  5008.2   23.72
  5024.1   24.12  5046.2   33.98  5058.5   35.77  5112.1   55.61  5125.6   54.95
  5189.3   56.79  5477.5    55.3  5647.5      59  5920.3    57.1  6230.3    57.8
  6280.3    60.3  6440.3    62.4  6560.3    60.4  6620.3    62.7  6820.3    63.3
#Mann= 6 ,-1 , 0
  1976.1     .08       0  4391.1     .05       0  4886.1     .04       0
    4956    .015       0  5046.2     .04       0  5125.6     .08       0
#XS Ineff= 2 , 0
       0    2920    57.9               0
Permanent Ineff=
       F       F
Bank Sta=4886.1,5112.1
XS Rating Curve= 0 ,0
Exp/Cntr=0.3,0.1

Type RM Length L Ch R = 1 ,33962.58,55,53.5,55
BEGIN DESCRIPTION:
Ineffective Area - building 15 feet tall and updated n values for the building and parking lot (PBS&J Sept 2009)
END DESCRIPTION:
XS GIS Cut Line= 6
  3104097.93487513858773.5490723 3102485.542724613857341.6378784
  3101750.69268813856658.6578979 3101298.618530313856619.0336914
 3100872.730285613856370.5128784 3100207.124084513855467.3131104
#Sta/Elev= 30
 1644.59   65.81 1985.63   63.36 2426.97   55.36 2788.07   54.56  2828.2   52.44
 4251.54   54.55 4517.76   50.77  4763.5   52.24 4783.97   51.15 4804.25   46.28
 4834.36   38.46 4849.42   39.01 4879.54   44.24 4909.65    44.4 4954.82   32.29
    4961   26.69  5002.7   21.61 5007.46   23.74 5023.98   24.31  5029.9   28.16
 5060.23   34.91 5135.51   53.71 5240.92   56.74 5518.56   54.97  5709.6   58.84
 6328.78   58.21 6440.58   62.18 6589.65   60.38 6664.18   62.54 6873.12   63.45
#Mann= 6 ,-1 , 0
 1644.59     .08       0 4251.54     .05       0 4804.25     .04       0
    4961    .015       0 5060.23     .04       0 5135.51     .08       0
#XS Ineff= 3 ,-1
       0    2450    57.9    4035    4400      70    4790    4897      48
Permanent Ineff=
       F       F       T
Bank Sta=4804.25,5135.51
XS Rating Curve= 0 ,0
Exp/Cntr=0.3,0.1

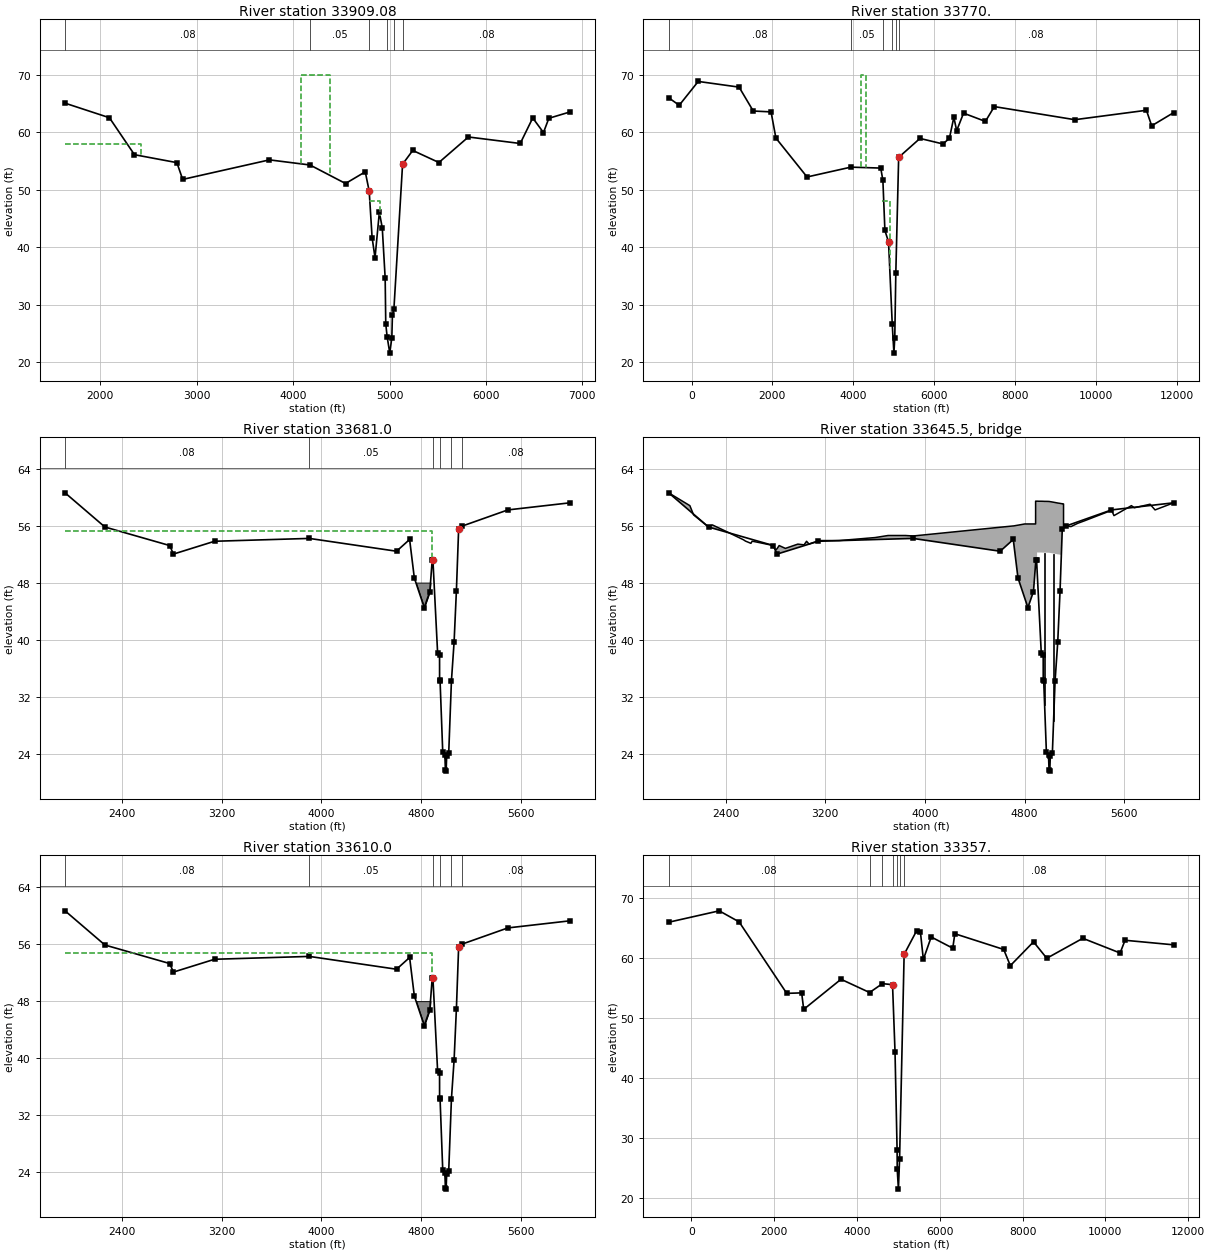
Type RM Length L Ch R = 1 ,33909.08,144,139.08,142
BEGIN DESCRIPTION:
Ineffective Area - building 15 feet tall and updated n values for the building and parking lot (PBS&J Sept 2009)
END DESCRIPTION:
XS GIS Cut Line= 6
  3104146.24548313858720.4074707 3102532.528076213857296.7127075
 3101797.678100613856613.7327271  3101263.07812513856566.5726929
 3100876.855102513856363.2944946  3100223.42529313855465.0786743
#Sta/Elev= 30
 1633.98   65.07 2094.05   62.54  2354.1   56.11 2794.17   54.73 2854.18   51.81
 3754.32   55.21 4175.04   54.32 4543.65    51.1 4748.43   53.13 4789.18   49.76
  4819.3    41.7 4849.42   38.18 4894.59    46.1 4924.71    43.4 4954.82   34.65
    4961   26.68 4974.99   24.49  5002.7    21.6 5023.98    24.3  5029.9   28.15
 5045.17   29.19 5135.52   54.46 5240.93   56.85 5512.32   54.75 5817.96   59.19
 6355.89   58.06 6485.74    62.5 6597.03   59.96 6652.68   62.44 6873.07   63.55
#Mann= 6 ,-1 , 0
 1633.98     .08       0 4175.04     .05       0 4789.18     .04       0
 4974.99    .015       0 5045.17     .04       0 5135.52     .08       0
#XS Ineff= 3 ,-1
       0    2420    57.9    4080    4380      70    4787    4901      48
Permanent Ineff=
       F       F       T
Bank Sta=4789.18,5135.52
XS Rating Curve= 0 ,0
Exp/Cntr=0.3,0.1

Type RM Length L Ch R = 1 ,33770.  ,84.2,89,106.8
BEGIN DESCRIPTION:
W 18th St - U/S - XS 4
Ineffective Area - building 15 feet tall and updated n values for the building and parking lot (PBS&J Sept 2009)
END DESCRIPTION:
XS GIS Cut Line= 6
      3105844.13     13860003.02      3102646.88     13857171.47
      3101912.03     13856488.49      3101377.43     13856441.33
      3100877.43     13856355.39      3097384.21     13851275.68
#Sta/Elev= 30
  -564.2   66.01  -304.2    64.7   165.8   68.85  1175.8   67.86  1525.8    63.7
  1965.8   63.55  2085.8   58.99  2855.8   52.22  3936.8   53.93  4676.6   53.77
  4729.9   51.67  4779.9   42.91  4869.9   40.92    4961   26.64  5002.7   21.56
 5023.98   24.26  5049.9   35.58  5119.9   55.63  5646.5   58.93  6213.9   57.97
  6373.9   58.94  6483.9   62.61  6553.9   60.28  6723.9   63.33  7263.9   61.89
  7483.9   64.47  9473.9   62.19 11243.9   63.83 11373.9   61.13 11918.8   63.43
#Mann= 6 ,-1 , 0
  -564.2     .08       0  3936.8     .05       0  4729.9     .04       0
    4961    .015       0  5049.9     .04       0  5119.9     .08       0
#XS Ineff= 2 ,-1
    4190    4315      70    4710    4900      48
Permanent Ineff=
       F       T
Bank Sta=4869.9,5119.9
XS Rating Curve= 0 ,0
Exp/Cntr=0.5,0.3

Type RM Length L Ch R = 1 ,33681.0 ,62.4,71,89.3
BEGIN DESCRIPTION:
Upstream Section of Bridge/Culvert/Weir
END DESCRIPTION:
XS GIS Cut Line= 6
 3103979.610425513858240.1817965      3102661.03     13857072.42
      3101926.18     13856389.45      3100953.59      13856341.9
       3100846.9     13856274.89 3100740.753478313856117.9648764
#Sta/Elev= 30
  1943.8    60.6  2263.8    55.8  2783.8    53.2  2813.8      52  3143.8    53.8
  3904.6    54.2  4604.6    52.4  4709.6   54.05  4747.4   48.65  4827.1   44.49
  4871.8   46.74    4891   51.16  4896.7   51.14  4934.4   38.09  4949.9   37.83
  4950.2   34.37    4954   34.22  4975.3   24.28  4992.5   23.78  4996.9   21.66
  5002.5   21.53  5007.2   23.68  5023.5   24.09  5045.2    34.2  5066.5   39.63
  5084.9   46.76  5103.2   55.59  5131.2   55.93  5497.9    58.2  5997.6    59.2
#Mann= 6 ,-1 , 0
  1943.8     .08       0  3904.6     .05       0  4896.7     .04       0
    4954    .015       0  5045.2     .04       0  5131.2     .08       0
#XS Ineff= 2 , 0
       0    4890   55.28    5103       0   55.28
Permanent Ineff=
       F       F
#Block Obstruct= 2 , 0
       0    4897      48               0
Bank Sta=4896.7,5103.2
XS Rating Curve= 0 ,0
Exp/Cntr=0.5,0.3

Type RM Length L Ch R = 3 ,33645.5 ,,,
BEGIN DESCRIPTION:
W 18TH
Structure ID: E100-00-00-27
END DESCRIPTION:
Bridge Culvert--1,0,-1,-1, 0
Deck Dist Width WeirC Skew NumUp NumDn MinLoCord MaxHiCord MaxSubmerge Is_Ogee
10,51,2.6,0, 99, 99, , , 0.95, 0, ,,,
  1943.8  2113.8  2143.8  2263.8  2293.8  2410.4  2413.8  2450.4  2470.4  2543.8
  2560.4  2603.8  2613.8  2660.4  2740.4  2750.4  2770.4  2780.4  2783.8  2800.4
  2813.8  2830.4  2880.4  2980.4  3030.4  3050.4  3070.4  3100.4  3143.8  3160.4
  3193.8  3253.8  3310.4  3313.8  3600.4  3704.6  3844.6  3904.6  4564.6  4604.6
  4616.6  4644.6  4707.9  4709.6  4714.4  4747.4  4801.5  4827.1  4871.8 4888.89
    4889 4889.11    4891  4896.7 4900.81  4900.9    4901  4914.4  4934.4  4949.9
  4950.2    4954  4961.4  4975.3  4992.5  4993.8  4996.7  4996.9  4999.7  5002.5
  5006.3  5007.2  5023.5  5033.2  5045.2  5048.1  5066.5  5084.9 5093.29  5093.4
  5093.5  5103.2 5112.99  5113.1 5113.21  5127.2  5131.2  5173.1  5204.6    5227
  5279.7  5477.9  5497.9  5517.9  5657.9  5681.6  5807.6  5847.6  5997.6
    60.6    58.8    57.5    55.8    56.1   55.14   55.11    54.8   54.63   54.01
   53.82   53.51   53.81   53.65   53.36   53.33   53.26   53.22   53.21   52.55
   52.76    53.2    52.8    53.4    53.3    53.8   53.41    53.6   53.82    53.9
    53.9    53.9    53.9    53.9   54.32   54.61   54.61   54.54    55.7   55.77
   55.79   55.84   55.95   55.95   55.96   56.06   56.23   56.23   56.23   56.23
   59.43   59.43   59.43   59.43   59.43   59.43   59.43   59.42   59.42   59.41
   59.41   59.41    59.4    59.4   59.39   59.39   59.39   59.39   59.38   59.37
   59.36   59.36   59.31   59.28   59.24   59.23   59.17   59.12   59.09   59.09
   59.09   59.07   59.04   59.04   55.84   55.95   55.94   55.86   56.13   56.32
   56.66      58    58.2    57.4    58.8    58.5      59    58.2    59.2
                                                                                
                                                                                
                                                                                
                                                                                
                                                                                
                                           52.23   52.23   52.22   52.22   52.21
   52.21   52.21    52.2    52.2   52.19   52.19   52.19   52.19   52.18   52.17
   52.16   52.16   52.11   52.08   52.04   52.03   51.97   51.92   51.89   50.86
                                                                                
                                                                        
  1943.8  2113.8  2143.8  2263.8  2293.8  2410.4  2413.8  2450.4  2470.4  2543.8
  2560.4  2603.8  2613.8  2660.4  2740.4  2750.4  2770.4  2780.4  2783.8  2800.4
  2813.8  2830.4  2880.4  2980.4  3030.4  3050.4  3070.4  3100.4  3143.8  3160.4
  3193.8  3253.8  3310.4  3313.8  3600.4  3704.6  3844.6  3904.6  4564.6  4604.6
  4616.6  4644.6  4707.9  4709.6  4714.4  4747.4  4801.5  4827.1  4871.8 4888.89
    4889 4889.11    4891  4896.7 4900.81  4900.9    4901  4914.4  4934.4  4949.9
  4950.2    4954  4961.4  4975.3  4992.5  4993.8  4996.7  4996.9  4999.7  5002.5
  5006.3  5007.2  5023.5  5033.2  5045.2  5048.1  5066.5  5084.9 5093.29  5093.4
  5093.5  5103.2 5112.99  5113.1 5113.21  5127.2  5131.2  5173.1  5204.6    5227
  5279.7  5477.9  5497.9  5517.9  5657.9  5681.6  5807.6  5847.6  5997.6
    60.6    58.8    57.5    55.8    56.1   55.14   55.11    54.8   54.63   54.01
   53.82   53.51   53.81   53.65   53.36   53.33   53.26   53.22   53.21   52.55
   52.76    53.2    52.8    53.4    53.3    53.8   53.41    53.6   53.82    53.9
    53.9    53.9    53.9    53.9   54.32   54.61   54.61   54.54    55.7   55.77
   55.79   55.84   55.95   55.95   55.96   56.06   56.23   56.23   56.23   56.23
   59.43   59.43   59.43   59.43   59.43   59.43   59.43   59.42   59.42   59.41
   59.41   59.41    59.4    59.4   59.39   59.39   59.39   59.39   59.38   59.37
   59.36   59.36   59.31   59.28   59.24   59.23   59.17   59.12   59.09   59.09
   59.09   59.07   59.04   59.04   55.84   55.95   55.94   55.86   56.13   56.32
   56.66      58    58.2    57.4    58.8    58.5      59    58.2    59.2
                                                                                
                                                                                
                                                                                
                                                                                
                                                                                
                                           52.23   52.23   52.22   52.22   52.21
   52.21   52.21    52.2    52.2   52.19   52.19   52.19   52.19   52.18   52.17
   52.16   52.16   52.11   52.08   52.04   52.03   51.97   51.92   51.89   50.86
                                                                                
                                                                        
Pier Skew, UpSta & Num, DnSta & Num=  ,4961.3, 2 ,4961.3, 2 , 0 , 0 , 0 ,,
       3       3
   29.22    53.2
       3       3
   29.31   53.29
Pier Skew, UpSta & Num, DnSta & Num=  ,5033.1, 2 ,5033.1, 2 , 0 , 0 , 0 ,,
       3       3
   27.52   53.08
       3       3
   27.61   53.17
BR Coef= 1 , 1 , 0 ,1.25, 0 ,,,0.8,-1,2,0,
WSPro=,,,, 1 ,,,, 0 ,,,, 0 ,,,,-1 ,-1 ,-1 , 0 , 0 , 0 , 0 , 0
BC Design=,, 0 ,, 0 ,,,,,,
BC HTab HWMax=60.6
BC Use User HTab Curves=0
BC User HTab FreeFlow(D)= 0

Type RM Length L Ch R = 1 ,33610.0 ,90.1,253,332.9
BEGIN DESCRIPTION:
Downstream Section of Bridge/Culvert/Weir
END DESCRIPTION:
XS GIS Cut Line= 6
 3103985.768815813858163.4017833      3102683.03     13857009.67
      3101940.42     13856319.48      3100964.74     13856271.78
      3100870.05     13856212.31 3100751.761998913856037.4348464
#Sta/Elev= 30
  1943.8   60.68  2263.8   55.88  2783.8   53.28  2813.8   52.08  3143.8   53.88
  3904.6   54.28  4604.6   52.48  4709.6   54.13  4747.4   48.73  4827.1   44.57
  4871.8   46.82    4891   51.24  4896.7   51.22  4934.4   38.17  4949.9   37.91
  4950.2   34.45    4954    34.3  4975.3   24.36  4992.5   23.86  4996.9   21.74
  5002.5   21.61  5007.2   23.76  5023.5   24.17  5045.2   34.28  5066.5   39.71
  5084.9   46.84  5103.2   55.67  5131.2   56.01  5497.9   58.28  5997.6   59.28
#Mann= 6 ,-1 , 0
  1943.8     .08       0  3904.6     .05       0  4896.7     .04       0
    4954    .015       0  5045.2     .04       0  5131.2     .08       0
#XS Ineff= 2 , 0
       0    4890    54.8    5103       0    54.8
Permanent Ineff=
       F       F
#Block Obstruct= 2 , 0
       0    4897      48               0
Bank Sta=4896.7,5103.2
XS Rating Curve= 0 ,0
Exp/Cntr=0.5,0.3

Type RM Length L Ch R = 1 ,33357.  ,1415.5,787,664.2
BEGIN DESCRIPTION:
W 18th St - D/S - XS 1
END DESCRIPTION:
XS GIS Cut Line= 6
      3105902.65     13859741.93      3102705.67     13856910.62
      3101963.06     13856220.43      3101523.07     13855935.57
      3097808.82     13851453.78       3097447.7     13851020.24
#Sta/Elev= 30
  -543.8   65.91   676.2   67.81  1156.2   65.97  2306.2   54.05  2666.2   54.13
  2716.2   51.38  3616.2    56.4  4306.7   54.19  4616.7   55.67  4860.5    55.5
  4920.5   44.34  4970.5   28.01 4974.19    24.7 5002.62   21.41  5030.5   26.39
  5140.5   60.55  5444.7   64.52  5534.7   64.21  5604.7   59.71  5794.7   63.45
  6314.7   61.58  6364.7   63.99  7544.7   61.37  7704.7   58.67  8264.7   62.64
  8584.7    59.9  9454.7   63.23 10354.7   60.78 10474.7    62.9 11649.7   62.14
#Mann= 7 ,-1 , 0
  -543.8     .08       0  4306.7     .05       0  4616.7     .08       0
  4860.5     .04       0  4970.5    .015       0  5030.5     .04       0
  5140.5     .08       0
Bank Sta=4860.5,5140.5
XS Rating Curve= 0 ,0
Exp/Cntr=0.3,0.1