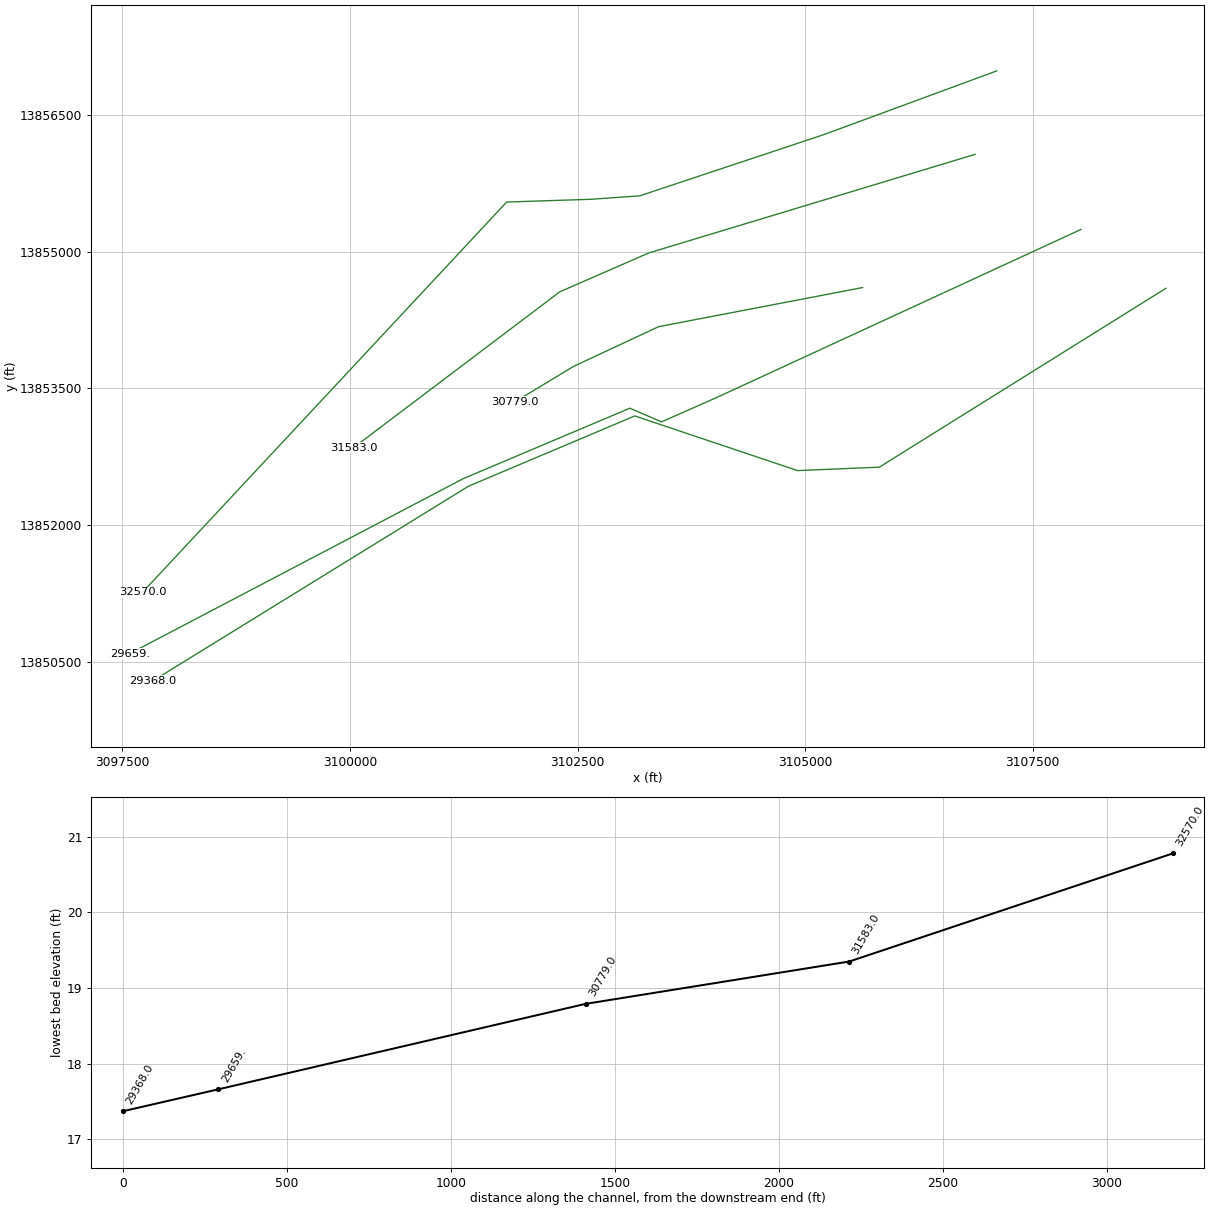
HEC-RAS study E100-00-00.prj: E100-00-00

--- E100-00-00.g02 (geometry) --- (continued)

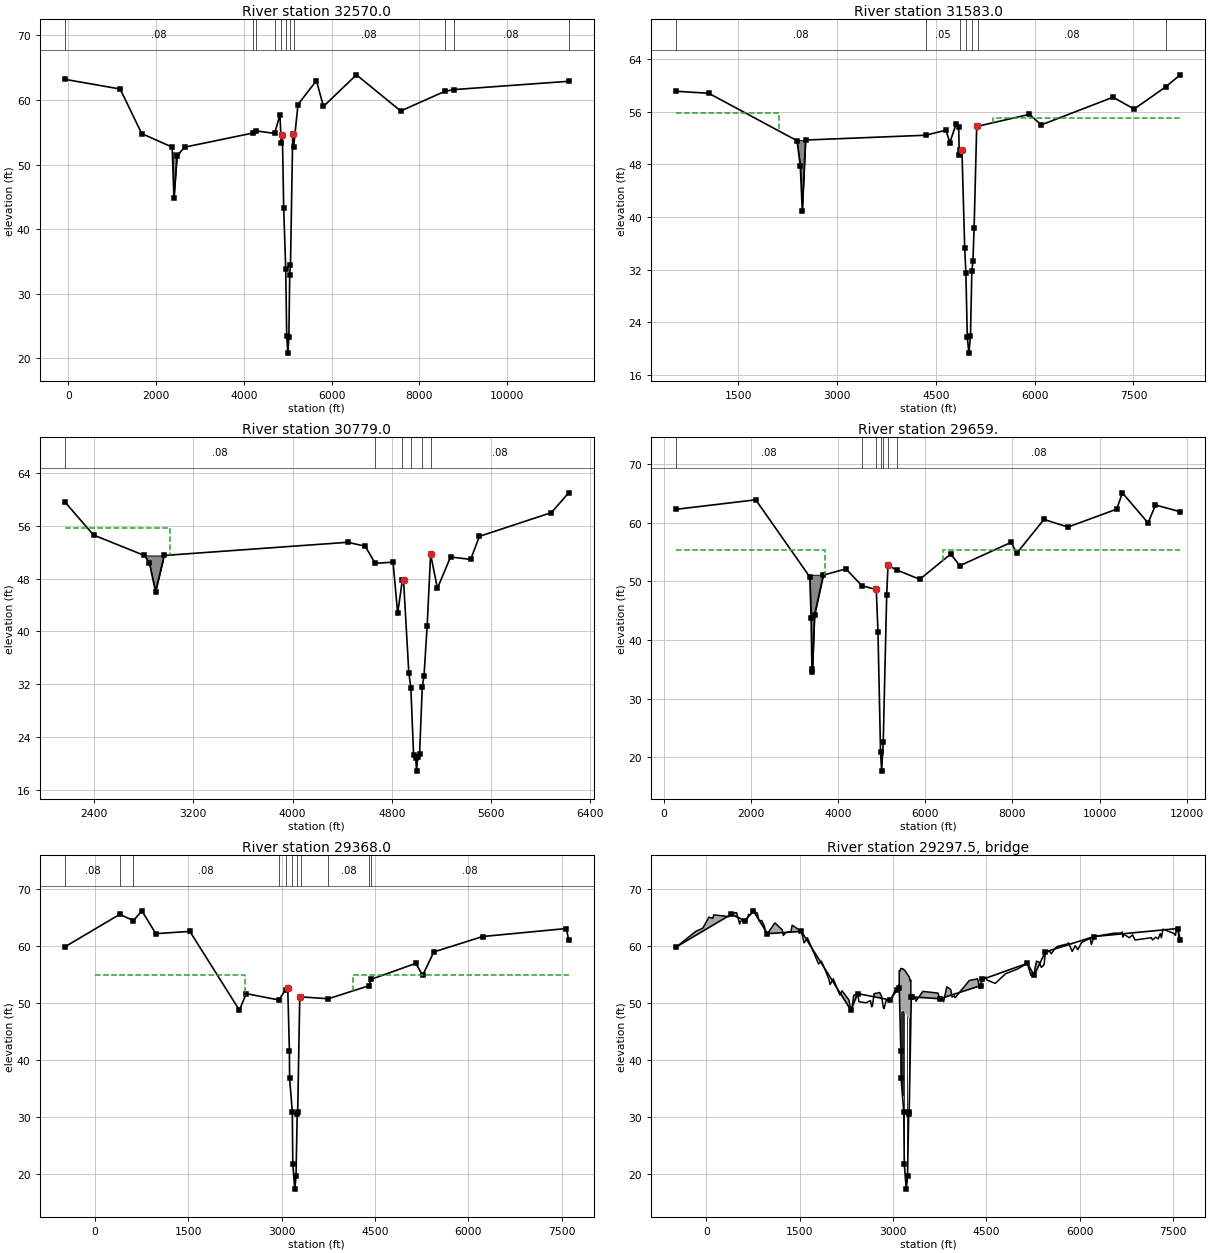
Type RM Length L Ch R = 1 ,32570.0 ,643.9,987,1040.1
BEGIN DESCRIPTION:
Cross Section E100-00-00-X22
Located At: DS W 18TH
END DESCRIPTION:
XS GIS Cut Line= 6
       3107104.1     13856983.11      3105206.86     13856284.69
      3103184.01     13855612.61      3102652.64     13855574.95
      3101722.03     13855544.57      3097724.06     13851264.54
#Sta/Elev= 30
   -74.9    63.2  1182.6    61.7  1672.6    54.8  2366.9    52.7  2406.9    44.8
  2476.9    51.4  2656.9    52.7  4218.4    54.9  4273.4  55.222  4698.5   54.82
  4821.5   57.66  4850.8   53.33  4877.5   54.51  4906.8   43.29  4953.2    33.8
  4975.8   23.43    5003   20.78  5024.8   23.32  5044.5   32.96  5061.8   34.49
    5113   54.73  5133.5    52.7  5232.5    59.3  5652.9      63  5812.9      59
  6562.9    63.9  7572.9    58.3  8572.5   61.33  8779.5   61.61 11399.7    62.9
#Mann= 11 ,-1 , 0
   -74.9     .08       0  4218.4     .05       0  4273.4     .12       0
  4698.5     .05       0  4850.8     .04       0  4953.2    .015       0
  5044.5     .04       0  5133.5     .08       0  8572.5     .05       0
  8779.5     .08       0 11399.7     .99       0
#Block Obstruct= 1 ,-1
 2303.93 2609.61   51.89
Bank Sta=4877.5,5113
XS Rating Curve= 0 ,0
Exp/Cntr=0.3,0.1

Type RM Length L Ch R = 1 ,31583.0 ,854.9,804,803
BEGIN DESCRIPTION:
Cross Section E100-00-00-X21
END DESCRIPTION:
XS GIS Cut Line= 4
  3106866.25535713856067.8346657      3103284.14      13854986.7
      3102305.79     13854559.78 3100039.126473213852848.8402158
#Sta/Elev= 30
   561.7    59.1  1051.7    58.8  2391.7    51.6  2441.7    47.8  2471.7      41
  2521.7    51.7  4347.5   52.43  4653.4    53.2  4712.1   51.32  4806.3   54.09
  4846.7   53.63  4855.6   49.37  4872.7   50.18  4896.3   50.15    4938   35.34
  4956.2   31.51  4977.3    21.8  5001.4   19.35  5025.7   21.91  5046.6   31.78
  5063.4   33.36  5081.1   38.38  5120.7   53.85  5133.6   53.79  5920.8    55.6
  6100.8      54  7190.8    58.2  7510.8    56.4  7991.9   59.79  8210.8    61.6
#Mann= 7 ,-1 , 0
   561.7     .08       0  4347.5     .05       0  4872.7     .04       0
  4956.2    .015       0  5046.6     .04       0  5133.6     .08       0
  7991.9     .05       0
#XS Ineff= 2 , 0
       0    2120    55.8  5370.8       0    55.1
Permanent Ineff=
       F       F
#Block Obstruct= 2 ,-1
    2390    2521    51.7    9000    9001      50
Bank Sta=4896.3,5120.7
XS Rating Curve= 0 ,0
Exp/Cntr=0.3,0.1

Type RM Length L Ch R = 1 ,30779.0 ,1121,1120,685.1
BEGIN DESCRIPTION:
Cross Section E100-00-00-X20
U/S W. TC Jester
END DESCRIPTION:
XS GIS Cut Line= 4
 3105630.677654713854606.3720212      3103390.87     13854177.34
      3102456.99     13853741.53 3101814.720667313853354.1263758
#Sta/Elev= 30
  2165.6    59.6  2395.6    54.6  2805.6    51.5  2845.6    50.4  2895.6      46
  2965.6    51.5  4446.1    53.5  4586.1    52.9  4666.1    50.3  4810.2   50.49
  4847.8   42.73    4885   47.71  4894.8   47.81  4937.7   33.66    4954   31.45
  4975.9   21.26  4992.7   20.75  5000.5   18.79  5008.1   20.95  5024.3   21.33
  5045.8   31.49    5060   33.26  5085.5   40.86  5113.3   51.68  5168.1   46.52
  5274.2   51.27  5436.1    50.9  5506.7    54.4  6086.7      58  6226.7      61
#Mann= 6 ,-1 , 0
  2165.6     .08       0  4666.1     .05       0    4885     .04       0
    4954    .015       0  5045.8     .04       0  5113.3     .08       0
#XS Ineff= 2 , 0
       0    3015   55.65    5865       0    55.1
Permanent Ineff=
       F       F
#Block Obstruct= 2 ,-1
    2807    2957    51.5    9000    9001      50
Bank Sta=4894.8,5113.3
XS Rating Curve= 0 ,0
Exp/Cntr=0.3,0.1

Type RM Length L Ch R = 1 ,29659.  ,1040.8,291,110
BEGIN DESCRIPTION:
TC Jester_2 - U/S - XS 4
END DESCRIPTION:
XS GIS Cut Line= 6
       3108029.1      13855243.8      3104045.46     13853407.94
      3103423.14     13853132.79      3103075.15      13853282.9
      3101249.67     13852512.29      3097584.29     13850591.76
#Sta/Elev= 30
   286.3   62.26  2106.3   63.87  3346.3   50.74  3376.3   43.73  3396.3   35.05
  3406.3   34.46  3456.3   44.25  3656.3   51.04  4176.3    52.1    4545   49.23
  4872.6    48.6  4912.6   41.31 4970.94   20.94 4996.84   17.66  5032.6   22.55
  5112.6   47.71  5142.6   52.69    5353   51.89    5872   50.33    6582   54.63
    6792   52.65  7973.5   56.64  8093.5   54.73  8723.5   60.53  9273.5   59.23
 10393.5   62.28 10523.5   65.06 11113.5   59.92 11283.5   62.99 11851.5   61.84
#Mann= 7 ,-1 , 0
   286.3     .08       0    4545     .05       0  4872.6     .04       0
 4970.94    .015       0  5032.6     .04       0  5142.6      .1       0
    5353     .08       0
#XS Ineff= 2 , 0
       0    3705    55.4    6400       0    55.4
Permanent Ineff=
       F       F
#Block Obstruct= 2 , 0
       0    3670    51.1               0
Bank Sta=4872.6,5142.6
XS Rating Curve= 0 ,0
Exp/Cntr=0.5,0.3

Type RM Length L Ch R = 1 ,29368.0 ,104.3,165,176.5
BEGIN DESCRIPTION:
Upstream Section of Bridge/Culvert/Weir
END DESCRIPTION:
XS GIS Cut Line= 6
       3108961.5     13854597.99      3105815.11     13852636.15
      3104917.09     13852598.48      3103128.92     13853198.01
      3101303.44     13852427.39      3097837.77     13850292.44
#Sta/Elev= 30
 -477.72   59.81 401.035   65.49 622.347    64.4 756.561   66.11 981.537   62.11
1527.906   62.512323.613   48.712432.887   51.612956.373    50.53064.426   52.27
3100.229   52.573126.648   41.553129.477   36.813172.928   30.943181.027   21.77
3212.974   17.373232.643   19.643251.734   30.573259.512   30.943293.065   51.04
3312.735   51.043751.823   50.714406.888      534433.756   54.095156.893   56.91
5266.167   54.815446.147   58.916230.349   61.617573.774   63.017612.534   61.01
#Mann= 11 ,-1 , 0
 -477.72     .08       0 401.035     .05       0 622.347     .08       0
2956.373     .05       03064.426     .04       03172.928    .015       0
3251.734     .04       03312.735      .1       03751.823     .08       0
4406.888     .12       04433.756     .08       0
#XS Ineff= 2 , 0
       0    2420   54.85    4140       0   54.85
Permanent Ineff=
       F       F
Bank Sta=3100.229,3293.065
XS Rating Curve= 0 ,0
Skew Angle= 50
Exp/Cntr=0.5,0.3

Type RM Length L Ch R = 3 ,29297.5 ,,,
BEGIN DESCRIPTION:
TC JESTER (SOUTH)
Structure ID: E100-00-00-26
Bridge deck is skew by 50 degrees with the channel.
END DESCRIPTION:
Bridge Culvert--1,0,-1,-1, 0
Deck Dist Width WeirC Skew NumUp NumDn MinLoCord MaxHiCord MaxSubmerge Is_Ogee
10,121,2.6,50, 189, 189, , , 0.95, 0, ,,,
-477.591-169.053 -53.351  43.067 107.346 120.201 370.888 401.035 403.028 415.884
 428.739  486.59 538.013 550.869 622.347 628.004 666.571 679.427  698.71 756.561
  820.84 846.551 891.546 936.542 949.397 981.5371103.6661219.3681238.6521277.219
1360.7811380.0651527.9061572.9011624.3241804.305  1849.31905.801 1970.081989.363
2040.7862143.632  2182.22291.4742323.6132336.4692368.6082432.887 2452.172567.101
2637.8082657.0912669.9472695.6592785.8422817.9812843.6922856.5482888.6882952.966
2956.3732959.3942964.215 2992.693022.9663023.8023042.0573045.2073053.0493059.733
3064.4263079.4033092.965 3099.133099.2013099.2713100.2293108.8423108.9133108.971
3110.1283114.8853123.9483126.6483129.4763137.3823141.2393141.8173151.845 3155.83
 3156.283172.9283181.0273189.9623192.5973209.1173212.9743216.9593218.7593222.166
3223.1943232.6433251.7343252.1843259.5123260.8623276.6743276.9963283.9313284.002
3286.2463286.3163286.3873289.2733293.0653312.7353320.4483332.2753336.1973336.903
3368.4643368.5353478.8953722.5123751.8233754.6513780.3633812.5023863.9253928.204
3947.4883986.0553998.9114223.8864358.8724391.0114406.8884410.294 4423.154433.756
4493.8574506.7134641.6984808.8234996.1965156.8935214.7435266.1675279.0225304.734
5349.7295381.8685426.8635446.1475516.8545542.5655606.8445645.411 5799.685818.964
5876.8145928.2385966.8056031.0836166.0696185.3536230.3486551.7426654.5886680.299
6693.1556706.0116796.0016847.4246885.9917149.5347168.8187220.2417258.8087290.947
7310.2317335.9427522.3517535.207 7554.497573.7747580.2027593.0587612.663
    59.8    62.5    63.1      65    64.8    65.4    65.1   65.48    65.5    65.2
    65.7    65.8    63.8    64.3   64.39    64.4    64.9    65.5    65.3    66.1
    65.7    64.4    64.4    63.4    62.4    62.1      64    62.8    61.8    62.3
    62.5    63.6    62.5    60.5    61.4    56.8    57.3    55.9    54.1    53.2
    54.2    51.4    52.1    50.5    48.7    48.7    51.3    51.6    50.2      50
    50.4    49.3    49.5    51.6    51.8    51.1    49.2      49    50.4    50.6
   50.49    50.4   50.53   51.24   51.98   51.99    52.1   52.12    52.2   52.37
   52.45   52.71   53.09   53.01   55.61   55.61    55.6   55.47   55.47   55.47
   55.52   55.69   56.01   56.01      56   55.99   55.98   55.98   55.97   55.96
   55.96   55.81   55.75   55.67   55.63   55.35   55.28   55.22   55.19   55.13
   55.11   54.96   54.65   54.64   54.52    54.5   53.79    53.8    53.9    53.9
   53.94   53.94   51.34   51.39   51.36   51.22   51.16   51.04   51.01      51
   50.72   50.29      52    51.7    50.7    50.6    51.1    50.2    52.8    52.3
      51    51.2    50.9    53.9    54.2    52.5   52.99    53.1      54   54.08
    54.5      54    53.4    55.1    55.9    56.9    54.8    54.8      56    57.3
    57.1    56.2    56.7    58.9      59    58.6    59.6    59.9    60.3    60.5
      59      60    59.3    60.6    61.3    60.2    61.6    62.2    62.2    62.4
    61.5      62    61.4    61.9      61    61.4      61    61.5    61.2    62.1
    61.4    62.9    62.1    61.8      63      63    62.5    60.7      61
                                                                                
                                                                                
                                                                                
                                                                                
                                                                                
                                                                                
                                                                                
                                                                   48.34   48.31
   48.17   48.34   48.66   48.66   48.65   48.64   48.63   48.63   48.62   48.61
   48.61   48.46    48.4   48.32   48.28      48   47.93   47.87   47.84   47.78
   47.76   47.61    47.3   47.29   47.17   47.15   46.44   46.45   46.55
                                                                                
                                                                                
                                                                                
                                                                                
                                                                                
                                                                                
                                                                                
                                                                        
-477.591-169.053 -53.351  43.067 107.346 120.201 370.888 401.035 403.028 415.884
 428.739  486.59 538.013 550.869 622.347 628.004 666.571 679.427  698.71 756.561
  820.84 846.551 891.546 936.542 949.397 981.5371103.6661219.3681238.6521277.219
1360.7811380.0651527.9061572.9011624.3241804.305  1849.31905.801 1970.081989.363
2040.7862143.632  2182.22291.4742323.6132336.4692368.6082432.887 2452.172567.101
2637.8082657.0912669.9472695.6592785.8422817.9812843.6922856.5482888.6882952.966
2956.3732959.3942964.215 2992.693022.9663023.8023042.0573045.2073053.0493059.733
3064.4263079.4033092.965 3099.133099.2013099.2713100.2293108.8423108.9133108.971
3110.1283114.8853123.9483126.6483129.4763137.3823141.2393141.8173151.845 3155.83
 3156.283172.9283181.0273189.9623192.5973209.1173212.9743216.9593218.7593222.166
3223.1943232.6433251.7343252.1843259.5123260.8623276.6743276.9963283.9313284.002
3286.2463286.3163286.3873289.2733293.0653312.7353320.4483332.2753336.1973336.903
3368.4643368.5353478.8953722.5123751.8233754.6513780.3633812.5023863.9253928.204
3947.4883986.0553998.9114223.8864358.8724391.0114406.8884410.294 4423.154433.756
4493.8574506.7134641.6984808.8234996.1965156.8935214.7435266.1675279.0225304.734
5349.7295381.8685426.8635446.1475516.8545542.5655606.8445645.411 5799.685818.964
5876.8145928.2385966.8056031.0836166.0696185.3536230.3486551.7426654.5886680.299
6693.1556706.0116796.0016847.4246885.9917149.5347168.8187220.2417258.8087290.947
7310.2317335.9427522.3517535.207 7554.497573.7747580.2027593.0587612.663
    59.8    62.5    63.1      65    64.8    65.4    65.1   65.48    65.5    65.2
    65.7    65.8    63.8    64.3   64.39    64.4    64.9    65.5    65.3    66.1
    65.7    64.4    64.4    63.4    62.4    62.1      64    62.8    61.8    62.3
    62.5    63.6    62.5    60.5    61.4    56.8    57.3    55.9    54.1    53.2
    54.2    51.4    52.1    50.5    48.7    48.7    51.3    51.6    50.2      50
    50.4    49.3    49.5    51.6    51.8    51.1    49.2      49    50.4    50.6
   50.49    50.4   50.53   51.24   51.98   51.99    52.1   52.12    52.2   52.37
   52.45   52.71   53.09   53.01   55.61   55.61    55.6   55.47   55.47   55.47
   55.52   55.69   56.01   56.01      56   55.99   55.98   55.98   55.97   55.96
   55.96   55.81   55.75   55.67   55.63   55.35   55.28   55.22   55.19   55.13
   55.11   54.96   54.65   54.64   54.52    54.5   53.79    53.8    53.9    53.9
   53.94   53.94   51.34   51.39   51.36   51.22   51.16   51.04   51.01      51
   50.72   50.29      52    51.7    50.7    50.6    51.1    50.2    52.8    52.3
      51    51.2    50.9    53.9    54.2    52.5   52.99    53.1      54   54.08
    54.5      54    53.4    55.1    55.9    56.9    54.8    54.8      56    57.3
    57.1    56.2    56.7    58.9      59    58.6    59.6    59.9    60.3    60.5
      59      60    59.3    60.6    61.3    60.2    61.6    62.2    62.2    62.4
    61.5      62    61.4    61.9      61    61.4      61    61.5    61.2    62.1
    61.4    62.9    62.1    61.8      63      63    62.5    60.7      61
                                                                                
                                                                                
                                                                                
                                                                                
                                                                                
                                                                                
                                                                                
                                                                   48.34   48.31
   48.17   48.34   48.66   48.66   48.65   48.64   48.63   48.63   48.62   48.61
   48.61   48.46    48.4   48.32   48.28      48   47.93   47.87   47.84   47.78
   47.76   47.61    47.3   47.29   47.17   47.15   46.44   46.45   46.55
                                                                                
                                                                                
                                                                                
                                                                                
                                                                                
                                                                                
                                                                                
                                                                        
Pier Skew, UpSta & Num, DnSta & Num=  ,3129.476, 2 ,3129.476, 2 , 0 , 0 , 0 ,,
     2.5     2.5
   35.81   49.65
     2.5     2.5
   35.81   49.65
Pier Skew, UpSta & Num, DnSta & Num=  ,3151.845, 2 ,3151.845, 2 , 0 , 0 , 0 ,,
     2.5     2.5
   31.91   49.62
     2.5     2.5
   31.91   49.62
Pier Skew, UpSta & Num, DnSta & Num=  ,3181.027, 2 ,3181.027, 2 , 0 , 0 , 0 ,,
     2.5     2.5
   20.63   49.41
     2.5     2.5
   20.63   49.41
Pier Skew, UpSta & Num, DnSta & Num=  ,3223.194, 2 ,3223.194, 2 , 0 , 0 , 0 ,,
     2.5     2.5
   18.56   48.78
     2.5     2.5
   18.56   48.78
Pier Skew, UpSta & Num, DnSta & Num=  ,3252.184, 2 ,3252.184, 2 , 0 , 0 , 0 ,,
     2.5     2.5
   29.36   48.31
     2.5     2.5
   29.36   48.31
BR Coef= 1 , 1 , 0 ,1.25, 0 ,,,0.8,0,2,0,
WSPro=,,,, 1 ,,,, 0 ,,,, 0 ,,,,-1 ,-1 ,-1 , 0 , 0 , 0 , 0 , 0
BC Design=,, 0 ,, 0 ,,,,,,
BC HTab HWMax=66.11
BC Use User HTab Curves=0
BC User HTab FreeFlow(D)= 0