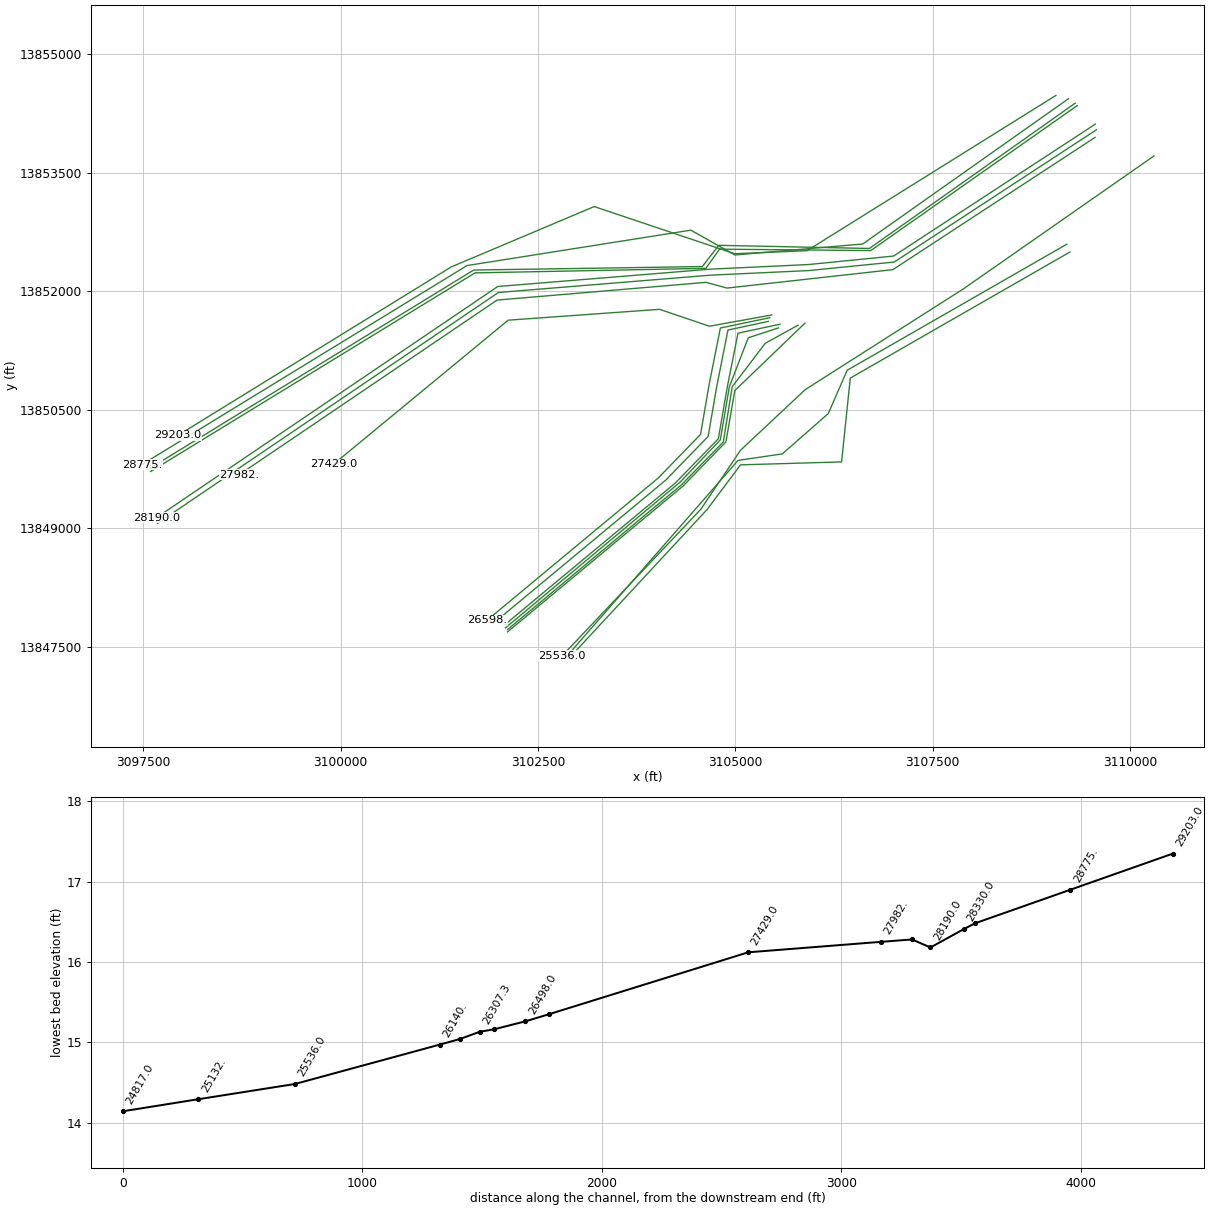
HEC-RAS study E100-00-00.prj: E100-00-00

--- E100-00-00.g02 (geometry) --- (continued)

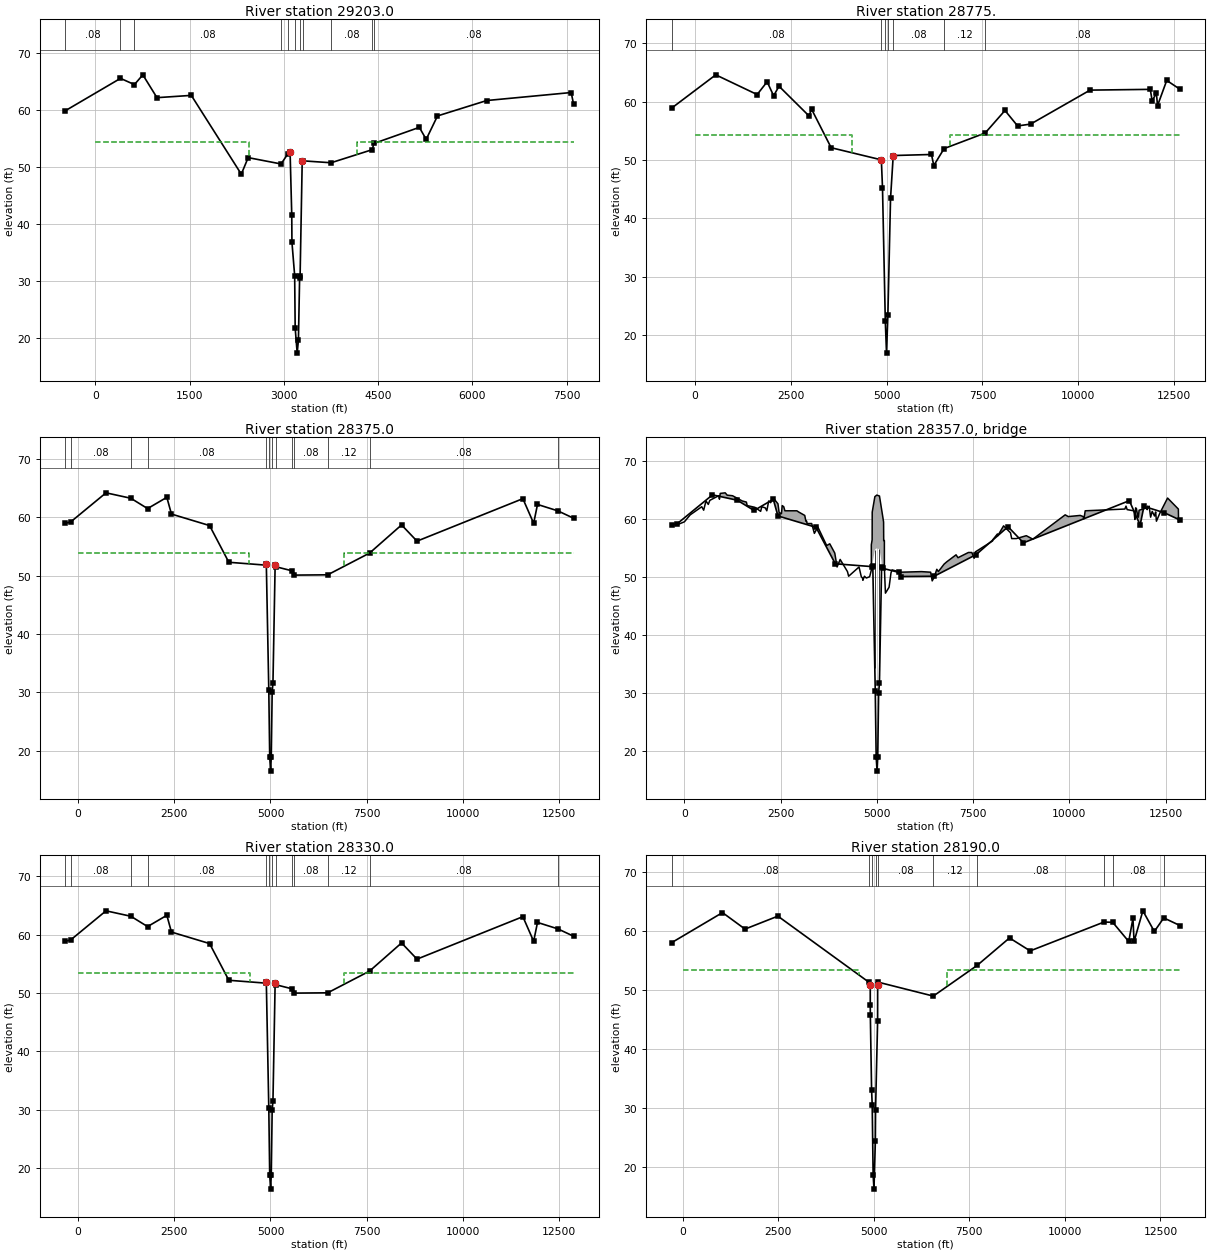
Type RM Length L Ch R = 1 ,29203.0 ,24.5,428,738.3
BEGIN DESCRIPTION:
Downstream Section of Bridge/Culvert/Weir
END DESCRIPTION:
XS GIS Cut Line= 6
      3109060.39     13854480.21      3105907.29     13852514.18
      3104991.39     13852475.76      3103211.81     13853073.06
      3101400.24     13852308.32      3097936.52     13850174.57
#Sta/Elev= 30
-478.941   59.79 401.035   65.47 622.347   64.38 756.561   66.09 981.537   62.09
1527.906   62.492323.613   48.692432.887   51.592956.373   50.483064.426   52.25
3100.229   52.553126.648   41.533129.477   36.793172.928   30.923181.027   21.75
3212.974   17.353232.643   19.623251.734   30.553259.512   30.923293.065   51.02
3312.735   51.023751.823   50.694406.888   52.984433.756   54.075156.893   56.89
5266.167   54.795446.147   58.896230.349   61.597573.774   62.997611.185   60.99
#Mann= 11 ,-1 , 0
-478.941     .08       0 401.035     .05       0 622.347     .08       0
2956.373     .05       03064.426     .04       03172.928    .015       0
3251.734     .04       03312.735      .1       03751.823     .08       0
4406.888     .12       04433.756     .08       0
#XS Ineff= 2 , 0
       0    2440   54.25    4165       0   54.25
Permanent Ineff=
       F       F
Bank Sta=3100.229,3293.065
XS Rating Curve= 0 ,0
Skew Angle= 50
Exp/Cntr=0.5,0.3

Type RM Length L Ch R = 1 ,28775.  ,19.3,400,401
BEGIN DESCRIPTION:
Bicycle Bridge - U/S - XS 4
END DESCRIPTION:
XS GIS Cut Line= 6
      3109219.55     13854438.36      3106612.83     13852598.97
      3104993.34      13852459.9      3104436.64     13852774.37
      3101600.16     13852325.91      3097483.73     13849806.83
#Sta/Elev= 30
  -606.5   58.89   543.5   64.59  1623.5   61.21  1883.5    63.4  2053.5      61
  2193.5   62.64  2973.9   57.56  3043.9   58.69  3553.9    52.1  4863.1   50.02
  4893.1   45.27 4966.34   22.41 4998.08    16.9  5033.1   23.36  5103.1   43.45
  5173.1   50.76  6171.2   50.94  6231.2   49.05    6500   51.95    7572   54.62
    8088   58.48    8418   55.83    8758   56.15   10308   61.97   11878    62.1
   11928   60.15   12038   61.45   12068   59.31   12308   63.63   12654   62.11
#Mann= 7 ,-1 , 0
  -606.5     .08       0  4863.1     .04       0 4966.34    .015       0
  5033.1     .04       0  5173.1     .08       0    6500     .12       0
    7572     .08       0
#XS Ineff= 2 , 0
       0    4110    54.3    6645       0    54.3
Permanent Ineff=
       F       F
Bank Sta=4863.1,5173.1
XS Rating Curve= 0 ,0
Exp/Cntr=0.5,0.3

Type RM Length L Ch R = 1 ,28375.0 ,46,45,28.4
BEGIN DESCRIPTION:
Upstream Section of Bridge/Culvert/Weir
END DESCRIPTION:
XS GIS Cut Line= 6
      3109304.45     13854381.76      3106697.73     13852542.37
      3104789.47     13852582.44      3104581.44     13852313.35
      3101685.06     13852269.31      3097568.63     13849750.23
#Sta/Elev= 30
  -332.5   58.94  -188.7   59.19   727.5   64.17  1372.5   63.24  1807.3   61.47
  2307.5    63.4  2427.5   60.53  3417.9   58.56  3917.9   52.27    4877   51.78
  4891.8   51.93  4956.1   30.35  4979.7   18.93  5003.1   16.48  5020.3   18.92
  5043.5   29.99  5064.2   31.62  5120.6   51.72  5148.1   51.49  5570.4   50.79
  5619.7   50.07  6485.9   50.12    7575   53.85    8405   58.67  8806.2   55.89
 11556.2   63.17 11836.2   58.95 11936.2   62.18   12465   61.08 12872.3   59.82
#Mann= 13 ,-1 , 0
  -332.5     .99       0  -188.7     .08       0  1372.5     .05       0
  1807.3     .08       0    4877     .04       0  4956.1    .015       0
  5043.5     .04       0  5148.1     .08       0  5570.4      .1       0
  5619.7     .08       0  6485.9     .12       0    7575     .08       0
   12465     .99       0
#XS Ineff= 2 , 0
       0    4450    53.9    6910       0    53.9
Permanent Ineff=
       F       F
Bank Sta=4891.8,5120.6
XS Rating Curve= 0 ,0
Exp/Cntr=0.5,0.3

Type RM Length L Ch R = 3 ,28357.0 ,,,
BEGIN DESCRIPTION:
BICYCLE BRIDGE
Structure ID: E100-00-00-25
END DESCRIPTION:
Bridge Culvert--1,0,-1,-1, 0
Deck Dist Width WeirC Skew NumUp NumDn MinLoCord MaxHiCord MaxSubmerge Is_Ogee
17.81,16,2.6,0, 171, 171, , , 0.95, 0, ,,,
  -221.3  -188.7    -1.3   148.7   448.7   498.7   558.7   618.7   658.7   888.7
   908.7   928.7  1058.7  1108.7  1248.7  1372.5  1498.7  1608.7  1628.7  1807.3
  1828.7  1978.7  2008.7  2058.7  2098.7  2138.7  2188.7  2238.7  2308.7  2428.7
  2458.7  2518.7  2538.7  2578.7  2608.7  2918.7  2964.3  3124.3  3154.3  3174.3
  3184.3  3304.3  3374.3  3464.3  3694.3  3774.3  3904.3  3964.3  4044.3  4234.3
  4264.3  4534.3  4594.3  4624.3  4634.3  4674.3  4724.3  4804.3  4814.1    4847
  4848.3  4853.4  4853.9  4874.3 4874.89    4875 4875.11    4877  4890.8 4890.91
    4891  4891.8  4944.2  4945.7  4956.1    4957  4979.7  4980.7  4992.1  4996.2
  4997.3  5003.1  5007.7  5019.2  5020.3  5043.5  5063.4  5064.2  5065.7  5113.4
 5120.09  5120.2  5120.3  5120.6  5148.1  5153.3  5168.2  5172.5  5175.3 5192.99
  5193.1 5193.21  5196.2  5214.9  5220.2  5314.9  5320.2  5364.9  5394.9  5570.4
  5604.9  5619.7  6154.9  6394.9  6434.9  6484.9  6485.9  6554.9  6594.9  6744.9
  6814.9  7054.9  7104.9  7374.9  7464.9  7524.9  7554.9    7575  8004.9  8009.7
  8129.7  8139.7  8289.7  8469.7  8499.7  8619.7  8879.7  9049.7  9889.7  9969.7
 10279.7 10359.7 10369.7 10379.7 10409.7 11439.7 11469.7 11499.7 11669.7 11679.7
 11699.7 11719.7 11739.7 11779.7 11789.7 11809.7 12009.7 12019.7 12029.7 12039.7
 12069.7 12109.7 12149.7 12209.7 12239.7 12259.7 12349.7   12465 12549.7 12829.7
 12835.7
   58.92   59.01   59.52   60.72   62.12   61.52   63.12   62.52   63.22   64.02
   63.42   64.42   64.52   64.12   64.02   63.57   63.12   62.92   62.32   62.05
   62.02   61.32   62.12   62.02   61.92   61.42   63.12   62.82   63.62   62.62
   61.12   60.92   62.32   62.12   61.42   61.42   61.22   60.62   59.62   59.62
   59.22   59.22   57.52   58.62   55.42   55.72   54.12   51.72   53.02   50.92
   50.12   51.72   50.02   49.82   49.42   50.12   49.82   50.02   50.13   51.01
   51.04   51.18   55.56   56.39   56.41   61.11   61.11   61.19   61.75   61.75
   61.76   61.79    63.8   63.86   63.92   63.92   64.04   64.05   64.11   64.13
   64.13   64.11    64.1   64.08   64.07   64.02   63.98   63.97   63.97   62.04
   61.76   61.76   61.76   61.74   60.54   60.31   59.66   59.47   56.28   56.28
   56.28   51.58   51.09   48.06    47.2   48.22   48.49   50.72   51.22   50.89
   50.82   50.82   50.92   50.82   49.32   49.92   49.94   51.32   50.92   52.22
   52.62   53.82   53.32   54.22   54.22   53.22   54.32    54.4   56.22   56.42
   57.42   57.12   58.82   57.62   56.62   56.62   57.12   56.52   60.72   60.42
   60.62   60.42   60.02   60.12   61.42   61.72   62.22   61.62   61.42   61.22
   59.92   61.92   61.82   60.32   60.32   61.52   61.92   61.62   62.22   61.92
   62.22   60.32   61.32   60.52   61.22   59.62   61.02   62.52   63.62   61.72
59.45924
                                                                                
                                                                                
                                                                                
                                                                                
                                                                                
                                                                                
                                                                           51.91
   52.58   52.61   54.62   54.68   54.74   54.74   54.86   54.87   54.93   54.95
   54.95   54.93   54.92    54.9   54.89   54.84    54.8   54.79   54.79   52.86
   52.58   51.66
                                                                                
                                                                                
                                                                                
                                                                                
                                                                                
                                                                                
                                                                                
        
  -221.3  -188.7    -1.3   148.7   448.7   498.7   558.7   618.7   658.7   888.7
   908.7   928.7  1058.7  1108.7  1248.7  1372.5  1498.7  1608.7  1628.7  1807.3
  1828.7  1978.7  2008.7  2058.7  2098.7  2138.7  2188.7  2238.7  2308.7  2428.7
  2458.7  2518.7  2538.7  2578.7  2608.7  2918.7  2964.3  3124.3  3154.3  3174.3
  3184.3  3304.3  3374.3  3464.3  3694.3  3774.3  3904.3  3964.3  4044.3  4234.3
  4264.3  4534.3  4594.3  4624.3  4634.3  4674.3  4724.3  4804.3  4814.1    4847
  4848.3  4853.4  4853.9  4874.3 4874.89    4875 4875.11    4877  4890.8 4890.91
    4891  4891.8  4944.2  4945.7  4956.1    4957  4979.7  4980.7  4992.1  4996.2
  4997.3  5003.1  5007.7  5019.2  5020.3  5043.5  5063.4  5064.2  5065.7  5113.4
 5120.09  5120.2  5120.3  5120.6  5148.1  5153.3  5168.2  5172.5  5175.3 5192.99
  5193.1 5193.21  5196.2  5214.9  5220.2  5314.9  5320.2  5364.9  5394.9  5570.4
  5604.9  5619.7  6154.9  6394.9  6434.9  6484.9  6485.9  6554.9  6594.9  6744.9
  6814.9  7054.9  7104.9  7374.9  7464.9  7524.9  7554.9    7575  8004.9  8009.7
  8129.7  8139.7  8289.7  8469.7  8499.7  8619.7  8879.7  9049.7  9889.7  9969.7
 10279.7 10359.7 10369.7 10379.7 10409.7 11439.7 11469.7 11499.7 11669.7 11679.7
 11699.7 11719.7 11739.7 11779.7 11789.7 11809.7 12009.7 12019.7 12029.7 12039.7
 12069.7 12109.7 12149.7 12209.7 12239.7 12259.7 12349.7   12465 12549.7 12829.7
 12835.7
   58.92   59.01   59.52   60.72   62.12   61.52   63.12   62.52   63.22   64.02
   63.42   64.42   64.52   64.12   64.02   63.57   63.12   62.92   62.32   62.05
   62.02   61.32   62.12   62.02   61.92   61.42   63.12   62.82   63.62   62.62
   61.12   60.92   62.32   62.12   61.42   61.42   61.22   60.62   59.62   59.62
   59.22   59.22   57.52   58.62   55.42   55.72   54.12   51.72   53.02   50.92
   50.12   51.72   50.02   49.82   49.42   50.12   49.82   50.02   50.13   51.01
   51.04   51.18   55.56   56.39   56.41   61.11   61.11   61.19   61.75   61.75
   61.76   61.79    63.8   63.86   63.92   63.92   64.04   64.05   64.11   64.13
   64.13   64.11    64.1   64.08   64.07   64.02   63.98   63.97   63.97   62.04
   61.76   61.76   61.76   61.74   60.54   60.31   59.66   59.47   56.28   56.28
   56.28   51.58   51.09   48.06    47.2   48.22   48.49   50.72   51.22   50.89
   50.82   50.82   50.92   50.82   49.32   49.92   49.94   51.32   50.92   52.22
   52.62   53.82   53.32   54.22   54.22   53.22   54.32    54.4   56.22   56.42
   57.42   57.12   58.82   57.62   56.62   56.62   57.12   56.52   60.72   60.42
   60.62   60.42   60.02   60.12   61.42   61.72   62.22   61.62   61.42   61.22
   59.92   61.92   61.82   60.32   60.32   61.52   61.92   61.62   62.22   61.92
   62.22   60.32   61.32   60.52   61.22   59.62   61.02   62.52   63.62   61.72
59.38924
                                                                                
                                                                                
                                                                                
                                                                                
                                                                                
                                                                                
                                                                           51.91
   52.58   52.61   54.62   54.68   54.74   54.74   54.86   54.87   54.93   54.95
   54.95   54.93   54.92    54.9   54.89   54.84    54.8   54.79   54.79   52.86
   52.58   51.66
                                                                                
                                                                                
                                                                                
                                                                                
                                                                                
                                                                                
                                                                                
        
Pier Skew, UpSta & Num, DnSta & Num=  ,4944.2, 2 ,4944.2, 2 , 0 , 0 , 0 ,,
     2.5     2.5
    32.9   55.67
     2.5     2.5
   32.85   55.62
Pier Skew, UpSta & Num, DnSta & Num=  ,5064.2, 2 ,5064.2, 2 , 0 , 0 , 0 ,,
     2.5     2.5
   30.37    55.8
     2.5     2.5
   30.32   55.75
BR Coef= 1 , 1 , 0 ,1.25, 0 ,,,0.8,0,1.2,0,
WSPro=,,,, 1 ,,,, 0 ,,,, 0 ,,,,-1 ,-1 ,-1 , 0 , 0 , 0 , 0 , 0
BC Design=,, 0 ,, 0 ,,,,,,
BC HTab HWMax=64.41
BC Use User HTab Curves=0
BC User HTab FreeFlow(D)= 0

Type RM Length L Ch R = 1 ,28330.0 ,171.3,140,74.5
BEGIN DESCRIPTION:
Downstream Section of Bridge/Culvert/Weir
END DESCRIPTION:
XS GIS Cut Line= 6
      3109329.73     13854350.93      3106715.05     13852515.57
      3104799.73     13852533.72      3104625.81     13852290.73
       3101702.1     13852233.37      3097592.33     13849718.37
#Sta/Elev= 30
  -332.5   58.87  -188.7   59.12   727.5    64.1  1372.5   63.17  1807.3    61.4
  2307.5   63.33  2427.5   60.46  3417.9   58.49  3917.9    52.2    4877   51.71
  4891.8   51.86  4956.1   30.28  4979.7   18.86  5003.1   16.41  5020.3   18.85
  5043.5   29.92  5064.2   31.55  5120.6   51.65  5148.1   51.42  5570.4   50.72
  5619.7      50  6485.9   50.05    7575   53.78    8405    58.6  8806.2   55.82
 11556.2    63.1 11836.2   58.88 11936.2   62.11   12465   61.01 12872.3   59.75
#Mann= 13 ,-1 , 0
  -332.5     .99       0  -188.7     .08       0  1372.5     .05       0
  1807.3     .08       0    4877     .04       0  4956.1    .015       0
  5043.5     .04       0  5148.1     .08       0  5570.4      .1       0
  5619.7     .08       0  6485.9     .12       0    7575     .08       0
   12465     .99       0
#XS Ineff= 2 , 0
       0    4460    53.5    6920       0    53.5
Permanent Ineff=
       F       F
Bank Sta=4891.8,5120.6
XS Rating Curve= 0 ,0
Exp/Cntr=0.5,0.3

Type RM Length L Ch R = 1 ,28190.0 ,78.9,77,76
BEGIN DESCRIPTION:
Upstream Section of Bridge/Culvert/Weir
END DESCRIPTION:
XS GIS Cut Line= 6
      3109559.28     13854116.68       3107003.9     13852446.33
      3105926.22     13852338.87        3104686.     13852280.79
      3101990.16     13852060.78       3097665.7     13849133.75
#Sta/Elev= 30
  -292.4   58.01  1037.6   63.11  1627.6   60.31  2487.6   62.51  4872.9   51.28
  4905.3   50.88  4905.4   47.47    4907   45.79  4939.7   33.05  4955.8   30.53
  4980.4   18.58  5002.4   16.18  5038.1   24.28  5043.6   29.58  5097.4   44.66
  5098.9   50.86  5101.3   51.32  6555.1   48.94  7703.2   54.15  8549.9   58.81
  9089.9   56.61 11024.7   61.51 11250.8   61.46 11669.9   58.21 11779.9   62.11
 11809.9   58.21 12039.9   63.41 12339.9   59.91   12587   62.21 13011.8   60.91
#Mann= 10 ,-1 , 0
  -292.4     .08       0  4872.9     .04       0  4955.8    .015       0
  5043.6     .04       0  5101.3     .08       0  6555.1     .12       0
  7703.2     .08       0 11024.7     .05       0 11250.8     .08       0
   12587     .99       0
#XS Ineff= 2 , 0
       0    4600    53.3    6925       0    53.3
Permanent Ineff=
       F       F
Bank Sta=4905.3,5098.9
XS Rating Curve= 0 ,0
Exp/Cntr=0.5,0.3

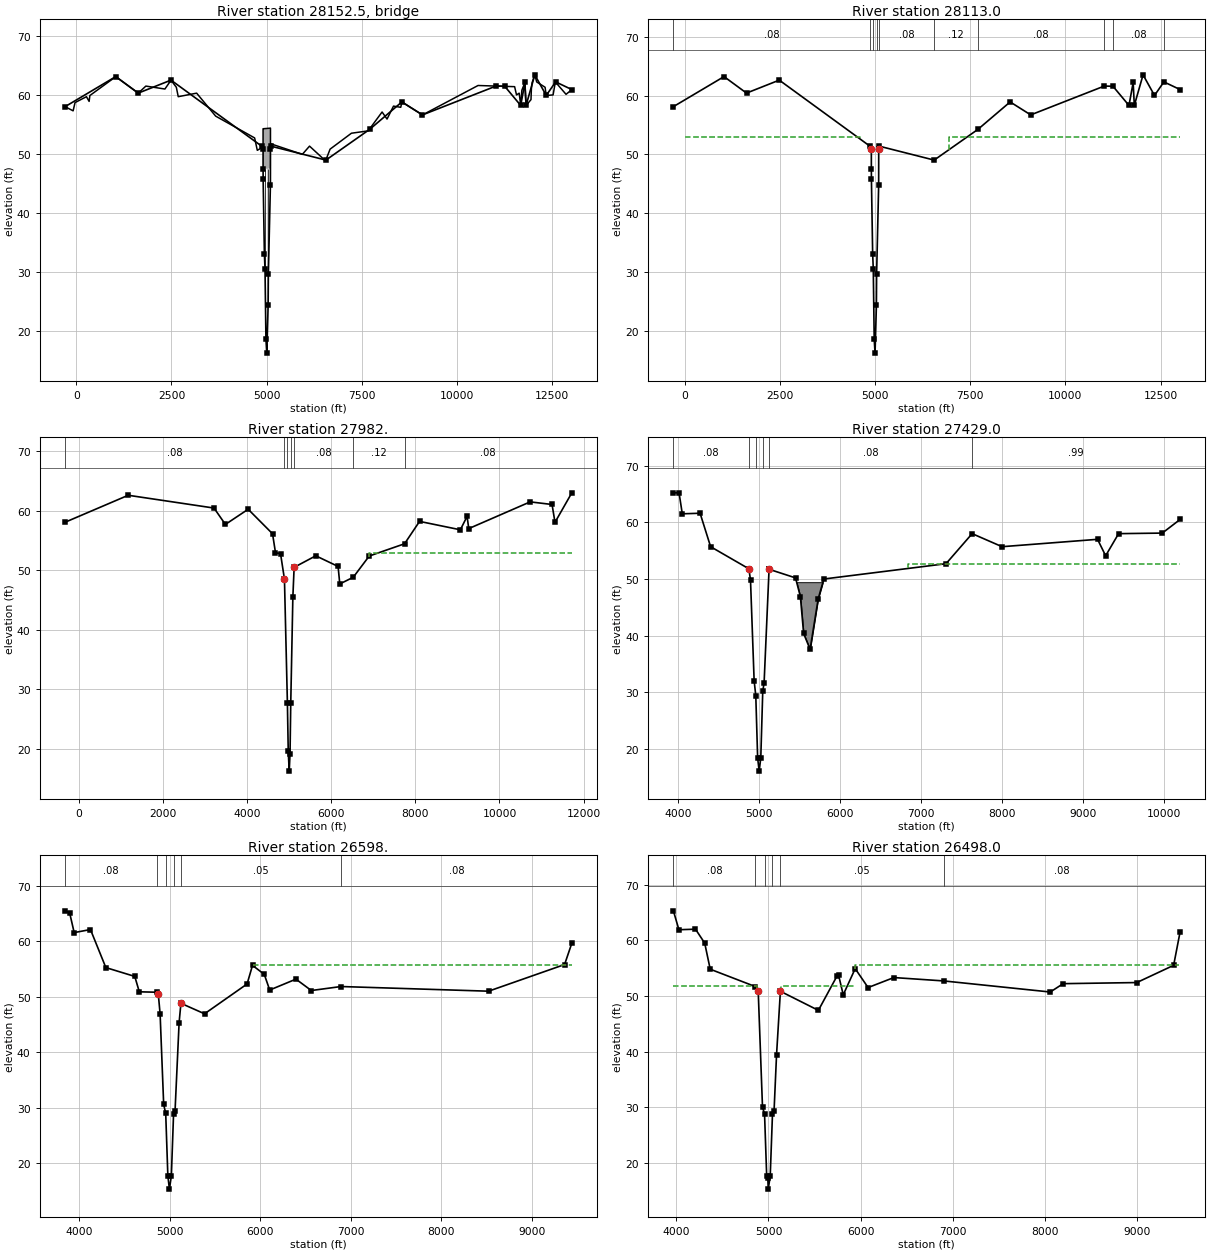
Type RM Length L Ch R = 3 ,28152.5 ,,,
BEGIN DESCRIPTION:
W 11TH   E100-00-00-24
Structure ID: E100-00-00-24
END DESCRIPTION:
Bridge Culvert--1,0,-1,-1, 0
Deck Dist Width WeirC Skew NumUp NumDn MinLoCord MaxHiCord MaxSubmerge Is_Ogee
10,55,2.6,0, 60, 60, , , 0.95, 0, ,,,
  -292.4   -82.4   -32.4   267.6   337.6   357.6  1037.6  1627.6  1827.6  2327.6
  2487.6  2627.6  2677.6  3160.5  3660.5  4683.5  4753.5 4904.69  4904.8 4904.91
  4905.3  4905.4  4905.5  5098.5  5098.9  5099.3 5099.41  5102.9  5127.9  5935.1
  6125.1  6545.1  6665.1  7225.1  7665.1  8029.9  8159.9  8329.9  8519.9  8549.9
  9089.9 10549.9 11509.9 11559.9 11629.9 11669.9 11699.9 11779.9 11809.9 11939.9
 11949.9 11969.9 12039.9 12089.9 12309.9 12339.9 12519.9 12579.9 12859.9 13011.8
      58    57.3    58.7    59.7    58.9    59.9    63.1    60.3    61.5      61
    62.5    61.3    59.7    60.3    56.4    52.7    50.6   51.16   54.26   54.26
   54.26   54.26   54.26   54.36   54.35   54.35   51.25   51.62   51.66   49.91
   51.31   48.81    50.8    53.5    53.9    57.1    55.9    58.1    57.9    58.8
    56.6    61.6    61.4      60    60.3    58.2    60.8    62.1    58.2    59.2
      61    62.1    63.4    62.2    61.3    59.9      60    62.2    60.1    60.9
      58    57.3    58.7    59.7    58.9    59.9    63.1    60.3    61.5      61
    62.5    61.3    59.7    60.3    56.4    52.7    50.6   50.88   50.88   50.88
   50.87   47.46   47.45    47.5   50.85   50.93   50.95   51.61   51.65    49.9
    51.3    48.8    50.8    53.5    53.9    57.1    55.9    58.1    57.9    58.8
    56.6    61.6    61.4      60    60.3    58.2    60.8    62.1    58.2    59.2
      61    62.1    63.4    62.2    61.3    59.9      60    62.2    60.1    60.9
  -292.4   -82.4   -32.4   267.6   337.6   357.6  1037.6  1627.6  1827.6  2327.6
  2487.6  2627.6  2677.6  3160.5  3660.5  4683.5  4753.5 4904.69  4904.8 4904.91
  4905.3  4905.4  4905.5  5098.5  5098.9  5099.3 5099.41  5102.9  5127.9  5935.1
  6125.1  6545.1  6665.1  7225.1  7665.1  8029.9  8159.9  8329.9  8519.9  8549.9
  9089.9 10549.9 11509.9 11559.9 11629.9 11669.9 11699.9 11779.9 11809.9 11939.9
 11949.9 11969.9 12039.9 12089.9 12309.9 12339.9 12519.9 12579.9 12859.9 13011.8
   58.11   57.41   58.81   59.81   59.01   60.01   63.21   60.41   61.61   61.11
   62.61   61.41   59.81   60.41   56.51   52.81   50.71   51.16   54.26   54.26
   54.26   54.26   54.26   54.36   54.35   54.35   51.25   51.72   51.76   50.01
   51.41   48.91   50.91   53.61   54.01   57.21   56.01   58.21   58.01   58.91
   56.71   61.71   61.51   60.11   60.41   58.31   60.91   62.21   58.31   59.31
   61.11   62.21   63.51   62.31   61.41   60.01   60.11   62.31   60.21   61.01
   58.11   57.41   58.81   59.81   59.01   60.01   63.21   60.41   61.61   61.11
   62.61   61.41   59.81   60.41   56.51   52.81   50.71   50.99   50.99   50.99
   50.98   47.57   47.56   47.61   50.96   51.04   51.06   51.72   51.76   50.01
   51.41   48.91   50.91   53.61   54.01   57.21   56.01   58.21   58.01   58.91
   56.71   61.71   61.51   60.11   60.41   58.31   60.91   62.21   58.31   59.31
   61.11   62.21   63.51   62.31   61.41   60.01   60.11   62.31   60.21   61.01
Pier Skew, UpSta & Num, DnSta & Num=  ,4966.3, 2 ,4966.3, 2 , 0 , 0 , 0 ,,
       3       3
    23.3   48.71
       3       3
   23.41   48.82
Pier Skew, UpSta & Num, DnSta & Num=  ,5038.1, 2 ,5038.1, 2 , 0 , 0 , 0 ,,
       3       3
   22.81   48.75
       3       3
   22.92   48.86
BR Coef= 1 , 1 , 0 ,1.25, 0 ,,,0.8,0,1.2,0,
WSPro=,,,, 1 ,,,, 0 ,,,, 0 ,,,,-1 ,-1 ,-1 , 0 , 0 , 0 , 0 , 0
BC Design=,, 0 ,, 0 ,,,,,,
BC HTab HWMax=63.41
BC Use User HTab Curves=0
BC User HTab FreeFlow(D)= 0

Type RM Length L Ch R = 1 ,28113.0 ,174.3,131,90.3
BEGIN DESCRIPTION:
Downstream Section of Bridge/Culvert/Weir
END DESCRIPTION:
XS GIS Cut Line= 6
      3109573.48     13854045.14      3107011.96     13852370.78
       3105926.2     13852262.51      3104685.69     13852204.41
      3101998.24     13851985.09      3097680.31     13849062.47
#Sta/Elev= 30
  -292.4   58.11  1037.6   63.21  1627.6   60.41  2487.6   62.61  4872.9   51.38
  4905.3   50.98  4905.4   47.57    4907   45.89  4939.7   33.15  4955.8   30.63
  4980.4   18.68  5002.4   16.28  5038.1   24.38  5043.6   29.68  5097.4   44.76
  5098.9   50.96  5101.3   51.42  6555.1   49.04  7703.2   54.25  8549.9   58.91
  9089.9   56.71 11024.7   61.61 11250.8   61.56 11669.9   58.31 11779.9   62.21
 11809.9   58.31 12039.9   63.51 12339.9   60.01   12587   62.31 13011.8   61.01
#Mann= 10 ,-1 , 0
  -292.4     .08       0  4872.9     .04       0  4955.8    .015       0
  5043.6     .04       0  5101.3     .08       0  6555.1     .12       0
  7703.2     .08       0 11024.7     .05       0 11250.8     .08       0
   12587     .99       0
#XS Ineff= 2 , 0
       0    4595    52.9    6940       0    52.9
Permanent Ineff=
       F       F
Bank Sta=4905.3,5098.9
XS Rating Curve= 0 ,0
Exp/Cntr=0.5,0.3

Type RM Length L Ch R = 1 ,27982.  ,554.5,553,291.5
BEGIN DESCRIPTION:
11th St. - D/S - XS 1
END DESCRIPTION:
XS GIS Cut Line= 6
       3109556.5     13853948.92      3106994.98     13852274.56
        3104894.     13852041.08      3104628.35     13852113.53
      3101981.26     13851888.87      3098718.46     13849680.42
#Sta/Elev= 30
  -325.9   58.07  1174.1    62.6  3214.3   60.45  3484.3    57.7  4025.4   60.25
  4605.4   56.13  4675.4   52.94  4795.4   52.79  4888.4   48.51  4958.4   27.71
 4978.59   19.55 5001.88   16.25 5021.02   19.17  5038.4   27.73  5088.4   45.51
  5118.4   50.49  5633.7   52.43  6163.7   50.64  6203.7    47.7  6523.7   48.82
  6903.7   52.39  7743.7   54.45  8100.3   58.21  9070.3    56.8  9230.3   59.05
  9270.3      57 10730.3   61.49 11250.3   61.05 11320.3   58.05 11720.3   63.01
#Mann= 7 ,-1 , 0
  -325.9     .08       0  4888.4     .04       0  4958.4    .015       0
  5038.4     .04       0  5118.4     .08       0  6523.7     .12       0
  7743.7     .08       0
#XS Ineff= 2 , 0
       0                    6895       0    52.9
Permanent Ineff=
       F       F
Bank Sta=4888.4,5118.4
XS Rating Curve= 0 ,0
Exp/Cntr=0.3,0.1

Type RM Length L Ch R = 1 ,27429.0 ,460,831,1812.7
BEGIN DESCRIPTION:
Cross Section E100-00-00-X19
Located At: DS W 11TH
END DESCRIPTION:
XS GIS Cut Line= 5
 3105461.555678213851700.3569445       3104670.8     13851558.17
      3104039.94     13851771.85      3102122.08     13851634.52
 3099907.647944913849808.8416523
#Sta/Elev= 30
  3939.6    65.2  4009.6    65.2  4049.6    61.5  4269.6    61.6  4399.6    55.7
  4872.9    51.8  4892.8   49.77  4937.5   32.07    4958   29.43  4980.9   18.43
  4999.7   16.12  5019.7   18.44    5044   30.17  5060.8   31.72  5122.1   51.72
  5123.9   51.71  5449.1    50.2  5509.1    46.9  5549.1    40.4  5629.1    37.6
  5729.1    46.5  5799.1      50  7309.1    52.7  7631.9      58  8001.9    55.7
  9181.9      57  9281.9    54.1  9441.9      58  9981.9    58.1 10201.9    60.5
#Mann= 6 ,-1 , 0
  3939.6     .08       0  4872.9     .04       0    4958    .015       0
    5044     .04       0  5123.9     .08       0  7631.9     .99       0
#XS Ineff= 2 , 0
       0                    6845       0   52.65
Permanent Ineff=
       F       F
#Block Obstruct= 2 ,-1
 5434.06 5825.33   49.44    7000    7001      50
Bank Sta=4872.9,5122.1
XS Rating Curve= 0 ,0
Exp/Cntr=0.3,0.1

Type RM Length L Ch R = 1 ,26598.  ,111.7,100,99.4
BEGIN DESCRIPTION:
T.C. Jester_1 - U/S - XS 4
END DESCRIPTION:
XS GIS Cut Line= 6
      3105436.13     13851665.63      3104809.99     13851535.24
       3104669.1     13850828.05      3104558.59     13850187.48
      3104023.08     13849636.24      3101853.76     13847834.44
#Sta/Elev= 30
  3845.5   65.46  3895.5   65.09  3945.5   61.54  4125.5   62.09  4295.5   55.24
  4615.1   53.65  4665.1   50.88  4865.1    50.8  4875.1   50.46  4895.1    46.9
 4934.51    30.6    4957   28.97 4980.71   17.74 4997.92   15.35 5019.32   17.72
 5043.56    28.8 5060.32   29.47  5105.1   45.34  5125.1   48.81  5386.2   46.92
  5856.2   52.29  5916.2   55.64  6046.2   54.02  6106.2    51.2  6396.2   53.16
  6566.2   51.11  6894.7   51.83  8524.7   50.99  9364.7   55.79  9444.7   59.63
#Mann= 6 ,-1 , 0
  3845.5     .08       0  4865.1     .04       0    4957    .015       0
 5043.56     .04       0  5125.1     .05       0  6894.7     .08       0
#XS Ineff= 2 , 0
       0                  5916.2       0   55.67
Permanent Ineff=
       F       F
Bank Sta=4875.1,5125.1
XS Rating Curve= 0 ,0
Exp/Cntr=0.5,0.3

Type RM Length L Ch R = 1 ,26498.0 ,147.5,132,131
BEGIN DESCRIPTION:
Upstream Section of Bridge/Culvert/Weir
END DESCRIPTION:
XS GIS Cut Line= 6
 3105417.894230713851619.0710451      3104906.21     13851509.77
      3104765.32     13850802.58       3104654.8     13850162.01
       3104119.3     13849610.77 3101934.285398413847795.9402754
#Sta/Elev= 30
  3967.5   65.31  4027.5   61.91  4207.5   62.01  4307.5   59.51  4367.5   54.81
  4856.7   51.69  4888.9   50.83  4935.4   29.97  4957.5   28.84  4980.8    17.6
    4993   17.24  4997.7   15.26  5019.2   17.61  5043.7   28.73  5060.6   29.23
    5088   39.44  5129.7   50.84  5542.2   47.41  5742.2   53.51  5762.2   53.71
  5812.2   50.21  5942.2   54.91  6082.2   51.51  6362.2   53.31  6905.7    52.7
  8060.8   50.71  8200.8   52.21  9000.8   52.41  9400.8   55.51  9470.8   61.51
#Mann= 6 ,-1 , 0
  3967.5     .08       0  4856.7     .04       0  4957.5    .015       0
  5043.7     .04       0  5129.7     .05       0  6905.7     .08       0
#XS Ineff= 3 ,-1
 5940.29 9454.13    55.5    5140    5940    51.8  3967.5    4878    51.8
Permanent Ineff=
       F       F       F
Bank Sta=4888.9,5129.7
XS Rating Curve= 0 ,0
Exp/Cntr=0.5,0.3

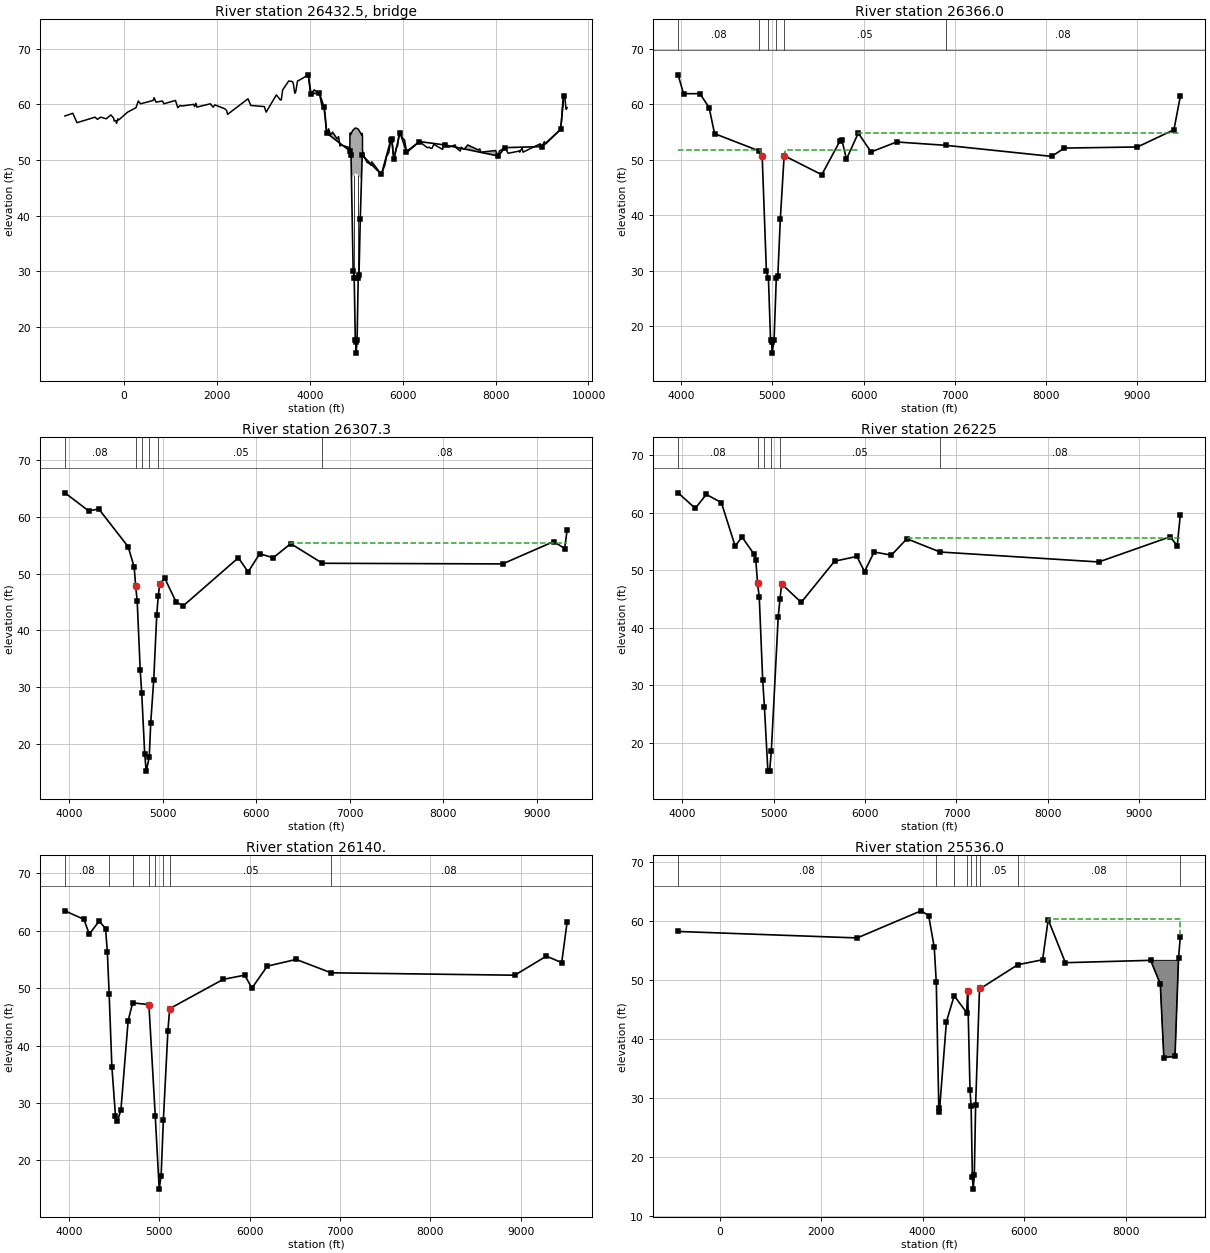
Type RM Length L Ch R = 3 ,26432.5 ,,,
BEGIN DESCRIPTION:
TC JESTER
Structure ID: E100-00-00-23
END DESCRIPTION:
Bridge Culvert--1,0,-1,-1, 0
Deck Dist Width WeirC Skew NumUp NumDn MinLoCord MaxHiCord MaxSubmerge Is_Ogee
10,111,2.6,0, 187, 187, , , 0.95, 0, ,,,
 -1269.9 -1099.9 -1009.9  -619.9  -569.9  -499.9  -379.9  -279.9  -219.9  -209.9
  -169.9  -159.9  -129.9  -109.9    80.1   260.1   310.1   360.1   630.1   650.1
   690.1   830.1   860.1  1110.1  1160.1  1210.1  1250.1  1500.1  1520.1  1550.1
  1570.1  1860.1  1920.1  1960.1  2171.9  2211.9  2231.9  2671.9  2731.9  3021.9
  3061.9  3281.9  3367.5  3387.5  3417.5  3547.5  3627.5  3647.5  3677.5  3697.5
  3737.5  3787.5  3967.5  3987.5  4007.5  4027.5  4097.5  4207.5  4257.5  4307.5
  4327.5  4337.5  4347.5  4367.5  4407.5  4447.5  4491.1  4591.1  4621.1  4651.1
  4662.1  4735.5  4812.9  4834.2  4856.7 4864.39  4864.5 4864.61  4879.3  4879.5
  4888.9  4889.7 4895.61  4895.7  4915.2  4932.4  4935.4    4953  4957.5  4967.5
  4973.5  4980.8  4986.1  4992.5    4993  4997.7    5000  5003.3    5007  5007.9
  5019.2  5026.2  5031.6  5043.7  5045.5  5046.7  5060.6    5088 5114.49  5114.6
  5120.6    5121  5129.7 5135.69  5135.8 5135.91  5172.1  5175.5  5225.6  5231.6
  5268.7  5281.9  5320.5  5336.2  5542.2  5622.2  5652.2  5702.2  5742.2  5762.2
  5782.2  5792.2  5812.2  5862.2  5862.3  5892.2  5922.2  5942.2  6002.2  6042.2
  6082.2  6112.2  6362.2  6532.2  6572.2  6602.2  6630.8  6670.8  6860.8  6880.8
  6905.7  6990.8  7130.8  7150.8  7240.8  7260.8  7320.8  7400.8  7630.8  7660.8
  7680.8  8000.8  8040.8  8050.8  8060.8  8080.8  8200.8  8270.8  8510.8  8520.8
  8530.8  8560.8  8570.8  8590.8  8960.8  9000.8  9010.8  9050.8  9080.8  9400.8
  9420.8  9450.8  9470.8  9490.8  9510.8  9520.8  9540.8
    57.9    58.4    56.7    57.7    57.3    57.7    57.4    58.1    57.5      57
    57.1    56.6    57.4    57.2    58.6    59.4    60.6    60.1    60.7    61.2
    60.4    60.6    60.1    60.7    59.4    59.8    59.7      60    59.6    60.2
    59.5    60.1    59.5    59.9    59.2    58.9    58.2      61    59.8    59.6
    58.6    61.7    60.8    60.8    62.6    64.2    64.1    63.7      62    62.2
    64.2    64.4    65.3    64.1    62.5    61.9    62.6      62    59.9    59.5
    58.5    57.7    56.3    54.8    55.6    54.5      55    53.8    54.2    52.5
   52.71   52.54   52.34   52.29   51.81   51.95   54.65   54.65   54.91   54.57
   54.72   54.73   54.82   54.82   55.12   55.39   55.41   55.53   55.56   55.63
   55.67   55.72   55.76   55.74   55.74   55.72   55.71    55.7   55.69   55.68
   55.64   55.62    55.6   55.56   55.55   55.53   55.33   54.93   54.54   54.54
   54.45    54.8   54.55   54.38   54.38   51.68   50.65   50.55   49.68   49.58
   49.41   49.35   49.05   49.67    47.4    49.2    50.6    51.3    53.5    53.7
    52.7    51.3    50.2    52.1    52.1    52.6    54.7    54.9    53.9    53.6
    51.5    51.5    53.3    52.2    52.3    52.1    52.1    52.8    51.9    52.8
   52.69    52.3    52.7    52.2    51.6    52.3    51.9    52.7    51.8      52
    51.4    51.7    50.9    51.1    50.7    51.6    52.2    51.2    51.6    51.4
    51.7    51.9    52.2    51.4    52.9    52.4    52.6    53.3    52.9    55.5
    57.2    60.9    61.5    61.4    59.6    59.1    59.4
                                                                                
                                                                                
                                                                                
                                                                                
                                                                                
                                                                                
                                                                                
                                                                                
                           46.89   46.92   47.19   47.21   47.33   47.36   47.43
   47.47   47.52   47.56   47.54   47.54   47.52   47.51    47.5   47.49   47.48
   47.44   47.42    47.4   47.36   47.35   47.33   47.13   46.73   46.67
                                                                                
                                                                                
                                                                                
                                                                                
                                                                                
                                                                                
                                                                                
                                                        
 -1269.9 -1099.9 -1009.9  -619.9  -569.9  -499.9  -379.9  -279.9  -219.9  -209.9
  -169.9  -159.9  -129.9  -109.9    80.1   260.1   310.1   360.1   630.1   650.1
   690.1   830.1   860.1  1110.1  1160.1  1210.1  1250.1  1500.1  1520.1  1550.1
  1570.1  1860.1  1920.1  1960.1  2171.9  2211.9  2231.9  2671.9  2731.9  3021.9
  3061.9  3281.9  3367.5  3387.5  3417.5  3547.5  3627.5  3647.5  3677.5  3697.5
  3737.5  3787.5  3967.5  3987.5  4007.5  4027.5  4097.5  4207.5  4257.5  4307.5
  4327.5  4337.5  4347.5  4367.5  4407.5  4447.5  4491.1  4591.1  4621.1  4651.1
  4662.1  4735.5  4812.9  4834.2  4856.7 4864.39  4864.5 4864.61  4879.3  4879.5
  4888.9  4889.7 4895.61  4895.7  4915.2  4932.4  4935.4    4953  4957.5  4967.5
  4973.5  4980.8  4986.1  4992.5    4993  4997.7    5000  5003.3    5007  5007.9
  5019.2  5026.2  5031.6  5043.7  5045.5  5046.7  5060.6    5088 5114.49  5114.6
  5120.6    5121  5129.7 5135.69  5135.8 5135.91  5172.1  5175.5  5225.6  5231.6
  5268.7  5281.9  5320.5  5336.2  5542.2  5622.2  5652.2  5702.2  5742.2  5762.2
  5782.2  5792.2  5812.2  5862.2  5862.3  5892.2  5922.2  5942.2  6002.2  6042.2
  6082.2  6112.2  6362.2  6532.2  6572.2  6602.2  6630.8  6670.8  6860.8  6880.8
  6905.7  6990.8  7130.8  7150.8  7240.8  7260.8  7320.8  7400.8  7630.8  7660.8
  7680.8  8000.8  8040.8  8050.8  8060.8  8080.8  8200.8  8270.8  8510.8  8520.8
  8530.8  8560.8  8570.8  8590.8  8960.8  9000.8  9010.8  9050.8  9080.8  9400.8
  9420.8  9450.8  9470.8  9490.8  9510.8  9520.8  9540.8
    57.9    58.4    56.7    57.7    57.3    57.7    57.4    58.1    57.5      57
    57.1    56.6    57.4    57.2    58.6    59.4    60.6    60.1    60.7    61.2
    60.4    60.6    60.1    60.7    59.4    59.8    59.7      60    59.6    60.2
    59.5    60.1    59.5    59.9    59.2    58.9    58.2      61    59.8    59.6
    58.6    61.7    60.8    60.8    62.6    64.2    64.1    63.7      62    62.2
    64.2    64.4    65.3    64.1    62.5    61.9    62.6      62    59.9    59.5
    58.5    57.7    56.3    54.8    55.6    54.5      55    53.8    54.2    52.5
   52.71   52.54   52.34   52.29   51.81   51.95   54.65   54.65   54.91   54.57
   54.72   54.73   54.82   54.82   55.12   55.39   55.41   55.53   55.56   55.63
   55.67   55.72   55.76   55.74   55.74   55.72   55.71    55.7   55.69   55.68
   55.64   55.62    55.6   55.56   55.55   55.53   55.33   54.93   54.54   54.54
   54.45    54.8   54.55   54.38   54.38   51.68   50.65   50.55   49.68   49.58
   49.41   49.35   49.05   49.67    47.4    49.2    50.6    51.3    53.5    53.7
    52.7    51.3    50.2    52.1    52.1    52.6    54.7    54.9    53.9    53.6
    51.5    51.5    53.3    52.2    52.3    52.1    52.1    52.8    51.9    52.8
   52.69    52.3    52.7    52.2    51.6    52.3    51.9    52.7    51.8      52
    51.4    51.7    50.9    51.1    50.7    51.6    52.2    51.2    51.6    51.4
    51.7    51.9    52.2    51.4    52.9    52.4    52.6    53.3    52.9    55.5
    57.2    60.9    61.5    61.4    59.6    59.1    59.4
                                                                                
                                                                                
                                                                                
                                                                                
                                                                                
                                                                                
                                                                                
                                                                                
                           46.89   46.92   47.19   47.21   47.33   47.36   47.43
   47.47   47.52   47.56   47.54   47.54   47.52   47.51    47.5   47.49   47.48
   47.44   47.42    47.4   47.36   47.35   47.33   47.13   46.73   46.67
                                                                                
                                                                                
                                                                                
                                                                                
                                                                                
                                                                                
                                                                                
                                                        
Pier Skew, UpSta & Num, DnSta & Num=  ,4953, 2 ,4953, 2 , 0 , 0 , 0 ,,
     2.5     2.5
   27.95   48.34
     2.5     2.5
   27.87   48.26
Pier Skew, UpSta & Num, DnSta & Num=  ,5046.7, 2 ,5046.7, 2 , 0 , 0 , 0 ,,
     2.5     2.5
   27.74   48.35
     2.5     2.5
   27.66   48.27
BR Coef= 1 , 1 , 0 ,1.25, 0 ,,,0.8,-1,1.2,0,
WSPro=,,,, 1 ,,,, 0 ,,,, 0 ,,,,-1 ,-1 ,-1 , 0 , 0 , 0 , 0 , 0
BR D #Sta/Elev= 131
  3967.5   65.21  3987.5   64.01  4007.5   62.41  4027.5   61.81  4097.5   62.51
  4207.5   61.91  4257.5   59.81  4307.5   59.41  4327.5   58.41  4337.5   57.61
  4347.5   56.21  4367.5   54.71  4407.5   55.51  4447.5   54.41  4491.1   54.91
  4591.1   53.71  4621.1   54.11  4651.1   52.41  4662.1   52.62  4735.5   52.44
  4812.9   52.24  4834.2   52.19  4856.7   51.59 4864.39   51.38  4864.5   51.38
 4864.61   51.38  4879.3   50.99  4879.5   50.98  4888.9   50.73  4889.7   49.44
 4895.61   46.84 4895.71    46.8  4915.2   38.24  4932.4   31.11  4935.4   29.87
    4953    28.9  4957.5   28.74  4967.5   23.84  4973.5    20.6  4980.8    17.5
  4986.1   17.36  4992.5   17.18    4993   17.14  4997.7   15.16    5000   15.23
  5003.3   15.34    5007   17.16  5007.9   17.41  5019.2   17.51  5026.2    20.4
  5031.6   23.11  5043.7   28.63  5045.5   28.65  5046.7   28.66  5060.6   29.13
    5088   39.34 5114.49   46.58  5114.6   46.61  5120.6   48.25    5121   48.36
  5129.7   50.74 5135.69   50.65  5135.8   50.65 5135.91   50.65  5172.1   50.11
  5175.5   50.04  5225.6   49.05  5231.6   48.98  5268.7   48.58  5281.9   48.68
  5320.5   48.96  5336.2   49.58  5542.2   47.31  5622.2   49.11  5652.2   50.51
  5702.2   51.21  5742.2   53.41  5762.2   53.61  5782.2   52.61  5792.2   51.21
  5812.2   50.11  5862.2   52.01  5862.3   52.01  5892.2   52.51  5922.2   54.61
  5942.2   54.81  6002.2   53.81  6042.2   53.51  6082.2   51.41  6112.2   51.41
  6362.2   53.21  6532.2   52.11  6572.2   52.21  6602.2   52.01  6630.8   52.01
  6670.8   52.71  6860.8   51.81  6880.8   52.71  6905.7    52.6  6990.8   52.21
  7130.8   52.61  7150.8   52.11  7240.8   51.51  7260.8   52.21  7320.8   51.81
  7400.8   52.61  7630.8   51.71  7660.8   51.91  7680.8   51.31  8000.8   51.61
  8040.8   50.81  8050.8   51.01  8060.8   50.61  8080.8   51.51  8200.8   52.11
  8270.8   51.11  8510.8   51.51  8520.8   51.31  8530.8   51.61  8560.8   51.81
  8570.8   52.11  8590.8   51.31  8960.8   52.81  9000.8   52.31  9010.8   52.51
  9050.8   53.21  9080.8   52.81  9400.8   55.41  9420.8   57.11  9450.8   60.81
  9470.8   61.41
BR D #Mann= 6
  3967.5     .08  4856.7     .04  4957.5    .015  5043.7     .04  5129.7     .05
  6905.7     .08
BC Design=,, 0 ,, 0 ,,,,,,
BC HTab HWMax=65.31
BC Use User HTab Curves=0
BC User HTab FreeFlow(D)= 0

Type RM Length L Ch R = 1 ,26366.0 ,72.2,58.7,26.4
BEGIN DESCRIPTION:
Downstream Section of Bridge/Culvert/Weir
END DESCRIPTION:
XS GIS Cut Line= 6
 3105564.222731613851583.3805535      3105033.26     13851469.96
       3104896.3     13850782.51      3104784.27     13850133.17
      3104241.19     13849574.12 3102071.0134391 13847771.622508
#Sta/Elev= 30
  3967.5   65.31  4027.5   61.91  4207.5   61.91  4307.5   59.41  4367.5   54.71
  4856.7   51.59  4888.9   50.73  4935.4   29.87  4957.5   28.74  4980.8    17.5
    4993   17.14  4997.7   15.16  5019.2   17.51  5043.7   28.63  5060.6   29.13
    5088   39.34  5129.7   50.74  5542.2   47.31  5742.2   53.41  5762.2   53.61
  5812.2   50.11  5942.2   54.81  6082.2   51.41  6362.2   53.21  6905.7    52.6
  8060.8   50.61  8200.8   52.11  9000.8   52.31  9400.8   55.41  9470.8   61.41
#Mann= 6 ,-1 , 0
  3967.5     .08       0  4856.7     .04       0  4957.5    .015       0
  5043.7     .04       0  5129.7     .05       0  6905.7     .08       0
#XS Ineff= 3 ,-1
 5938.63  9470.8   54.81    5140    5938    51.8  3967.5    4878    51.8
Permanent Ineff=
       F       F       F
Bank Sta=4888.9,5129.7
XS Rating Curve= 0 ,0
Exp/Cntr=0.5,0.3

Type RM Length L Ch R = 1 ,26307.3 ,104.9,82.3,38.4
BEGIN DESCRIPTION:
Added XS.
END DESCRIPTION:
XS GIS Cut Line= 6
      3105546.48     13851536.87      3105163.45      13851411.8
      3104923.73     13850791.66      3104809.01     13850118.37
      3104298.51     13849582.66       3102088.5     13847739.67
#Sta/Elev= 30
  3953.6   64.26 4206.07   61.09 4316.53   61.39 4629.92   54.74 4694.25   51.14
 4710.33   47.75 4726.41   45.12 4758.58   32.99 4774.66   28.94 4806.82    18.1
  4822.9   15.13 4855.07   17.58 4871.15    23.7 4903.31    31.3 4935.48   42.76
 4951.56   46.08 4967.64   48.22  5021.4   49.17 5143.13   44.95 5219.21   44.32
 5807.99    52.8 5911.59   50.29 6035.91    53.5 6180.95    52.8 6367.43   55.29
 6706.16  51.823 8631.89   51.71 9178.77   55.66 9295.96   54.43 9322.01   57.74
#Mann= 6 ,-1 , 0
  3953.6     .08       0 4710.33     .04       0 4774.66    .015       0
 4855.07     .04       0 4951.56     .05       0 6706.16     .08       0
#XS Ineff= 2 , 0
                         6359.21           55.36
Permanent Ineff=
       F       F
Bank Sta=4710.33,4967.64
XS Rating Curve= 0 ,0
Exp/Cntr=0.3,0.1

Type RM Length L Ch R = 1 ,26225   ,97.1,85,38
BEGIN DESCRIPTION:
Added XS.
END DESCRIPTION:
XS GIS Cut Line= 6
      3105793.59     13851570.61      3105378.81     13851342.06
       3104959.8     13850791.84      3104847.64     13850093.48
      3104316.46     13849549.61      3102115.59     13847719.08
#Sta/Elev= 30
  3953.6   63.43 4141.99   60.73 4261.88   63.15 4427.18   61.74 4578.02   54.18
 4653.43   55.74 4785.41   52.75 4804.27   51.79 4823.12   47.68 4841.98   45.29
 4879.68   30.84 4898.54   26.16 4936.25   15.04  4955.1   15.04 4973.96   18.52
 5049.37   41.88 5068.23   44.92 5087.08   47.58 5301.09   44.38  5665.7   51.54
 5909.95   52.37 5993.82   49.74 6098.65   53.15 6287.36   52.59 6457.44   55.44
 6820.43   53.14 8556.84   51.41 9337.25   55.78 9415.29   54.26 9448.94   59.56
#Mann= 6 ,-1 , 0
  3953.6     .08       0 4823.12     .04       0 4898.54    .015       0
 4973.96     .04       0 5068.23     .05       0 6820.43     .08       0
#XS Ineff= 2 , 0
                         6463.98           55.52
Permanent Ineff=
       F       F
Bank Sta=4823.12,5087.08
XS Rating Curve= 0 ,0
Exp/Cntr=0.3,0.1

Type RM Length L Ch R = 1 ,26140.  ,612.4,604,375.7
BEGIN DESCRIPTION:
T.C. Jester_1 - D/S - XS 1
END DESCRIPTION:
XS GIS Cut Line= 5
      3105880.54       13851596.      3104992.52      13850742.8
      3104880.49      13850093.5      3104337.41      13849534.5
      3102114.23      13847687.9
#Sta/Elev= 30
  3953.6   63.47  4163.6   61.99  4223.6    59.4  4333.6    61.7  4403.6   60.36
  4423.6   56.28  4443.6   48.91  4473.6   36.28  4513.6   27.71  4533.6   26.77
  4573.6   28.75  4653.6   44.31  4703.6   47.43  4883.6   47.13  4953.6   27.79
 4997.56   14.97 5018.74   17.34  5043.6   27.01  5093.6   42.52  5113.6   46.42
    5705   51.52    5944   52.26    6024      50    6194   53.83    6514      55
    6900   52.67  8933.4   52.25  9283.4   55.57  9453.4   54.45  9513.4   61.55
#Mann= 8 ,-1 , 0
  3953.6     .08       0  4443.6     .99       0  4703.6     .08       0
  4883.6     .04       0  4953.6    .015       0  5043.6     .04       0
  5113.6     .05       0    6900     .08       0
#XS Ineff= 2 , 0
       0                    6514       0      55
Permanent Ineff=
       F       F
Bank Sta=4883.6,5113.6
XS Rating Curve= 0 ,0
Exp/Cntr=0.3,0.1

Type RM Length L Ch R = 1 ,25536.0 ,420.1,404,403
BEGIN DESCRIPTION:
Cross Section E100-00-00-X18
Located At: DS TC JESTER
END DESCRIPTION:
XS GIS Cut Line= 6
      3110301.32     13853713.23      3107889.86     13852031.66
      3105883.65     13850754.21      3105064.65     13849986.86
      3104563.02     13849241.24      3102807.02     13847385.85
#Sta/Elev= 30
  -818.4    58.2  2711.5    57.1  3969.7    61.7  4119.7    60.9  4229.7    55.5
  4269.7    49.6  4319.7    28.2  4329.7    27.5  4469.7    42.9  4622.9    47.3
    4867   44.44  4888.4   48.03  4934.7   31.27  4956.5    28.5  4981.1   16.59
  4997.2   14.48  5019.6   16.95  5044.9   28.67  5121.8   48.59  5130.4   48.47
  5877.7   52.56  6365.2    53.4  6475.2    60.2  6813.9    52.9  8493.9    53.3
  8683.9    49.3  8753.9    36.8  8973.9      37  9043.9    53.7  9078.5    57.3
#Mann= 9 ,-1 , 0
  -818.4     .08       0  4269.7     .99       0  4622.9     .08       0
    4867     .04       0  4956.5    .015       0  5044.9     .04       0
  5130.4     .05       0  5877.7     .08       0  9078.5     .99       0
#XS Ineff= 2 , 0
       0                    6469       0   60.25
Permanent Ineff=
       F       F
#Block Obstruct= 2 ,-1
    7000    7001      50 8459.39 9193.01    53.3
Bank Sta=4888.4,5121.8
XS Rating Curve= 0 ,0
Exp/Cntr=0.3,0.1

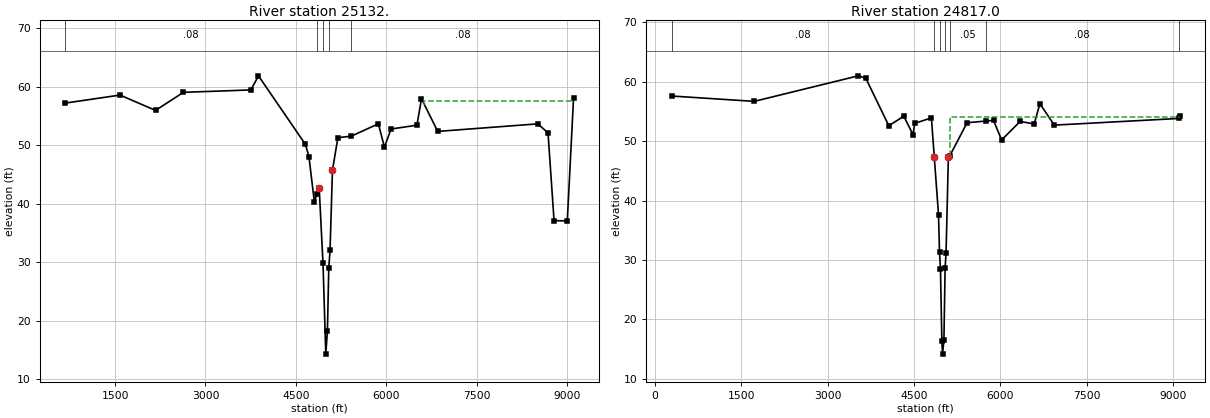
Type RM Length L Ch R = 1 ,25132.  ,381.8,315,238.2
BEGIN DESCRIPTION:
Union Pacific RR7 - U/S - XS 4
END DESCRIPTION:
XS GIS Cut Line= 6
      3109197.49     13852596.13      3106415.88      13851000.1
      3106177.15     13850452.03      3105594.41     13849941.38
      3105033.13     13849858.83       3102872.2     13847387.18
#Sta/Elev= 30
   672.4    57.2  1582.4   58.57  2171.2   55.95  2634.4   59.04  3754.4   59.45
  3879.5   61.86  4657.3   50.16  4717.3   48.03  4807.3   40.26  4847.3   41.65
  4887.3   42.65 4950.25   29.81 4996.75   14.29 5023.87   18.31 5046.39   29.04
  5067.3   32.03  5107.3   45.71  5197.3   51.29    5418   51.54  5869.4   53.66
  5969.4   49.67  6079.4   52.77  6509.4   53.42  6584.5   57.94  6854.5   52.36
  8514.5   53.65  8684.5   52.11  8784.5   37.11  9004.5   37.05  9107.9   58.04
#Mann= 5 ,-1 , 0
   672.4     .08       0  4847.3     .04       0 4950.25    .015       0
 5046.39     .04       0    5418     .08       0
#XS Ineff= 2 , 0
       0                    6634       0    57.5
Permanent Ineff=
       F       F
#Block Obstruct= 2 , 0
       0                    8660       0      52
Bank Sta=4887.3,5107.3
XS Rating Curve= 0 ,0
Exp/Cntr=0.5,0.3

Type RM Length L Ch R = 1 ,24817.0 ,57.5,59,73.7
BEGIN DESCRIPTION:
Upstream Section of Bridge/Culvert/Weir
END DESCRIPTION:
XS GIS Cut Line= 6
      3109237.11     13852497.08       3106455.5     13850901.05
      3106345.58     13849839.91      3105065.57     13849802.77
      3104642.76     13849238.51      3102919.89     13847383.11
#Sta/Elev= 30
   294.5    57.6  1727.1    56.7  3534.2      61  3664.2    60.6  4064.2    52.6
  4324.2    54.2  4484.2    51.1  4514.2      53    4804   53.92    4853   47.37
  4926.9   37.64  4944.4   31.31  4961.1   28.39  4985.4   16.28  4996.4   14.14
  5021.1   16.55  5041.6   28.72  5057.7    31.1  5098.2   47.36  5119.7   47.47
  5422.6    53.1  5744.5   53.38  5882.4    53.5  6022.4    50.2    6344   53.32
  6587.5    52.9  6687.5    56.3  6937.5    52.7    9094   53.82  9119.4    54.2
#Mann= 7 ,-1 , 0
   294.5     .08       0    4853     .04       0  4961.1    .015       0
  5041.6     .04       0  5119.7     .05       0  5744.5     .08       0
    9094     .99       0
#XS Ineff= 2 , 0
       0 4801.01    53.9    5124       0      54
Permanent Ineff=
       F       F
Bank Sta=4853,5098.2
XS Rating Curve= 0 ,0
Exp/Cntr=0.5,0.3