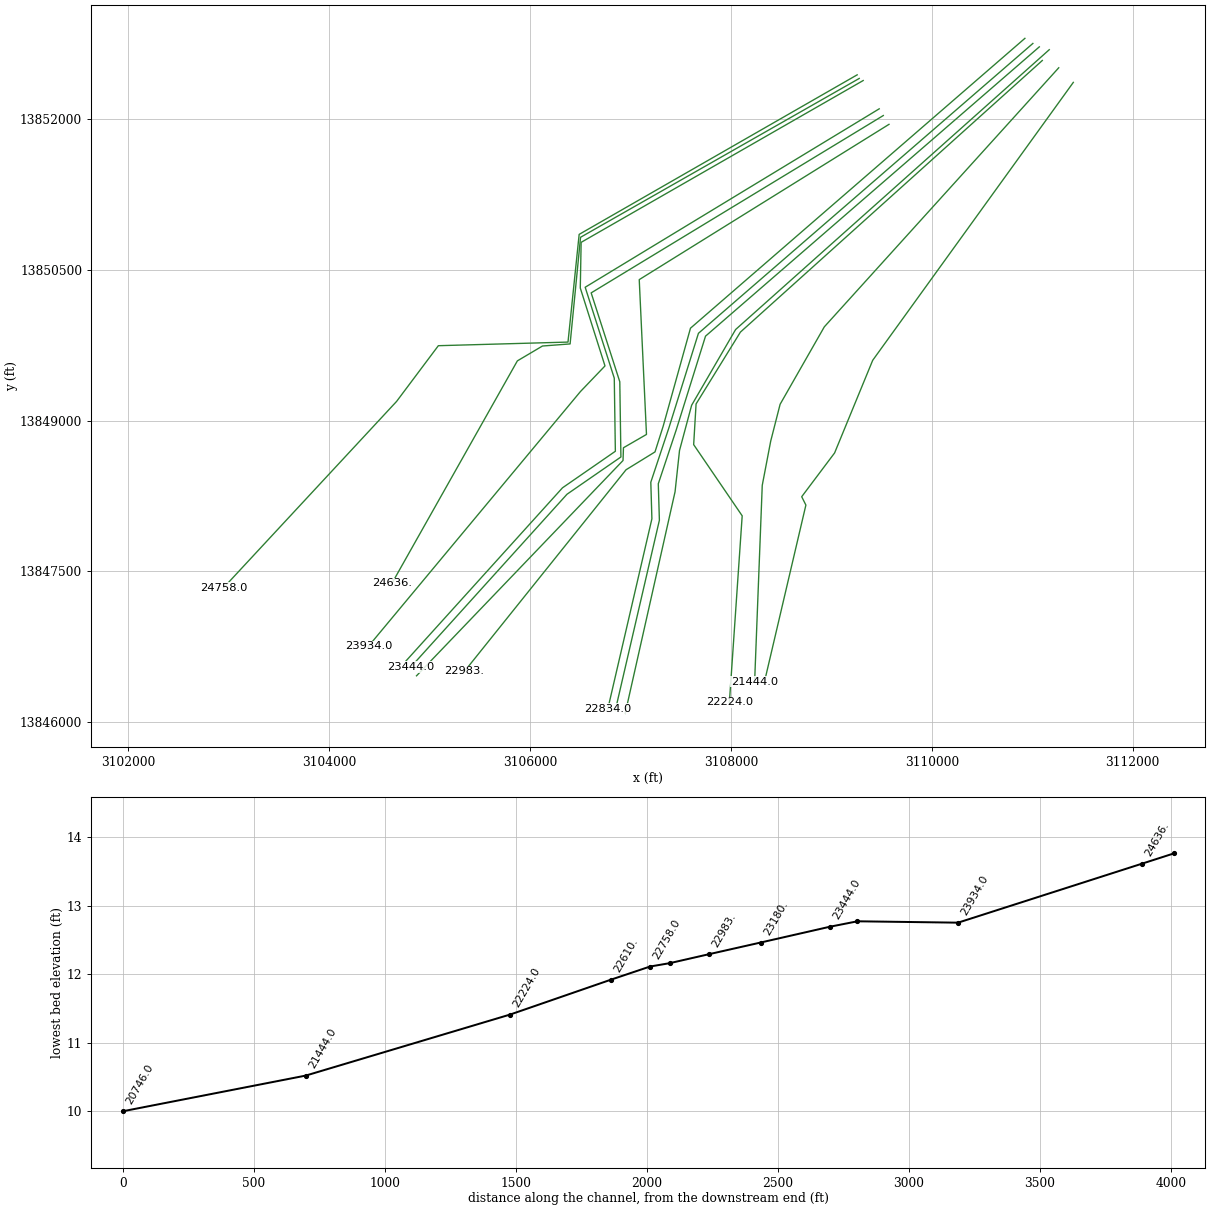
HEC-RAS study E100-00-00.prj: E100-00-00

--- E100-00-00.g02 (geometry) --- (continued)

Type RM Length L Ch R = 3 ,24789.0 ,,,
BEGIN DESCRIPTION:
UNION PACIFIC RR
Structure ID: E100-00-00-22
END DESCRIPTION:
Bridge Culvert--1,0,-1,-1, 0
Deck Dist Width WeirC Skew NumUp NumDn MinLoCord MaxHiCord MaxSubmerge Is_Ogee
10,36,2.6,0, 60, 60, , , 0.95, 0, ,,,
   294.5   477.1   564.5   967.1  1077.1  1227.1  1264.5  1597.1  1634.5  2129.1
  2229.1  2434.7  2464.7  2599.1  2619.1  2769.1  3079.1  3489.1  3534.2  3664.2
  4064.2  4094.9  4324.2  4484.2  4494.2  4504.2  4562.5    4853 4864.99    4865
    4878  4878.1  5021.1    5111  5111.1  5123.6 5123.71  5882.4  5942.4  5972.4
    6344  6587.5  6657.5  6687.5  6787.5  6817.5  6915.2  7035.2  7935.2  8305.2
  8447.5  8647.5  8677.5  9025.2  9045.2  9065.2  9085.2    9094  9117.5  9119.4
    57.6   57.61    58.6   57.81   58.61   57.51    58.1   57.91      57   57.87
   58.81    58.1    59.2   58.91   59.41   57.81   59.21   59.88   61.01   60.61
   53.48    54.2   54.21   51.56   51.74   52.91    54.3   53.81    54.1    56.7
    56.7    56.7   57.18   57.02   57.02      57    54.3   53.51   52.31   50.81
    53.4   53.47   56.21   56.31   55.61   53.71    52.9    53.8    53.1    53.7
   52.51   53.31   52.41    53.6    54.3    57.9    58.6    57.9    53.9    54.2
                                                                                
                                                                                
                                                                                
            50.5   50.98   50.82
                                                                                
                                                                                
   294.5   477.1   564.5   967.1  1077.1  1227.1  1264.5  1597.1  1634.5  2129.1
  2229.1  2434.7  2464.7  2599.1  2619.1  2769.1  3079.1  3489.1  3534.2  3664.2
  4064.2  4094.9  4324.2  4484.2  4494.2  4504.2  4562.5    4853 4864.99    4865
    4878  4878.1  5021.1    5111  5111.1  5123.6 5123.71  5882.4  5942.4  5972.4
    6344  6587.5  6657.5  6687.5  6787.5  6817.5  6915.2  7035.2  7935.2  8305.2
  8447.5  8647.5  8677.5  9025.2  9045.2  9065.2  9085.2    9094  9117.5  9119.4
    57.6   57.61    58.6   57.81   58.61   57.51    58.1   57.91      57   57.87
   58.81    58.1    59.2   58.91   59.41   57.81   59.21   59.88   61.01   60.61
   53.48    54.2   54.21   51.56   51.74   52.91    54.3   53.81    54.1    56.7
    56.7    56.7   57.18   57.02   57.02      57    54.3   53.51   52.31   50.81
    53.4   53.47   56.21   56.31   55.61   53.71    52.9    53.8    53.1    53.7
   52.51   53.31   52.41    53.6    54.3    57.9    58.6    57.9    53.9    54.2
                                                                                
                                                                                
                                                                                
            50.5   50.98   50.82
                                                                                
                                                                                
Pier Skew, UpSta & Num, DnSta & Num=  ,4884.7, 2 ,4884.7, 2 , 0 , 0 , 0 ,,
       1       1
   42.13   51.68
       1       1
   41.76   51.31
Pier Skew, UpSta & Num, DnSta & Num=  ,4904.7, 2 ,4904.7, 2 , 0 , 0 , 0 ,,
       1       1
    39.5    51.9
       1       1
   39.13   51.53
Pier Skew, UpSta & Num, DnSta & Num=  ,4924.7, 2 ,4924.7, 2 , 0 , 0 , 0 ,,
       1       1
   36.86    51.9
       1       1
   36.49   51.53
Pier Skew, UpSta & Num, DnSta & Num=  ,4944, 2 ,4944, 2 , 0 , 0 , 0 ,,
       1       1
    30.3   51.91
       1       1
   29.93   51.54
Pier Skew, UpSta & Num, DnSta & Num=  ,4964.5, 2 ,4964.5, 2 , 0 , 0 , 0 ,,
       1       1
   24.49   51.91
       1       1
   24.12   51.54
Pier Skew, UpSta & Num, DnSta & Num=  ,4984.1, 2 ,4984.1, 2 , 0 , 0 , 0 ,,
       1       1
   15.68   51.93
       1       1
   15.31   51.56
Pier Skew, UpSta & Num, DnSta & Num=  ,5003.9, 2 ,5003.9, 2 , 0 , 0 , 0 ,,
       1       1
   14.01   51.96
       1       1
   13.64   51.59
Pier Skew, UpSta & Num, DnSta & Num=  ,5023.9, 2 ,5023.9, 2 , 0 , 0 , 0 ,,
       1       1
   16.83   51.98
       1       1
   16.46   51.61
Pier Skew, UpSta & Num, DnSta & Num=  ,5043.6, 2 ,5043.6, 2 , 0 , 0 , 0 ,,
       1       1
   27.94   51.96
       1       1
   27.57   51.59
Pier Skew, UpSta & Num, DnSta & Num=  ,5064.2, 2 ,5064.2, 2 , 0 , 0 , 0 ,,
       1       1
   32.17   51.93
       1       1
    31.8   51.56
Pier Skew, UpSta & Num, DnSta & Num=  ,5084, 2 ,5084, 2 , 0 , 0 , 0 ,,
       1       1
   40.84   51.89
       1       1
   40.47   51.52
Pier Skew, UpSta & Num, DnSta & Num=  ,5103.2, 2 ,5103.2, 2 , 0 , 0 , 0 ,,
       1       1
   46.38   51.85
       1       1
   46.01   51.48
BR Coef= 1 , 1 , 0 ,1.25, 0 ,,,0.8,-1,1.2,0,
WSPro=,,,, 1 ,,,, 0 ,,,, 0 ,,,,-1 ,-1 ,-1 , 0 , 0 , 0 , 0 , 0
BC Design=,, 0 ,, 0 ,,,,,,
BC HTab HWMax=61
BC Use User HTab Curves=0
BC User HTab FreeFlow(D)= 0

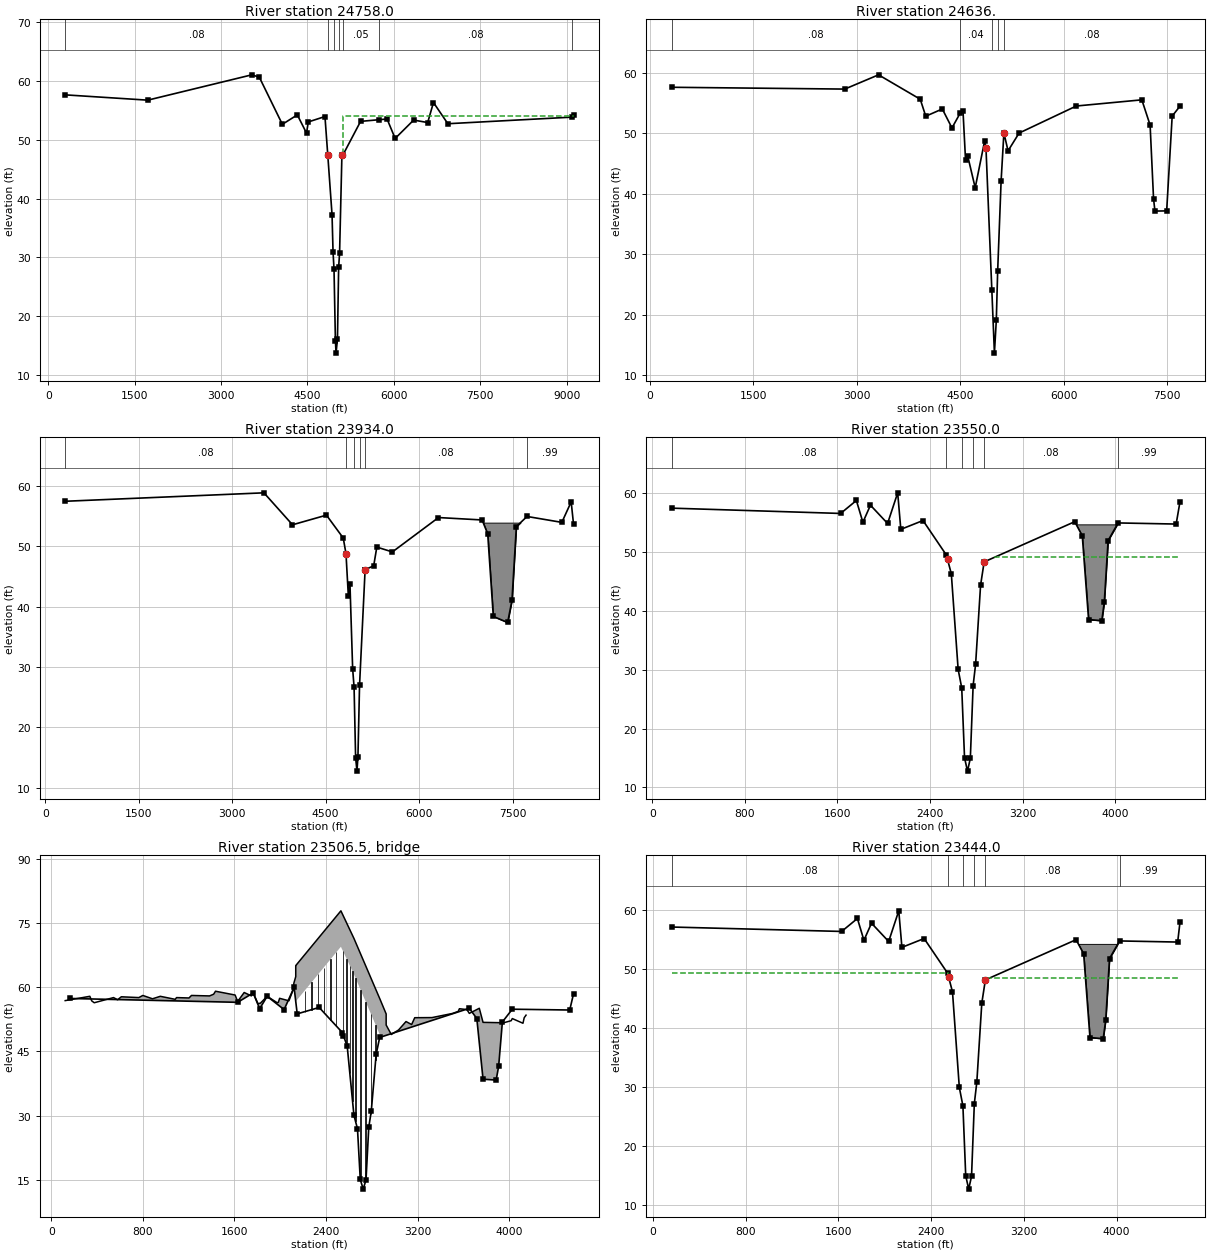
Type RM Length L Ch R = 1 ,24758.0 ,86.9,122,179.7
BEGIN DESCRIPTION:
Downstream Section of Bridge/Culvert/Weir
END DESCRIPTION:
XS GIS Cut Line= 6
      3109256.73     13852444.04       3106488.2     13850855.35
      3106377.08     13849782.66      3105085.81     13849746.63
      3104670.28     13849192.09      3102946.33     13847335.54
#Sta/Elev= 30
   294.5    57.6  1727.1    56.7  3534.2      61  3664.2    60.6  4064.2    52.6
  4324.2    54.2  4484.2    51.1  4514.2      53    4804   53.92    4853   47.37
  4926.9   37.26  4944.4   30.93  4961.1   28.01  4985.4    15.9  4996.4   13.76
  5021.1   16.17  5041.6   28.34  5057.7   30.72  5098.2   47.36  5119.7   47.47
  5422.6    53.1  5744.5   53.38  5882.4    53.5  6022.4    50.2    6344   53.32
  6587.5    52.9  6687.5    56.3  6937.5    52.7    9094   53.82  9119.4    54.2
#Mann= 7 ,-1 , 0
   294.5     .08       0    4853     .04       0  4961.1    .015       0
  5041.6     .04       0  5119.7     .05       0  5744.5     .08       0
    9094     .99       0
#XS Ineff= 2 , 0
       0 4801.01    53.9    5124       0      54
Permanent Ineff=
       F       F
Bank Sta=4853,5098.2
XS Rating Curve= 0 ,0
Exp/Cntr=0.5,0.3

Type RM Length L Ch R = 1 ,24636.  ,675.7,702,703
BEGIN DESCRIPTION:
Union Pacific RR7 - D/S - XS 1
END DESCRIPTION:
XS GIS Cut Line= 6
      3109277.31     13852408.16        3106502.     13850826.31
      3106397.96     13849764.33      3106122.89      13849743.5
      3105872.84     13849595.55      3104623.54     13847380.12
#Sta/Elev= 30
   317.2   57.61  2827.2   57.31  3317.2   59.67  3921.7   55.63  4001.7   52.82
  4241.7   54.02  4381.7   50.88    4500   53.31  4541.7    53.7  4578.7   45.53
  4608.7    46.3  4718.7   40.98  4854.6   48.68  4874.6   47.63    4960   24.02
 4997.27   13.61  5024.6   19.02  5044.6   27.24  5094.6   42.16  5134.6   50.05
  5195.1   47.09  5355.1   50.03  6185.1   54.51  7135.1   55.53  7255.1   51.35
  7305.1   39.13  7325.1   37.12  7495.1   37.15  7575.1   52.84  7688.5   54.49
#Mann= 5 ,-1 , 0
   317.2     .08       0    4500     .04       0    4960    .015       0
  5044.6     .04       0  5134.6     .08       0
#Block Obstruct= 2 , 0
       0                    7234       0   52.94
Bank Sta=4874.6,5134.6
XS Rating Curve= 0 ,0
Exp/Cntr=0.3,0.1

Type RM Length L Ch R = 1 ,23934.0 ,218.3,384,657
BEGIN DESCRIPTION:
Cross Section E100-00-00-X17
Located At: US DURHAM
END DESCRIPTION:
XS GIS Cut Line= 6
      3109316.94     13852387.48      3106507.82     13850775.86
      3106499.39     13850321.02      3106745.38     13849545.18
      3106500.05     13849288.99       3104390.6      13846754.1
#Sta/Elev= 30
   318.8    57.5  3508.8    58.9  3967.4    53.6  4512.3    55.2  4782.3    51.4
  4826.1    48.8  4864.3   41.72  4889.7   43.81  4932.9   29.75  4955.9   26.66
  4980.5   14.99  5002.3   12.75    5018   15.17  5043.6   26.98    5133   46.16
  5133.5   46.16  5270.9    46.8  5320.9    49.9  5570.9    49.1  6310.9    54.8
  7010.9    54.4  7100.9    52.1  7190.9    38.4  7420.9    37.4  7490.9    41.1
  7560.9    53.3  7732.3   54.98  8290.9      54  8440.9    57.4  8478.7    53.7
#Mann= 6 ,-1 , 0
   318.8     .08       0  4826.1     .04       0  4955.9    .015       0
  5043.6     .04       0  5133.5     .08       0  7732.3     .99       0
#Block Obstruct= 1 ,-1
  6986.9 7807.86   53.96
Bank Sta=4826.1,5133
XS Rating Curve= 0 ,0
Exp/Cntr=0.5,0.3

Type RM Length L Ch R = 1 ,23550.0 ,75.6,106,121.4
BEGIN DESCRIPTION:
Upstream Section of Bridge/Culvert/Weir
END DESCRIPTION:
XS GIS Cut Line= 6
      3109476.43      13852105.7      3106548.14     13850328.71
      3106837.87     13849423.37      3106848.66     13848695.25
        3106322.     13848331.16      3104764.51     13846608.16
#Sta/Elev= 30
 166.986    57.4 1627.49    56.5 1763.65    58.71819.966      551885.323    57.9
2033.464    54.82120.607      602147.839    53.82339.552    55.32542.538   49.41
2551.634    48.72584.367   46.252643.297   30.042674.341   26.892698.523   15.05
 2724.23   12.772748.739   14.962772.812   27.282794.434   30.952837.297   44.33
2868.178   48.283651.042    55.13716.399    52.73770.863    38.53885.237    38.3
3907.023    41.53939.701    51.94026.244   54.894527.911    54.74561.134    58.5
#Mann= 6 ,-1 , 0
 166.986     .08       02542.538     .04       02674.341    .015       0
2772.812     .04       02868.178     .08       04026.244     .99       0
#XS Ineff= 2 , 0
       0 2406.75   53.27 2957.37       0   49.06
Permanent Ineff=
       F       F
#Block Obstruct= 1 ,-1
3638.8544043.172   54.65
Bank Sta=2551.634,2868.178
XS Rating Curve= 0 ,0
Skew Angle= 57
Exp/Cntr=0.5,0.3

Type RM Length L Ch R = 3 ,23506.5 ,,,
BEGIN DESCRIPTION:
DURHAM
Structure ID: E100-00-00-21
Bridge has a 57 degree skew with the channel.
END DESCRIPTION:
Bridge Culvert--1,0,-1,-1, 0
Deck Dist Width WeirC Skew NumUp NumDn MinLoCord MaxHiCord MaxSubmerge Is_Ogee
10,67,2.6,57, 60, 60, , , 0.95, 0, ,,,
 121.618 336.696 353.035 374.821 543.659 579.115 611.793 764.292 799.639 884.113
 952.1381082.8511093.7441202.6721224.4581382.4031417.8591434.1981605.705 1627.49
1684.7321747.311 1763.651804.5531826.3381885.3231972.4651982.922 1994.25 2075.51
2113.6352118.6462134.9252134.9852135.0452529.4132643.5152874.8172874.8772924.712
2924.7712969.5353032.6593098.0163147.0333174.2653324.8583504.5893553.6063564.499
3629.8563651.0423738.1853770.8633951.193 4016.554026.2444119.4324130.3254146.392
    56.9   57.91   56.85    56.4   57.61    57.1    57.8   57.61   58.11   57.33
   57.91    57.2   57.61   57.52   58.11      58    58.4    59.1   58.21    56.7
    58.8   58.01   58.71    56.2    56.3   57.91   56.41    56.5   57.44   56.86
   59.53      61    62.5    65.1    65.1   77.92   71.45   56.99   56.98   53.78
   51.18   48.97   50.02      52    51.3    52.9   52.93    53.9   54.37      55
    54.8   53.91   55.11   51.81   51.72    52.2    52.7    51.6    52.9    53.5
                                                                                
                                                                                
                                                                                
                                    56.7   69.52   63.05   48.59
                                                                                
                                                                                
 121.618 336.696 353.035 374.821 543.659 579.115 611.793 764.292 799.639 884.113
 952.1381082.8511093.7441202.6721224.4581382.4031417.8591434.1981605.705 1627.49
1684.7321747.311 1763.651804.5531826.3381885.3231972.4651982.922 1994.25 2075.51
2113.6352118.6462134.9252134.9852135.0452529.4132643.5152874.8172874.8772924.712
2924.7712969.5353032.6593098.0163147.0333174.2653324.8583504.5893553.6063564.499
3629.8563651.0423738.1853770.8633951.193 4016.554026.2444119.4324130.3254146.392
    56.9   57.91   56.85    56.4   57.61    57.1    57.8   57.61   58.11   57.33
   57.91    57.2   57.61   57.52   58.11      58    58.4    59.1   58.21    56.7
    58.8   58.01   58.71    56.2    56.3   57.91   56.41    56.5   57.44   56.86
   59.53      61    62.5    65.1    65.1   77.92   71.45   56.99   56.98   53.78
   51.18   48.97   50.02      52    51.3    52.9   52.93    53.9   54.37      55
    54.8   53.91   55.11   51.81   51.72    52.2    52.7    51.6    52.9    53.5
                                                                                
                                                                                
                                                                                
                                    56.7   69.52   63.05   48.59
                                                                                
                                                                                
Pier Skew, UpSta & Num, DnSta & Num=  ,2213.958, 2 ,2213.958, 2 , 0 , 0 , 0 ,,
       3       3
   51.17   67.75
       3       3
    51.1   67.68
Pier Skew, UpSta & Num, DnSta & Num=  ,2272.234, 2 ,2272.234, 2 , 0 , 0 , 0 ,,
       3       3
   50.45   68.63
       3       3
   50.38   68.56
Pier Skew, UpSta & Num, DnSta & Num=  ,2329.966, 2 ,2329.966, 2 , 0 , 0 , 0 ,,
       3       3
   49.73   69.52
       3       3
   49.66   69.45
Pier Skew, UpSta & Num, DnSta & Num=  ,2378.983, 2 ,2378.983, 2 , 0 , 0 , 0 ,,
       3       3
   49.01    70.4
       3       3
   48.94   70.33
Pier Skew, UpSta & Num, DnSta & Num=  ,2438.349, 2 ,2438.349, 2 , 0 , 0 , 0 ,,
       3       3
   47.73   69.12
       3       3
   47.66   69.05
Pier Skew, UpSta & Num, DnSta & Num=  ,2489, 2 ,2489, 2 , 0 , 0 , 0 ,,
       3       3
   47.73   69.12
       3       3
   47.66   69.05
Pier Skew, UpSta & Num, DnSta & Num=  ,2546.188, 2 ,2546.188, 2 , 0 , 0 , 0 ,,
       3       3
   47.73   69.12
       3       3
   47.66   69.05
Pier Skew, UpSta & Num, DnSta & Num=  ,2579.465, 2 ,2579.465, 2 , 0 , 0 , 0 ,,
       3       3
   45.54   67.43
       3       3
   45.47   67.36
Pier Skew, UpSta & Num, DnSta & Num=  ,2607.133, 2 ,2607.133, 2 , 0 , 0 , 0 ,,
       3       3
   38.16   65.89
       3       3
   38.09   65.82
Pier Skew, UpSta & Num, DnSta & Num=  ,2631.424, 2 ,2631.424, 2 , 0 , 0 , 0 ,,
       3       3
   31.53   64.69
       3       3
   31.46   64.62
Pier Skew, UpSta & Num, DnSta & Num=  ,2655.932, 2 ,2655.932, 2 , 0 , 0 , 0 ,,
       3       3
   28.97    63.3
       3       3
    28.9   63.23
Pier Skew, UpSta & Num, DnSta & Num=  ,2700.593, 2 ,2700.593, 2 , 0 , 0 , 0 ,,
       3       3
   14.01   60.61
       3       3
   13.94   60.54
Pier Skew, UpSta & Num, DnSta & Num=  ,2745.635, 2 ,2745.635, 2 , 0 , 0 , 0 ,,
       3       3
   13.86    57.8
       3       3
   13.79   57.73
Pier Skew, UpSta & Num, DnSta & Num=  ,2790.458, 2 ,2790.458, 2 , 0 , 0 , 0 ,,
       3       3
   28.91   55.01
       3       3
   28.84   54.94
Pier Skew, UpSta & Num, DnSta & Num=  ,2832.885, 2 ,2832.885, 2 , 0 , 0 , 0 ,,
       3       3
   42.12   52.34
       3       3
   42.05   52.27
Abutment Skew #Up #Dn= , 2 , 2
2078.2342642.044
   57.09   30.32
2078.2342642.044
   57.02   30.25
Abutment Skew #Up #Dn= , 2 , 2
2779.8922874.926
   28.15   48.59
2779.8922874.926
   28.08   48.52
BR Coef= 1 , 1 , 0 ,1.25, 0 ,,,0.8,0,1.2,0,
WSPro=,,,, 1 ,,,, 0 ,,,, 0 ,,,,-1 ,-1 ,-1 , 0 , 0 , 0 , 0 , 0
BR D #Sta/Elev= 30
 121.618   56.82 1627.49   56.42 1763.65   58.621819.966   54.921885.323   57.82
2033.464   54.722120.607   59.922147.839   53.722339.552   55.222542.538   49.33
2584.367   46.172643.297   29.96 2663.83   29.852674.341   26.812698.523   14.97
 2724.23   12.692748.739   14.882772.812    27.22794.434   30.872837.297   44.25
2868.178    48.23651.042   55.023716.399   52.623770.863   38.423885.237   38.22
3907.023   41.423939.701   51.824026.244   54.814527.911   54.624562.006   58.32
BR D #Mann= 6
 121.618     .082542.538     .042674.341    .0152772.812     .042868.178     .08
4026.244     .99
BC Design=,, 0 ,, 0 ,,,,,,
BC HTab HWMax=60
BC Use User HTab Curves=0
BC User HTab FreeFlow(D)= 0

Type RM Length L Ch R = 1 ,23444.0 ,358.7,264,41.7
BEGIN DESCRIPTION:
Downstream Section of Bridge/Culvert/Weir
END DESCRIPTION:
XS GIS Cut Line= 6
      3109517.14     13852038.84      3106607.73     13850272.65
      3106892.86     13849387.44      3106903.95     13848638.41
      3106366.98     13848267.19      3104811.82     13846546.77
#Sta/Elev= 30
 160.614   57.17 1627.49   56.42 1763.65   58.621819.966   54.921885.323   57.82
2033.464   54.722120.607   59.922147.839   53.722339.552   55.222542.538   49.33
2551.634   48.622584.367   46.172643.297   29.962674.341   26.812698.523   14.97
 2724.23   12.692748.739   14.882772.812    27.22794.434   30.872837.297   44.25
2868.178    48.23651.042   55.023716.399   52.623770.863   38.423885.237   38.22
3907.023   41.423939.701   51.824026.244   54.814527.911   54.624548.008   58.02
#Mann= 6 ,-1 , 0
 160.614     .08       02542.538     .04       02674.341    .015       0
2772.812     .04       02868.178     .08       04026.244     .99       0
#XS Ineff= 2 , 0
       02546.242    49.32883.047       0    48.5
Permanent Ineff=
       F       F
#Block Obstruct= 1 ,-1
3638.8544066.956   54.31
Bank Sta=2551.634,2868.178
XS Rating Curve= 0 ,0
Skew Angle= 57
Exp/Cntr=0.5,0.3

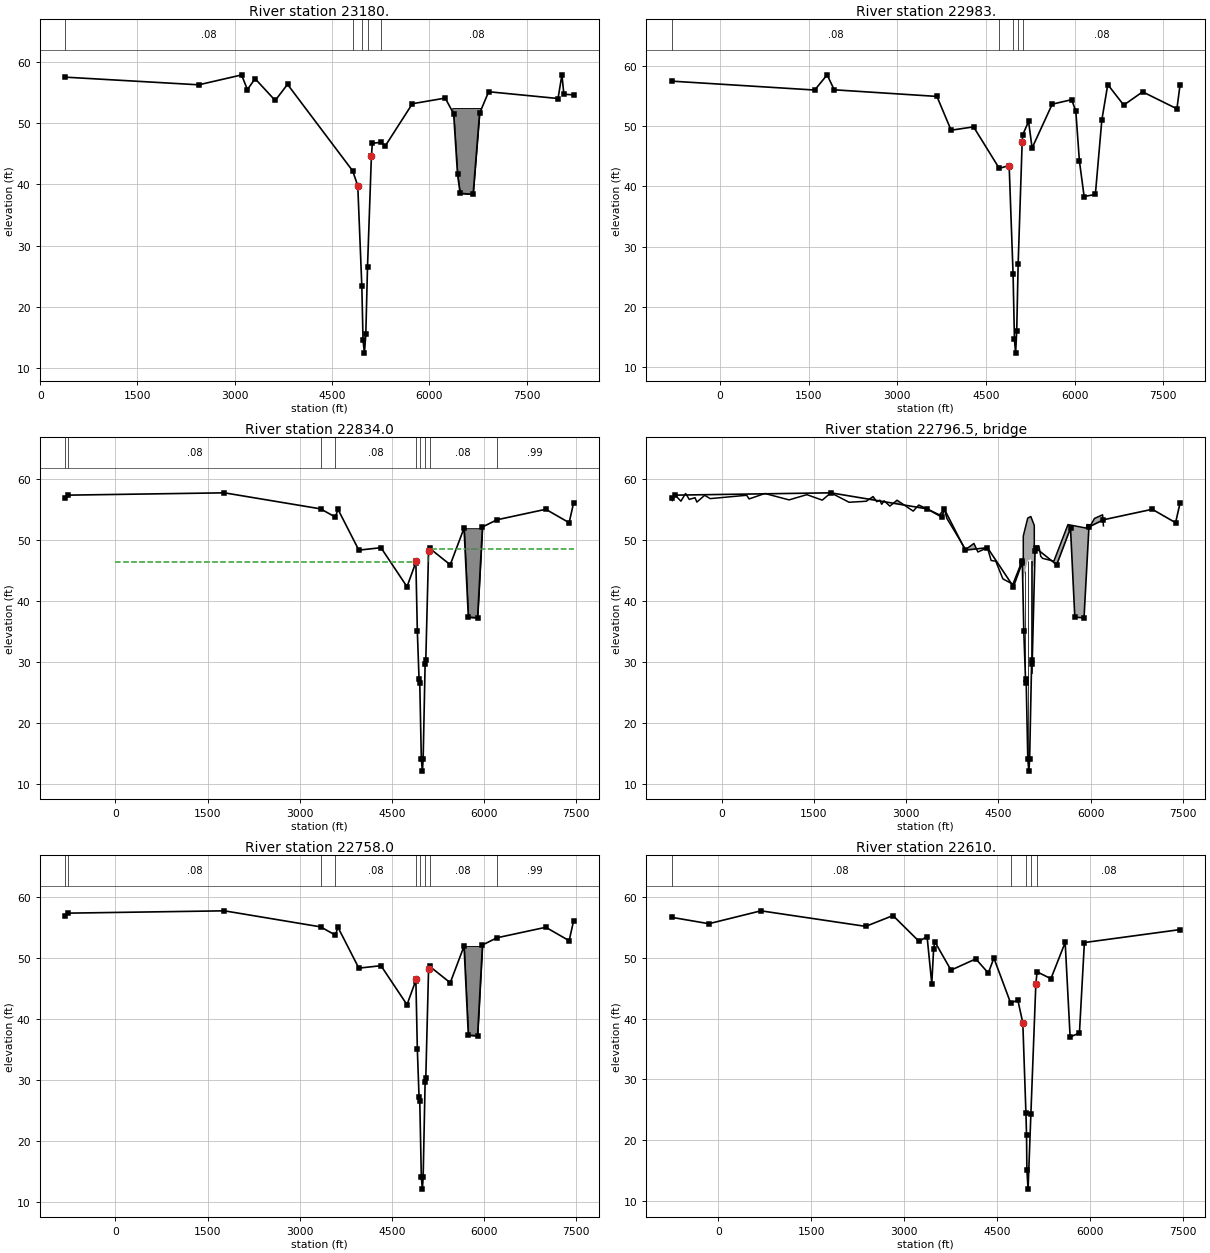
Type RM Length L Ch R = 1 ,23180.  ,214.4,197,98.5
BEGIN DESCRIPTION:
Durham Rd. - D/S - XS 1
END DESCRIPTION:
XS GIS Cut Line= 6
      3109573.74     13851951.11      3107086.47     13850404.67
      3107158.58     13848862.84      3106929.37     13848730.34
      3106925.06     13848603.36      3104868.42     13846459.04
#Sta/Elev= 30
   385.2   57.53  2445.2   56.28  3105.2   57.89  3195.2    55.5    3314   57.28
    3624   53.72    3814   56.35    4819   42.22  4897.5   39.78    4960   23.35
 4978.56   14.61    5000   12.46 5021.33   15.53  5047.5   26.52  5107.5   44.61
  5122.3   46.73  5249.4   46.88  5319.4   46.26  5739.4   53.19    6246   54.11
    6376   51.56    6436   41.66    6476   38.56    6676   38.39    6776   51.61
    6916   55.15    7986   54.04    8046   57.91    8076   54.74  8225.1   54.64
#Mann= 5 ,-1 , 0
   385.2     .08       0    4819     .04       0    4960    .015       0
  5047.5     .04       0  5249.4     .08       0
#Block Obstruct= 1 ,-1
    6355    6797    52.5
Bank Sta=4897.5,5107.5
XS Rating Curve= 0 ,0
Exp/Cntr=0.3,0.1

Type RM Length L Ch R = 1 ,22983.  ,59.7,149,269.7
BEGIN DESCRIPTION:
N. Shepherd - U/S - XS 4
END DESCRIPTION:
XS GIS Cut Line= 6
      3110927.42     13852807.64      3107596.75     13849920.92
      3107325.24     13848946.16      3107243.36      13848688.7
      3106955.27     13848511.25      3105346.62     13846504.37
#Sta/Elev= 30
  -818.8   57.51  1601.2   56.03  1811.2   58.56  1931.2   56.07  3668.8   54.97
  3908.8   49.35  4288.8   49.91    4723   43.01  4890.8   43.48 4957.13   25.42
 4980.41   14.56    5000   12.29 5018.96   16.02 5043.08   27.16  5110.8   47.36
  5120.8   48.59  5219.1   50.81  5279.1    46.4  5619.1   53.68  5949.1   54.43
  6019.1   52.49  6079.1   44.25  6159.1   38.33  6349.1   38.67  6459.1   51.07
  6559.1   56.94  6829.1   53.53  7149.1   55.73  7729.1   52.91  7781.2   56.84
#Mann= 5 ,-1 , 0
  -818.8     .08       0    4723     .04       0 4957.13    .015       0
 5043.08     .04       0  5120.8     .08       0
#Block Obstruct= 2 , 0
       0                 5949.55       0   54.46
Bank Sta=4890.8,5110.8
XS Rating Curve= 0 ,0
Exp/Cntr=0.5,0.3

Type RM Length L Ch R = 1 ,22834.0 ,75.7,76,86.4
BEGIN DESCRIPTION:
Upstream Section of Bridge/Culvert/Weir
END DESCRIPTION:
XS GIS Cut Line= 6
      3111006.66      13852756.7      3107675.99     13849869.98
      3107382.66     13848930.96      3107201.72     13848387.08
      3107212.55      13848022.6      3106773.99     13846131.29
#Sta/Elev= 30
  -815.4   56.91  -768.7   57.43  1774.6   57.81  3339.2   55.18  3580.4   53.83
  3622.2   55.11  3962.2   48.41  4322.2   48.81  4745.9   42.41  4887.3   46.34
  4889.8    46.6  4914.1   35.07  4941.7   27.29  4953.6   26.57  4979.1   14.13
  4996.1   12.16  5008.5   14.09  5040.5   29.71  5051.7   30.46    5097   48.31
    5113   48.72  5449.3   46.01  5673.9   52.01  5743.9   37.41  5893.9   37.31
  5973.9   52.21  6209.7   53.39  7003.9   55.11  7383.9   52.91  7455.4   56.11
#Mann= 9 ,-1 , 0
  -815.4     .99       0  -768.7     .08       0  3339.2     .05       0
  3580.4     .08       0  4887.3     .04       0  4953.6    .015       0
  5040.5     .04       0    5113     .08       0  6209.7     .99       0
#XS Ineff= 2 , 0
       0    4892    46.5 5092.25       0    48.6
Permanent Ineff=
       F       F
#Block Obstruct= 1 ,-1
    5674 6139.74   52.01
Bank Sta=4889.8,5097
XS Rating Curve= 0 ,0
Exp/Cntr=0.5,0.3

Type RM Length L Ch R = 3 ,22796.5 ,,,
BEGIN DESCRIPTION:
SHEPHERD E100-00-00-20
Structure ID: E100-00-00-20
END DESCRIPTION:
Bridge Culvert--1,0,-1,-1, 0
Deck Dist Width WeirC Skew NumUp NumDn MinLoCord MaxHiCord MaxSubmerge Is_Ogee
10,55,2.6,0, 60, 60, , , 0.95, 0, ,,,
  -815.4  -805.4  -765.4  -665.4  -588.7  -528.7  -435.4  -405.4  -278.7  -188.7
   404.6   444.6   701.3  1094.6  1384.6  1634.6  1774.6  2071.3  2351.3  2461.3
  2521.3  2571.3  2601.3  2641.3  2734.6  2851.3  3114.6  3204.6  3541.3  3622.2
  3662.2  3967.1  4102.2  4167.1  4322.2  4382.2  4457.1  4573.6  4735.9 4902.31
  4902.4 4905.49  4905.6  4977.6    5028 5082.59  5082.7  5084.7 5084.81  5159.3
  5189.3  5219.3  5403.1  5632.5  5932.5  5942.5  6003.9  6063.9  6196.1  6209.7
    56.9    56.5   57.51   56.44    57.7   56.73   57.01   56.29    57.4   56.86
   57.41   56.81    57.7   56.65   57.51   56.61   57.81   56.26   56.43    57.2
   56.36    56.6   55.93    56.5   55.63    56.6   54.81   55.81    54.2   55.11
   53.61    48.5   49.51    48.1   48.81   46.71    46.6    43.7   42.81   47.07
   47.08   47.23   50.73   53.66   53.93   52.52   52.51   52.45   48.95   49.11
   47.41   47.06    46.6    52.6   52.02    52.6   52.55   53.61   54.21    52.4
                                                                                
                                                                                
                                                                                
                                                                                
   43.58   43.73   43.73   46.66   46.93   45.52   42.67   43.45
                                                                                
  -815.4  -805.4  -765.4  -665.4  -588.7  -528.7  -435.4  -405.4  -278.7  -188.7
   404.6   444.6   701.3  1094.6  1384.6  1634.6  1774.6  2071.3  2351.3  2461.3
  2521.3  2571.3  2601.3  2641.3  2734.6  2851.3  3114.6  3204.6  3541.3  3622.2
  3662.2  3967.1  4102.2  4167.1  4322.2  4382.2  4457.1  4573.6  4735.9 4902.31
  4902.4 4905.49  4905.6  4977.6    5028 5082.59  5082.7  5084.7 5084.81  5159.3
  5189.3  5219.3  5403.1  5632.5  5932.5  5942.5  6003.9  6063.9  6196.1  6209.7
    56.9    56.5   57.51   56.44    57.7   56.73   57.01   56.29    57.4   56.86
   57.41   56.81    57.7   56.65   57.51   56.61   57.81   56.26   56.43    57.2
   56.36    56.6   55.93    56.5   55.63    56.6   54.81   55.81    54.2   55.11
   53.61    48.5   49.51    48.1   48.81   46.71    46.6    43.7   42.81   47.07
   47.08   47.23   50.73   53.66   53.93   52.52   52.51   52.45   48.95   49.11
   47.41   47.06    46.6    52.6   52.02    52.6   52.55   53.61   54.21    52.4
                                                                                
                                                                                
                                                                                
                                                                                
   43.58   43.73   43.73   46.66   46.93   45.52   42.67   43.45
                                                                                
Pier Skew, UpSta & Num, DnSta & Num=  ,4938.3, 2 ,4938.3, 2 , 0 , 0 , 0 ,,
     3.5     3.5
   26.74   46.19
     3.5     3.5
   26.71   46.16
Pier Skew, UpSta & Num, DnSta & Num=  ,4982.2, 2 ,4982.2, 2 , 0 , 0 , 0 ,,
     3.5     3.5
   13.14   47.69
     3.5     3.5
   13.11   47.66
Pier Skew, UpSta & Num, DnSta & Num=  ,5037.5, 2 ,5037.5, 2 , 0 , 0 , 0 ,,
     3.5     3.5
   26.16   47.73
     3.5     3.5
   26.13    47.7
BR Coef= 1 , 1 , 0 ,1.25, 0 ,,,0.8,0,2,0,
WSPro=,,,, 1 ,,,, 0 ,,,, 0 ,,,,-1 ,-1 ,-1 , 0 , 0 , 0 , 0 , 0
BR D #Sta/Elev= 30
  -815.4   56.86  -768.7   57.38  1774.6   57.76  3339.2   55.13  3580.4   53.78
  3622.2   55.06  3962.2   48.36  4322.2   48.76  4745.9   42.36  4887.3   46.29
  4914.1   35.02  4941.7   27.24  4953.6   26.52  4979.1   14.08  4996.1   12.11
  5008.5   14.04  5040.5   29.66  5051.7   30.41    5097   48.26    5113   48.67
  5449.3   45.96  5673.9   51.96  5743.9   37.36  5893.9   37.26  5973.9   52.16
  6209.7   53.34  6553.9   52.46  7003.9   55.06  7383.9   52.86  7455.4   56.06
BR D #Mann= 9
  -815.4     .99  -768.7     .08  3339.2     .05  3580.4     .08  4887.3     .04
  4953.6    .015  5040.5     .04    5113     .08  6209.7     .99
BC Design=,, 0 ,, 0 ,,,,,,
BC HTab HWMax=57.81
BC Use User HTab Curves=0
BC User HTab FreeFlow(D)= 0

Type RM Length L Ch R = 1 ,22758.0 ,99.5,148,173.3
BEGIN DESCRIPTION:
Downstream Section of Bridge/Culvert/Weir
END DESCRIPTION:
XS GIS Cut Line= 6
      3111070.79     13852722.75      3107746.56     13849841.62
      3107455.53     13848909.94      3107276.33     13848371.66
      3107287.13     13848008.34      3106847.69     13846113.24
#Sta/Elev= 30
  -815.4   56.86  -768.7   57.38  1774.6   57.76  3339.2   55.13  3580.4   53.78
  3622.2   55.06  3962.2   48.36  4322.2   48.76  4745.9   42.36  4887.3   46.29
  4889.8   46.55  4914.1   35.02  4941.7   27.24  4953.6   26.52  4979.1   14.08
  4996.1   12.11  5008.5   14.04  5040.5   29.66  5051.7   30.41    5097   48.26
    5113   48.67  5449.3   45.96  5673.9   51.96  5743.9   37.36  5893.9   37.26
  5973.9   52.16  6209.7   53.34  7003.9   55.06  7383.9   52.86  7455.4   56.06
#Mann= 9 ,-1 , 0
  -815.4     .99       0  -768.7     .08       0  3339.2     .05       0
  3580.4     .08       0  4887.3     .04       0  4953.6    .015       0
  5040.5     .04       0    5113     .08       0  6209.7     .99       0
#XS Ineff= 2 , 0
       0    4892   43.25 5092.25       0   45.35
Permanent Ineff=
       F       F
#Block Obstruct= 1 ,-1
 5650.65 6157.21      52
Bank Sta=4889.8,5097
XS Rating Curve= 0 ,0
Exp/Cntr=0.5,0.3

Type RM Length L Ch R = 1 ,22610.  ,123.5,386,574.5
BEGIN DESCRIPTION:
N. Shepherd - D/S - XS 1
END DESCRIPTION:
XS GIS Cut Line= 6
      3111169.83     13852694.45      3108046.39      13849907.8
      3107608.39     13849153.87      3107487.61     13848703.06
      3107443.25     13848292.25      3106946.74     13846084.94
#Sta/Elev= 30
  -751.5   56.65  -151.5    55.6   688.5   57.72  2378.5   55.16  2818.5   56.94
  3238.5    52.7  3368.5   53.49  3444.4   45.74  3474.4    51.5  3494.4   52.62
  3754.4   47.96  4154.4   49.81  4356.3   47.48  4446.3   49.95    4716   42.56
    4833   43.01    4913   39.27    4963   24.46    4973   20.89 4978.47   15.13
  4997.9   11.92    5043   24.27    5123   45.66    5143   47.68  5366.2   46.55
  5596.2   52.51  5676.2   36.97  5826.2    37.6  5906.2    52.5  7448.6   54.63
#Mann= 5 ,-1 , 0
  -751.5     .08       0    4716     .04       0    4963    .015       0
    5043     .04       0    5143     .08       0
#Block Obstruct= 2 , 0
       0                  5596.2       0    52.5
Bank Sta=4913,5123
XS Rating Curve= 0 ,0
Exp/Cntr=0.3,0.1

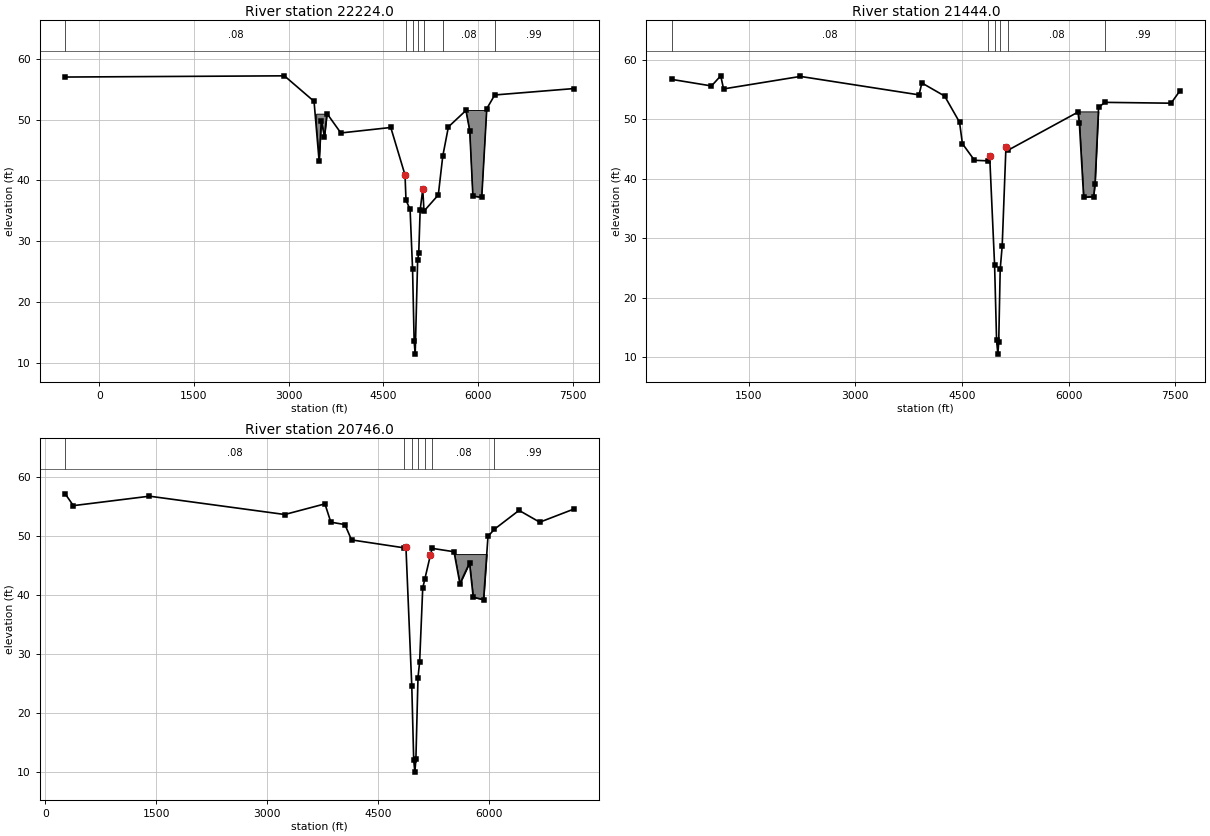
Type RM Length L Ch R = 1 ,22224.0 ,907.7,780,341.1
BEGIN DESCRIPTION:
Cross Section E100-00-00-X16
Located At: DS SHEPHERD
END DESCRIPTION:
XS GIS Cut Line= 6
      3111100.62     13852586.94      3108093.94     13849881.88
      3107652.54      13849166.7      3107628.51     13848761.36
      3108111.71     13848052.49      3107984.16     13846193.51
#Sta/Elev= 30
  -538.8      57  2931.2    57.2  3401.2      53  3481.2    43.2  3515.6    49.8
  3565.6    47.2  3605.6      51  3825.6    47.8  4616.1    48.7  4841.4   40.89
  4857.1   36.73  4921.9   35.23    4961   25.39    4986    13.5  5002.6   11.41
  5041.4   26.86  5058.7   28.02  5081.3   35.13  5122.5   38.53  5141.9   34.94
  5368.5    37.6  5439.4      44  5528.5    48.8  5806.3    51.5  5866.3    48.2
  5916.3    37.4  6056.3    37.2  6136.3    51.8  6261.9   54.05  7509.7    55.1
#Mann= 7 ,-1 , 0
  -538.8     .08       0  4857.1     .04       0    4961    .015       0
  5041.4     .04       0  5141.9      .1       0  5439.4     .08       0
  6261.9     .99       0
#Block Obstruct= 2 ,-1
 3434.19 3605.96   50.97  5787.8  6144.1    51.5
Bank Sta=4841.4,5122.5
XS Rating Curve= 0 ,0
Exp/Cntr=0.3,0.1

Type RM Length L Ch R = 1 ,21444.0 ,726.4,698,462.1
BEGIN DESCRIPTION:
Cross Section E100-00-00-X15
Located At: S. LARENCE PARK
END DESCRIPTION:
XS GIS Cut Line= 6
      3111264.11     13852514.28      3108929.75     13849934.54
      3108489.37     13849163.12      3108395.63     13848795.86
      3108311.55     13848355.78       3108235.7     13846401.93
#Sta/Elev= 30
   415.6    56.7   975.6    55.6  1105.6    57.3  1145.6    55.1  2225.6    57.2
  3894.7    54.1  3934.7    56.1  4254.7    53.9  4464.7    49.5  4504.7    45.9
  4674.7    43.1  4860.1   43.01  4888.5    43.8  4957.5   25.52  4985.5   12.85
  5003.5   10.52  5015.6   12.49  5036.4   24.78  5064.4    28.7  5117.3   45.32
  5144.1   44.78  6130.1    51.2  6150.1    49.3  6210.1    36.9  6350.1      37
  6370.1    39.2  6420.1      52    6509   52.84  7440.1    52.7  7565.4    54.8
#Mann= 6 ,-1 , 0
   415.6     .08       0  4860.1     .04       0  4957.5    .015       0
  5036.4     .04       0  5144.1     .08       0    6509     .99       0
#Block Obstruct= 1 ,-1
  6128.8  6420.2   51.32
Bank Sta=4888.5,5117.3
XS Rating Curve= 0 ,0
Exp/Cntr=0.3,0.1

Type RM Length L Ch R = 1 ,20746.0 ,7.9,102,206.3
BEGIN DESCRIPTION:
Cross Section E100-00-00-X14
Located At: 3RD US I-10
END DESCRIPTION:
XS GIS Cut Line= 6
      3111409.44     13852368.95      3109411.48     13849601.12
      3109032.06     13848678.61      3108704.43     13848242.68
       3108746.1     13848159.35      3108329.14     13846380.37
#Sta/Elev= 30
   270.3    57.1   380.3    55.1  1410.3    56.7  3240.3    53.6  3783.9    55.4
  3863.9    52.3  4053.9    51.9  4143.9    49.3    4850   47.97  4879.7   48.12
    4959    24.5  4984.8   12.07  5000.4      10  5014.4   12.15    5043      26
  5065.3   28.71    5107   41.15  5136.2   42.72  5211.4   46.76  5234.2   47.87
  5529.9    47.3  5609.9    41.9  5739.9    45.4  5789.9    39.6  5929.9    39.2
  5989.9    49.9  6077.9   51.12  6409.9    54.3  6689.9    52.3  7147.1    54.5
#Mann= 7 ,-1 , 0
   270.3     .08       0    4850     .04       0    4959    .015       0
    5043     .04       0  5136.2     .12       0  5234.2     .08       0
  6077.9     .99       0
#Block Obstruct= 1 ,-1
 5519.65 6204.37    46.9
Bank Sta=4879.7,5211.4
XS Rating Curve= 0 ,0
Exp/Cntr=0.5,0.3