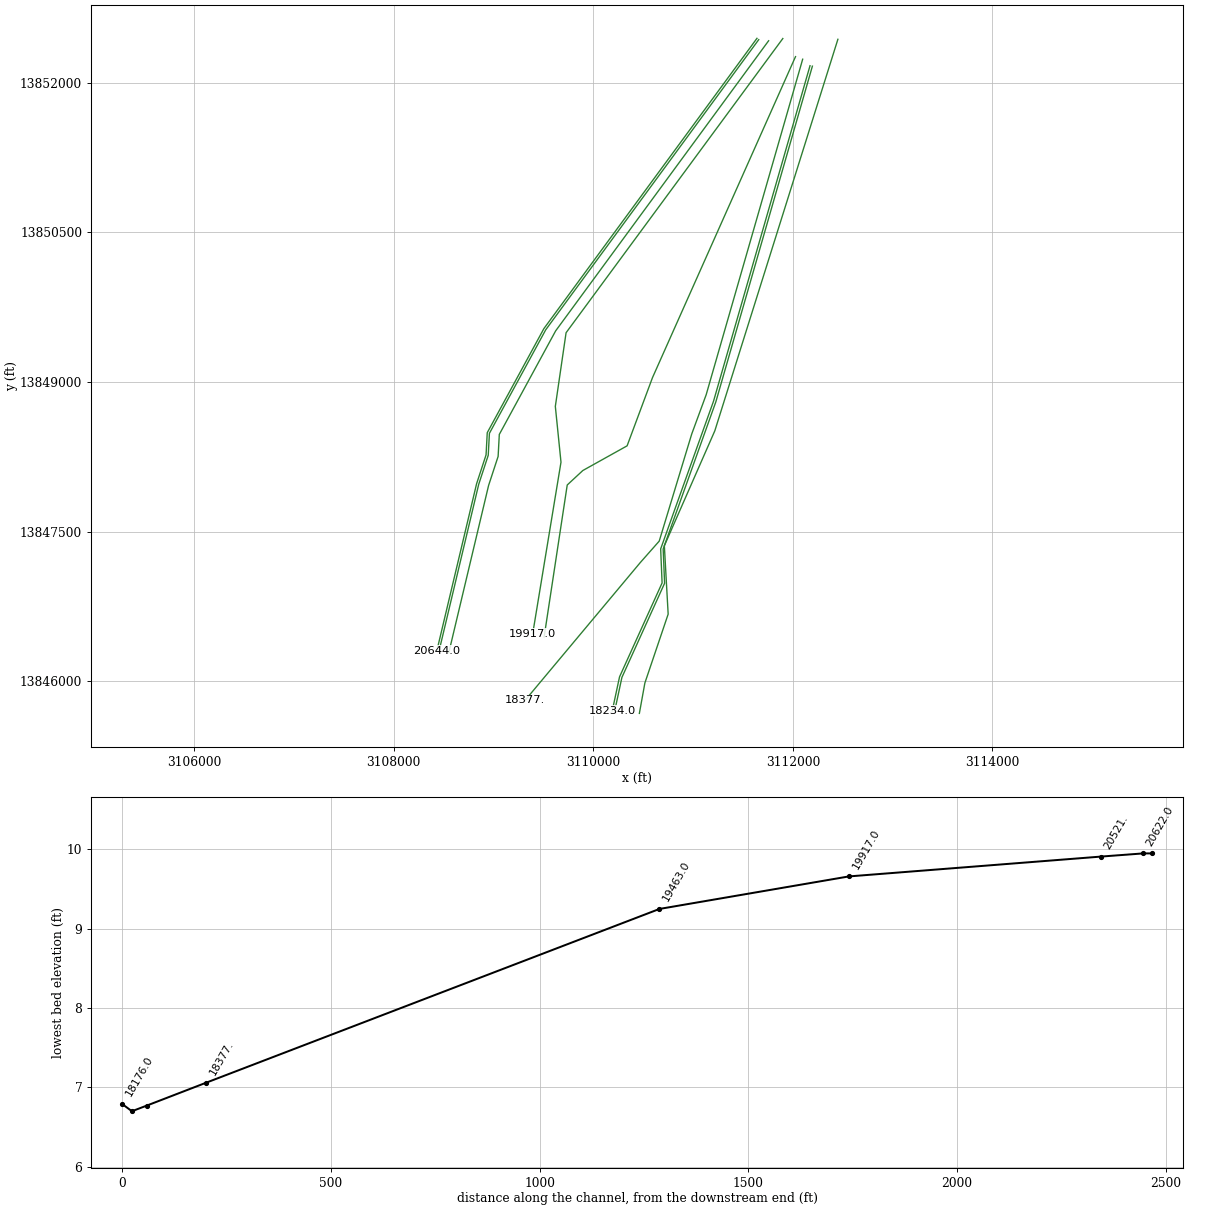
HEC-RAS study E100-00-00.prj: E100-00-00

--- E100-00-00.g02 (geometry) --- (continued)

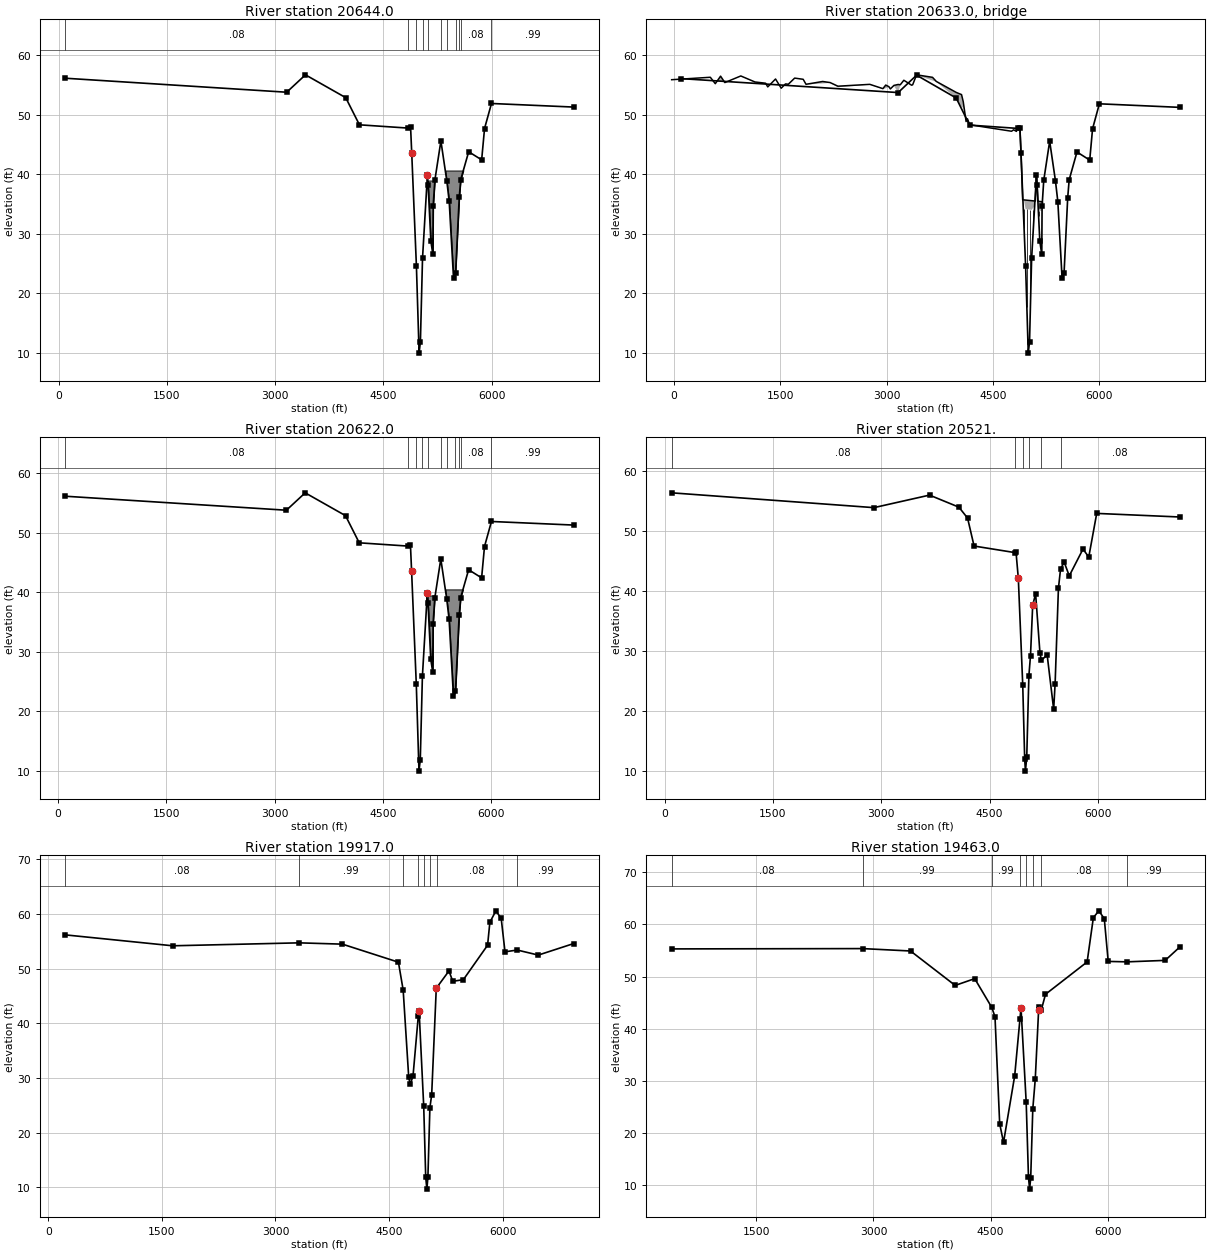
Type RM Length L Ch R = 1 ,20644.0 ,23.7,22,21
BEGIN DESCRIPTION:
Upstream Section of Bridge/Culvert/Weir
END DESCRIPTION:
XS GIS Cut Line= 6
      3111640.74     13852443.38      3109505.57     13849534.77
      3108937.84     13848491.45      3108925.93     13848269.08
      3108831.15     13847980.25      3108432.08     13846303.08
#Sta/Elev= 30
    90.3   56.09  3160.7   53.74  3420.7   56.66  3978.9   52.83  4168.9   48.27
  4844.7   47.72 4878.29   47.82 4893.59   43.62 4958.79   24.57 4996.19    9.95
 5014.19   11.87 5043.49   25.86 5111.29   39.82    5121   38.18 5159.29   28.73
 5186.89   26.53 5191.19   34.64 5214.49   38.97  5298.3   45.56  5379.8   38.89
  5413.3   35.42  5473.3   22.56  5501.2    23.4  5552.7   36.09  5573.5   39.09
  5683.3   43.75  5863.3   42.39  5903.3   47.65  5999.3   51.85  7136.9   51.25
#Mann= 11 ,-1 , 0
    90.3     .08       0  4844.7     .04       0 4958.79    .015       0
 5043.49     .04       0    5121     .12       0  5298.3     .08       0
  5379.8     .04       0  5501.2     .08       0  5552.7     .04       0
  5573.5     .08       0  5999.3     .99       0
#Block Obstruct= 2 ,-1
 5110.85 5233.73   38.92 5343.09 5628.18    40.6
Bank Sta=4893.59,5111.29
XS Rating Curve= 0 ,0
Exp/Cntr=0.5,0.3

Type RM Length L Ch R = 3 ,20633.0 ,,,
BEGIN DESCRIPTION:
PL1_E100-00-00-19a
END DESCRIPTION:
Bridge Culvert--1,0,-1,-1, 0
Deck Dist Width WeirC Skew NumUp NumDn MinLoCord MaxHiCord MaxSubmerge Is_Ogee
10,2,2.6,0, 60, 60, , , 0.95, 0, ,,,
   -34.6   510.7   580.7   655.4   715.4   940.7  1110.7  1140.7  1290.7  1320.7
  1430.7  1510.7  1570.7  1590.7  1610.7  1700.7  1820.7  1860.7  2095.4  2200.7
  2310.7  2760.7  2945.4  2985.4  3030.7  3050.7  3100.7  3160.7  3190.7  3240.7
  3350.7  3365.4  3420.7  3645.4  3698.9  3978.9  4008.9  4054.9  4078.9  4108.9
  4118.9  4138.9  4168.9 4759.99 4790.39 4829.59 4834.39 4878.29 4893.59 4912.99
    4917 5086.39 5095.99 5111.29 5115.99 5132.65 5138.99 5190.76 5191.19 5195.12
    55.9   56.31   55.23    56.5   55.42   56.53   55.67   55.52   55.31   54.69
   56.02   54.47   55.19   55.17   55.14   56.17   55.97   55.13    55.6   55.42
   54.81   55.12    54.4      55   54.72   54.35   54.94    55.1   55.05   55.81
   54.97   55.05   56.72    56.3   55.61   53.77   53.62    53.4    52.2   49.74
   48.87   49.33   48.33   47.24   47.48   47.21   47.62   47.88   43.68   37.22
   35.72   35.52   35.51   39.88   39.42   35.48   35.46   35.39   35.39   35.32
   55.85   56.25    54.8   55.25   55.36   56.47   55.59   54.71   55.25   54.58
   55.96   53.89    55.1   54.52   54.61   56.11   55.91   55.07   55.27   55.36
   54.63   55.06   54.31   54.47   54.66   54.29   54.88   53.74   54.99   55.75
   54.71   54.99   56.66   55.76   55.55   52.83   51.13   51.34   51.17   48.95
   48.81   49.27   48.27   46.49   47.42   46.85   47.56   47.82   43.62   37.16
   34.21   33.97   35.51   39.88   39.42   35.48   33.91   33.84   34.64   35.32
   -34.6   510.7   580.7   655.4   715.4   940.7  1110.7  1140.7  1290.7  1320.7
  1430.7  1510.7  1570.7  1590.7  1610.7  1700.7  1820.7  1860.7  2095.4  2200.7
  2310.7  2760.7  2945.4  2985.4  3030.7  3050.7  3100.7  3160.7  3190.7  3240.7
  3350.7  3365.4  3420.7  3645.4  3698.9  3978.9  4008.9  4054.9  4078.9  4108.9
  4118.9  4138.9  4168.9 4759.99 4790.39 4829.59 4834.39 4878.29 4893.59 4912.99
    4917 5086.39 5095.99 5111.29 5115.99 5132.65 5138.99 5190.76 5191.19 5195.12
    55.9   56.31   55.23    56.5   55.42   56.53   55.67   55.52   55.31   54.69
   56.02   54.47   55.19   55.17   55.14   56.17   55.97   55.13    55.6   55.42
   54.81   55.12    54.4      55   54.72   54.35   54.94    55.1   55.05   55.81
   54.97   55.05   56.72    56.3   55.61   53.77   53.62    53.4    52.2   49.74
   48.87   49.33   48.33   47.24   47.48   47.21   47.62   47.88   43.68   37.22
   35.72   35.52   35.51   39.88   39.42   35.48   35.46   35.39   35.39   35.32
   55.85   56.25    54.8   55.25   55.36   56.47   55.59   54.71   55.25   54.58
   55.96   53.89    55.1   54.52   54.61   56.11   55.91   55.07   55.27   55.36
   54.63   55.06   54.31   54.47   54.66   54.29   54.88   53.74   54.99   55.75
   54.71   54.99   56.66   55.76   55.55   52.83   51.13   51.34   51.17   48.95
   48.81   49.27   48.27   46.49   47.42   46.85   47.56   47.82   43.62   37.16
   34.21   33.97   35.51   39.88   39.42   35.48   33.91   33.84   34.64   35.32
Pier Skew, UpSta & Num, DnSta & Num=  ,4936.8, 2 ,4936.8, 2 , 0 , 0 , 0 ,,
       2       2
   28.15   35.15
       2       2
   28.15   35.15
Pier Skew, UpSta & Num, DnSta & Num=  ,4976.5, 2 ,4976.5, 2 , 0 , 0 , 0 ,,
       2       2
   14.81   35.11
       2       2
   14.81   35.11
Pier Skew, UpSta & Num, DnSta & Num=  ,5026.6, 2 ,5026.6, 2 , 0 , 0 , 0 ,,
       2       2
   16.31   35.04
       2       2
   16.31   35.04
Pier Skew, UpSta & Num, DnSta & Num=  ,5066.2, 2 ,5066.2, 2 , 0 , 0 , 0 ,,
       2       2
   27.28   34.99
       2       2
   27.28   34.99
Pier Skew, UpSta & Num, DnSta & Num=  ,5106.5, 2 ,5106.5, 2 , 0 , 0 , 0 ,,
       2       2
   37.16   39.73
       2       2
   37.16   39.73
Pier Skew, UpSta & Num, DnSta & Num=  ,5141.8, 2 ,5141.8, 2 , 0 , 0 , 0 ,,
       2       2
   31.93   34.91
       2       2
   31.93   34.91
BR Coef= 1 , 1 , 0 ,1.25, 0 ,,,0.8,0,2,0,
WSPro=,,,, 1 ,,,, 0 ,,,, 0 ,,,,-1 ,-1 ,-1 , 0 , 0 , 0 , 0 , 0
BC Design=,, 0 ,, 0 ,,,,,,
BC HTab HWMax=56.66
BC Use User HTab Curves=0
BC User HTab FreeFlow(D)= 0

Type RM Length L Ch R = 1 ,20622.0 ,95.4,101,102
BEGIN DESCRIPTION:
Downstream Section of Bridge/Culvert/Weir
END DESCRIPTION:
XS GIS Cut Line= 6
      3111658.47     13852430.37      3109524.18     13849522.95
      3108959.55     13848485.31      3108947.74     13848264.99
      3108852.34     13847974.27      3108453.48     13846297.99
#Sta/Elev= 30
    98.2   56.09  3160.7   53.74  3420.7   56.66  3978.9   52.83  4168.9   48.27
  4844.7   47.72 4878.29   47.82 4893.59   43.62 4958.79   24.57 4996.19    9.95
 5014.19   11.87 5043.49   25.86 5111.29   39.82    5121   38.18 5159.29   28.73
 5186.89   26.53 5191.19   34.64 5214.49   38.97  5298.3   45.56  5379.8   38.89
  5413.3   35.42  5473.3   22.56  5501.2    23.4  5552.7   36.09  5573.5   39.09
  5683.3   43.75  5863.3   42.39  5903.3   47.65  5999.3   51.85  7135.9   51.25
#Mann= 11 ,-1 , 0
    98.2     .08       0  4844.7     .04       0 4958.79    .015       0
 5043.49     .04       0    5121     .12       0  5298.3     .08       0
  5379.8     .04       0  5501.2     .08       0  5552.7     .04       0
  5573.5     .08       0  5999.3     .99       0
#Block Obstruct= 2 ,-1
  5112.6 5257.02   39.43 5340.49 5609.44   40.45
Bank Sta=4893.59,5111.29
XS Rating Curve= 0 ,0
Exp/Cntr=0.5,0.3

Type RM Length L Ch R = 1 ,20521.  ,536.1,604,700.9
BEGIN DESCRIPTION:
PL_19a - D/S - XS 1
END DESCRIPTION:
XS GIS Cut Line= 6
      3111757.52     13852419.05      3109623.23     13849511.63
       3109058.6     13848473.99      3109046.79     13848253.67
      3108951.39     13847962.95      3108552.53     13846286.67
#Sta/Elev= 30
    99.1    56.3  2899.1   53.83  3669.1   55.92  4075.8   53.91  4195.8   52.09
  4285.8   47.43    4850   46.34  4865.8    46.5 4898.42   42.04 4959.44   24.31
 4986.55   11.89 4996.85    9.91 5015.05   12.27 5044.69   25.83  5067.1   29.18
  5097.1   37.52  5137.7    39.5  5197.7   29.61  5217.7   28.39  5297.7   29.28
  5387.7   20.22  5407.7   24.46  5453.7   40.39  5483.7   43.65  5533.7   44.73
  5603.7   42.46  5793.7   46.92  5873.7    45.6  5983.7   52.87  7136.8   52.27
#Mann= 6 ,-1 , 0
    99.1     .08       0    4850     .04       0 4959.44    .015       0
 5044.69     .04       0  5217.7     .12       0  5483.7     .08       0
#Block Obstruct= 2 , 0
       0                  5138.5       0   39.49
Bank Sta=4898.42,5097.1
XS Rating Curve= 0 ,0
Exp/Cntr=0.3,0.1

Type RM Length L Ch R = 1 ,19917.0 ,668.4,454,205.1
BEGIN DESCRIPTION:
Cross Section E100-00-00-X13
Located At: 2ND US I-10
END DESCRIPTION:
XS GIS Cut Line= 5
      3111899.92     13852441.62       3109727.8     13849493.23
      3109620.09     13848754.87       3109676.8     13848196.06
      3109392.83      13846473.8
#Sta/Elev= 30
   222.8    56.2  1642.8    54.2  3313.9   54.74  3884.9    54.5  4624.9    51.2
  4687.6    46.1  4761.1    30.1  4780.5   28.85  4817.5   30.33  4887.6   41.37
    4898   42.32  4959.1   24.83  4985.5   11.81  5000.8    9.66  5014.4   11.83
  5040.6   24.55  5064.2   26.92    5125   46.45  5131.3   46.55  5292.8    49.6
  5342.8    47.7  5482.8      48  5802.8    54.3  5832.8    58.5  5912.8    60.6
  5982.8    59.2  6032.8    53.1  6195.2   53.42  6472.8    52.5  6938.3    54.6
#Mann= 8 ,-1 , 0
   222.8     .08       0  3313.9     .99       0  4687.6     .99       0
  4887.6     .04       0  4959.1    .015       0  5040.6     .04       0
  5131.3     .08       0  6195.2     .99       0
#Block Obstruct= 1 ,-1
    7000    7001      50
Bank Sta=4898,5125
XS Rating Curve= 0 ,0
Exp/Cntr=0.3,0.1

Type RM Length L Ch R = 1 ,19463.0 ,931.6,1086,1112.3
BEGIN DESCRIPTION:
Cross Section E100-00-00-X12
Located At: US I-10
END DESCRIPTION:
XS GIS Cut Line= 6
      3112027.09     13852259.96      3110593.68     13849042.96
      3110339.28     13848359.61      3109895.82     13848112.43
      3109739.38     13847967.43      3109507.82     13846445.06
#Sta/Elev= 30
   415.2    55.3  2860.4   55.36  3475.2    54.9  4047.1    48.3  4297.1    49.6
  4515.2    44.1  4557.1    42.3  4617.1    21.8  4666.3    18.2  4809.3   30.96
  4876.6   41.82  4890.2   44.02  4956.8    25.9    4986    11.5  5000.8    9.25
  5014.6   11.39  5041.3   24.63  5072.8   30.31    5118   44.21  5124.5   43.64
  5150.1   43.59    5204    46.6  5737.3    52.8  5817.3    61.3  5887.3    62.6
  5957.3    61.1  6007.3    52.9    6251   52.82  6737.3    53.1  6927.1    55.7
#Mann= 8 ,-1 , 0
   415.2     .08       0  2860.4     .99       0  4515.2     .99       0
  4876.6     .04       0  4956.8    .015       0  5041.3     .04       0
  5150.1     .08       0    6251     .99       0
#Block Obstruct= 1 ,-1
    7000    7001      50
Bank Sta=4890.2,5124.5
XS Rating Curve= 0 ,0
Exp/Cntr=0.3,0.1

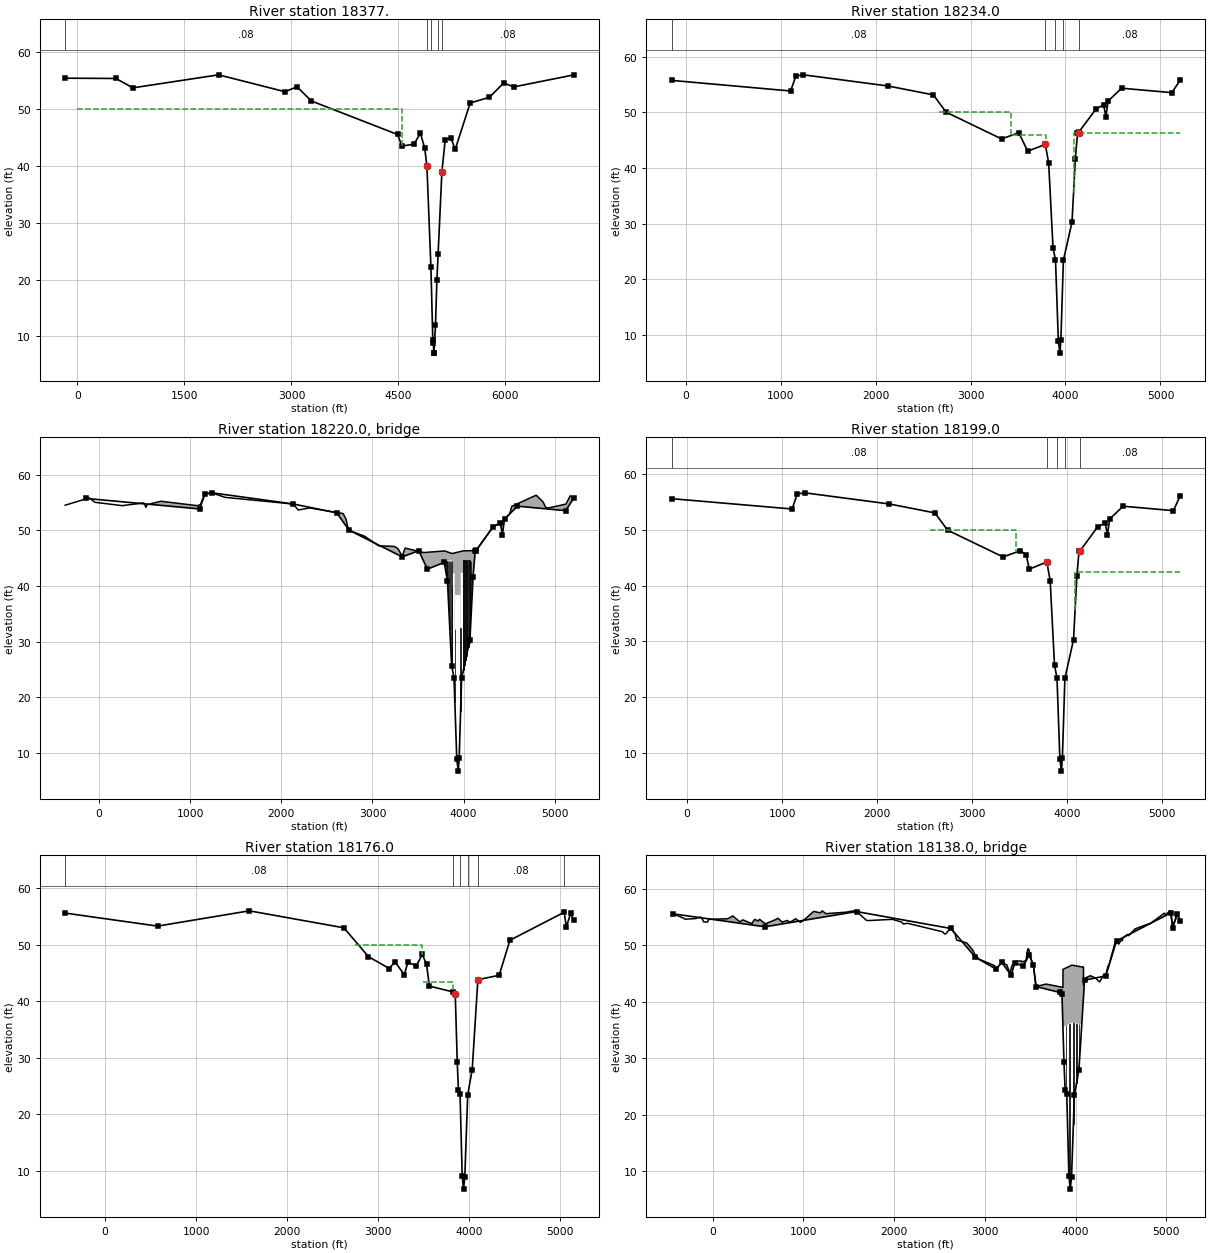
Type RM Length L Ch R = 1 ,18377.  ,54.5,143,315.1
BEGIN DESCRIPTION:
Union Pacific RR6 - U/S - XS 4
END DESCRIPTION:
XS GIS Cut Line= 6
      3112098.83     13852234.21      3111132.04     13848872.69
       3110986.7     13848477.54      3110661.07     13847404.65
      3110471.36     13847189.81      3109317.67     13845810.03
#Sta/Elev= 30
    -171   55.44     539   55.39     779   53.74    1979   56.03    2909   53.06
    3079   53.92    3279   51.43  4487.8   45.53  4547.8   43.52  4717.8    43.8
  4807.8   45.77    4869   43.09    4899   39.95    4955   22.26 4981.72    9.29
 4991.24    8.88 4993.26    7.17 4997.59    7.06    5019   11.95    5039   19.92
    5056   24.54    5109   38.95  5155.6    44.6  5235.6   44.92  5295.6   42.91
  5505.6   51.08  5775.6   52.08  5975.6   54.61  6115.6    53.9  6954.2   56.01
#Mann= 5 ,-1 , 0
    -171     .08       0    4899     .04       0    4955    .015       0
    5056     .04       0    5109     .08       0
#XS Ineff= 2 , 0
       0    4547      50               0
Permanent Ineff=
       F       F
Bank Sta=4899,5109
XS Rating Curve= 0 ,0
Exp/Cntr=0.5,0.3

Type RM Length L Ch R = 1 ,18234.0 ,36,35,23.9
BEGIN DESCRIPTION:
Upstream Section of Bridge/Culvert/Weir
END DESCRIPTION:
XS GIS Cut Line= 6
      3112172.41     13852169.13      3111205.62      13848807.6
      3110675.67      13847326.5      3110689.97     13846985.45
      3110263.65     13846044.65       3110190.5     13845703.85
#Sta/Elev= 30
-147.673   55.721105.264   53.821160.425   56.521239.226   56.722129.678   54.72
2608.631   53.122742.593   50.023326.509   45.223507.751   46.323602.312   43.02
3787.499   44.233822.869   40.883868.541   25.713894.665    23.53924.767       9
3940.921    6.773951.323    9.073977.643    23.44068.656   30.294103.741   41.65
4126.421    46.24139.105   46.344139.186   46.424323.027   50.624401.829   51.32
 4425.47   49.224449.109   52.024590.951   54.325120.415   53.525205.993   55.72
#Mann= 5 ,-1 , 0
-147.673     .08       03787.499     .04       03894.665    .015       0
3977.643     .04       04139.186     .08       0
#XS Ineff= 3 ,-1
2670.791 3430.93      50 4084.845205.993   46.34 3437.543794.061      46
Permanent Ineff=
       F       F       F
Bank Sta=3787.499,4139.105
XS Rating Curve= 0 ,0
Skew Angle= 38
Exp/Cntr=0.5,0.3

Type RM Length L Ch R = 3 ,18220.0 ,,,
BEGIN DESCRIPTION:
UNION PACIFIC RAILROAD  E100-00-00-18
Structure ID: E100-00-00-18
Bridge has 38 degree skew with the channel.
Column for pier structures are skewed at an angle with the channel but PBS&J made the assumption that the diameter of the columns times the number of columns is the amount blocked by the structures; the two middle columns flanking the channel are parallel
END DESCRIPTION:
Bridge Culvert--1,0,-1,-1, 0
Deck Dist Width WeirC Skew NumUp NumDn MinLoCord MaxHiCord MaxSubmerge Is_Ogee
10,10,2.6,38, 60, 60, , , 0.95, 0, ,,,
 -371.47 -108.27  -45.23  254.21  490.62  514.26  526.86  679.74 1081.62 1113.14
 1160.43 1239.23 1381.07 2129.68 2184.84 2310.92 2678.13 2709.65 2733.29 2742.59
 2915.96 3066.31 3239.67 3279.23 3326.51 3357.87 3562.75  3792.5 3874.65 3874.66
 3876.63 3876.64 3901.72 3901.73 3905.66 3905.67    3965 3965.01 3968.94 3968.95
 3992.69  3992.7 3994.67 3994.68 4084.84 4084.94 4139.19 4323.03 4401.83 4410.42
 4449.11 4504.98 4528.62 4796.54 4870.77 4902.29 4931.29 5122.94 5170.22 5205.99
    54.5   55.81   55.02   54.42   54.91   54.11    54.6   55.21   54.41   54.65
   56.51   56.71   55.91   54.71   53.64   54.01      53      52   50.23      50
   48.91   47.22    47.1   46.71   45.34    46.8      46   46.29   45.82   45.82
   45.83   45.83   45.93   45.93   45.95   45.95   46.18   46.18    46.2    46.2
   46.29   46.29    46.3    46.3   46.34   46.34    46.4   50.61   51.31   50.93
   52.09   52.92    54.3    56.3    55.1   54.06   54.01    54.7    56.2    55.7
       0       0       0       0       0       0       0       0       0       0
       0       0       0       0       0       0       0       0       0       0
       0       0       0       0       0       0       0   44.49   44.57   39.59
   39.59   42.29    42.3    32.3    32.3   38.37   38.39   32.45   32.45   42.37
   42.35   39.66   39.66   44.59   44.57       0       0       0       0       0
       0       0       0       0       0       0       0       0       0       0
 -371.47 -108.27  -45.23  254.21  490.62  514.26  526.86  679.74 1081.62 1113.14
 1160.43 1239.23 1381.07 2129.68 2184.84 2310.92 2678.13 2709.65 2733.29 2742.59
 2915.96 3066.31 3239.67 3279.23 3326.51 3357.87 3562.75  3792.5 3874.65 3874.66
 3876.63 3876.64 3901.72 3901.73 3905.66 3905.67    3965 3965.01 3968.94 3968.95
 3992.69  3992.7 3994.67 3994.68 4084.84 4084.94 4139.19 4323.03 4401.83 4410.42
 4449.11 4504.98 4528.62 4796.54 4870.77 4902.29 4931.29 5122.94 5170.22 5205.99
    54.5   55.81   55.02   54.42   54.91   54.11    54.6   55.21   54.41   54.65
   56.51   56.71   55.91   54.71   53.64   54.01      53      52   50.23      50
   48.91   47.22    47.1   46.71   45.34    46.8      46   46.29   45.82   45.82
   45.83   45.83   45.93   45.93   45.95   45.95   46.18   46.18    46.2    46.2
   46.29   46.29    46.3    46.3   46.34   46.34    46.4   50.61   51.31   50.93
   52.09   52.92    54.3    56.3    55.1   54.06   54.01    54.7    56.2    55.7
       0       0       0       0       0       0       0       0       0       0
       0       0       0       0       0       0       0       0       0       0
       0       0       0       0       0       0       0   44.49   44.57   39.59
   39.59   42.29    42.3    32.3    32.3   38.37   38.39   32.45   32.45   42.37
   42.35   39.66   39.66   44.59   44.57       0       0       0       0       0
       0       0       0       0       0       0       0       0       0       0
Pier Skew= 38
Pier Skew, UpSta & Num, DnSta & Num=  ,3796.68, 2 ,3796.68, 2 , 0 , 0 , 0 ,,
       5       5
      20      45
       5       5
      20      45
Pier Skew, UpSta & Num, DnSta & Num=  ,3811.33, 2 ,3811.33, 2 , 0 , 0 , 0 ,,
       5       5
      20      45
       5       5
      20      45
Pier Skew, UpSta & Num, DnSta & Num=  ,3817.56, 2 ,3817.56, 2 , 0 , 0 , 0 ,,
       5       5
      20      45
       5       5
      20      45
Pier Skew, UpSta & Num, DnSta & Num=  ,3829.85, 2 ,3829.85, 2 , 0 , 0 , 0 ,,
       5       5
      20      45
       5       5
      20      45
Pier Skew, UpSta & Num, DnSta & Num=  ,3838.91, 2 ,3838.91, 2 , 0 , 0 , 0 ,,
       5       5
    16.8   45.11
       5       5
    16.8   45.11
Pier Skew, UpSta & Num, DnSta & Num=  ,3849.39, 2 ,3849.39, 2 , 0 , 0 , 0 ,,
       5       5
    16.8   45.11
       5       5
    16.8   45.11
Pier Skew, UpSta & Num, DnSta & Num=  ,3864.52, 2 ,3864.52, 2 , 0 , 0 , 0 ,,
       4       4
      20      45
       4       4
      20      45
Pier Skew, UpSta & Num, DnSta & Num=  ,3873.43, 2 ,3873.43, 2 , 0 , 0 , 0 ,,
       5       5
      20      45
       5       5
      20      45
Pier Skew, UpSta & Num, DnSta & Num=  ,3875.64, 2 ,3875.64, 2 , 0 , 0 , 0 ,,
     4.5     4.5
      20      45
     4.5     4.5
      20      45
Pier Skew, UpSta & Num, DnSta & Num=  ,3903.69, 2 ,3903.69, 2 , 0 , 0 , 0 ,,
     4.5     4.5
   15.76   45.11
     4.5     4.5
   15.76   45.11
Pier Skew, UpSta & Num, DnSta & Num=  ,3966.97, 2 ,3966.97, 2 , 0 , 0 , 0 ,,
     4.5     4.5
    16.8   45.11
     4.5     4.5
    16.8   45.11
Pier Skew, UpSta & Num, DnSta & Num=  ,3993.68, 2 ,3993.68, 2 , 0 , 0 , 0 ,,
     4.5     4.5
    16.8   45.11
     4.5     4.5
    16.8   45.11
Pier Skew, UpSta & Num, DnSta & Num=  ,3996.87, 2 ,3996.87, 2 , 0 , 0 , 0 ,,
       4       4
   15.76   45.11
       4       4
   15.76   45.11
Pier Skew, UpSta & Num, DnSta & Num=  ,4000.06, 2 ,4000.06, 2 , 0 , 0 , 0 ,,
       4       4
    16.8   45.11
       4       4
    16.8   45.11
Pier Skew, UpSta & Num, DnSta & Num=  ,4009.75, 2 ,4009.75, 2 , 0 , 0 , 0 ,,
       6       6
    16.8   45.11
       6       6
    16.8   45.11
Pier Skew, UpSta & Num, DnSta & Num=  ,4020.47, 2 ,4020.47, 2 , 0 , 0 , 0 ,,
       5       5
    16.8   45.11
       5       5
    16.8   45.11
Pier Skew, UpSta & Num, DnSta & Num=  ,4030.72, 2 ,4030.72, 2 , 0 , 0 , 0 ,,
       4       4
    16.8   45.11
       4       4
    16.8   45.11
Pier Skew, UpSta & Num, DnSta & Num=  ,4039.46, 2 ,4039.46, 2 , 0 , 0 , 0 ,,
       6       6
    16.8   45.11
       6       6
    16.8   45.11
Pier Skew, UpSta & Num, DnSta & Num=  ,4051.6, 2 ,4051.6, 2 , 0 , 0 , 0 ,,
       6       6
   15.76   45.11
       6       6
   15.76   45.11
Pier Skew, UpSta & Num, DnSta & Num=  ,4062.47, 2 ,4062.47, 2 , 0 , 0 , 0 ,,
       6       6
   15.76   45.11
       6       6
   15.76   45.11
Pier Skew, UpSta & Num, DnSta & Num=  ,4072.8, 2 ,4072.8, 2 , 0 , 0 , 0 ,,
       4       4
   15.76   45.11
       4       4
   15.76   45.11
Pier Skew, UpSta & Num, DnSta & Num=  ,4082.09, 2 ,4082.09, 2 , 0 , 0 , 0 ,,
       5       5
   15.76   45.11
       5       5
   15.76   45.11
BR Coef= 1 , 1 , 0 ,1.25, 0 ,,,0.8,0,2,0,
WSPro=,,,, 1 ,,,, 0 ,,,, 0 ,,,,-1 ,-1 ,-1 , 0 , 0 , 0 , 0 , 0
BC Design=,, 0 ,, 0 ,,,,,,
BC HTab HWMax=56.72
BC Use User HTab Curves=0
BC User HTab FreeFlow(D)= 0

Type RM Length L Ch R = 1 ,18199.0 ,6.8,23,33
BEGIN DESCRIPTION:
Downstream Section of Bridge/Culvert/Weir
END DESCRIPTION:
XS GIS Cut Line= 6
      3112196.19     13852164.52      3111229.11     13848802.02
      3110700.74     13847325.39      3110715.12     13846982.45
      3110287.29      13846039.1      3110214.75     13845701.11
#Sta/Elev= 30
-162.488    55.61105.264   53.751160.425   56.451239.226   56.652129.678   54.65
2608.631   53.052742.593   49.953326.509   45.153507.751   46.253570.792   45.55
3602.312   42.953787.499   44.233822.869   40.883868.541   25.713894.665   23.43
3924.767    8.933940.921     6.73951.323       93977.643   23.334068.656   30.29
4103.741   41.654126.421    46.24139.105   46.274323.027   50.554401.829   51.25
 4425.47   49.154449.109   51.954590.951   54.255120.415   53.45 5189.76   56.05
#Mann= 5 ,-1 , 0
-162.488     .08       03787.499     .04       03894.665    .015       0
3977.643     .04       04139.105     .08       0
#XS Ineff= 3 ,-1
 2560.143464.602      50 3786.53 3787.27   42.43 4084.84 5189.76   42.43
Permanent Ineff=
       F       F       F
Bank Sta=3787.499,4139.105
XS Rating Curve= 0 ,0
Skew Angle= 38
Exp/Cntr=0.5,0.3

Type RM Length L Ch R = 1 ,18176.0 ,95,94,74.6
BEGIN DESCRIPTION:
Upstream Section of Bridge/Culvert/Weir
END DESCRIPTION:
XS GIS Cut Line= 6
       3112451.7     13852433.82      3111218.27     13848509.95
       3110712.6     13847358.55      3110750.79     13846673.03
      3110517.54     13845983.48      3110462.24     13845678.55
#Sta/Elev= 30
 -439.71   55.58 576.588   53.281585.241   55.982625.416   52.982895.861   47.88
3124.384   45.783187.425   46.983289.866   44.683329.267   46.883423.828   46.28
3486.869   48.283534.149   46.58 3565.67   42.683827.526   41.643850.221    41.3
3872.285   29.293885.287   24.333903.017   23.563926.579    9.153941.471    6.79
3955.578    8.933987.098   23.444036.743   27.914099.311   43.824333.271   44.58
4451.473   50.785048.785   55.735072.347   53.085119.626   55.585151.305   54.38
#Mann= 6 ,-1 , 0
 -439.71     .08       03827.526     .04       03903.017    .015       0
3987.098     .04       04099.311     .08       05048.785     .99       0
#XS Ineff= 3 ,-1
 2752.58 3488.66   49.94 3492.97 3825.81    43.44118.6175151.069      43
Permanent Ineff=
       F       F       F
Bank Sta=3850.221,4099.311
XS Rating Curve= 0 ,0
Skew Angle= 38
Exp/Cntr=0.5,0.3

Type RM Length L Ch R = 3 ,18138.0 ,,,
BEGIN DESCRIPTION:
YALE ROAD
Structure ID: E100-00-00-17
Bridge has a 38 degree skew with the channel.
END DESCRIPTION:
Bridge Culvert--1,0,-1,-1, 0
Deck Dist Width WeirC Skew NumUp NumDn MinLoCord MaxHiCord MaxSubmerge Is_Ogee
10,56,2.6,38, 194, 194, , , 0.95, 0, ,,,
-452.397-439.946-381.476-365.716-321.745-305.985-192.353-132.622-108.982-101.102
 -58.392 -42.631 166.822 221.983 225.292 241.052 300.784 332.304 375.014 398.655
 414.415 430.175 434.746 461.696 466.266 474.146 501.096 516.856 576.588 579.897
 698.099 713.859 718.429  765.71   816.3 820.871 852.391 915.432 934.502 966.022
 994.2331017.8731025.7541112.4351115.7451167.5961191.2361206.9961246.3971352.148
1375.7881423.0691470.349 1549.151572.7911585.2411651.5921695.5631722.5131982.556
1987.1272084.9982100.7582148.0392534.1642557.8042573.5642578.1352586.0152625.416
2636.6052668.1252672.6962688.4562801.299 2864.342895.8612917.3742933.1343106.496
3124.3843145.8963177.4173187.4253193.1773216.8183242.5853256.2183271.9793281.986
3289.8663295.6193329.2673342.899 3390.183392.3083423.8283453.2213468.9813476.861
3484.7413486.8693516.2623534.1493539.902 3557.79 3565.673675.0463778.4333792.223
3814.9963827.5263850.2213860.6153860.7013860.7883861.5683863.8613863.9323872.285
3885.2873898.2893903.0173926.5793933.1983933.8293936.5083941.4723943.2853946.279
3948.7223955.5783960.7783987.0984010.2664030.4394036.7434056.7584066.9244067.002
4072.2034075.9864087.4044087.4914087.5774099.3114118.5314118.6174119.405 4135.56
4163.6134200.7284217.7494260.9324265.0294274.958 4312.31 4328.074333.2714356.912
4364.7924388.3534435.7134451.4734475.1134506.6344514.5144522.3154522.3944545.955
4569.6744585.4354656.3554806.0784821.8384829.7184853.3584900.6394906.8644979.361
4995.1225010.8825018.7625026.6425034.5225040.8265048.7855056.5865064.4665072.347
5080.2275095.9875119.6275151.069
    55.2   55.61   55.21   55.11   54.81   54.63   54.73   55.01   54.51   54.16
   54.12    54.6   54.71   55.21   55.16   54.92   54.16   54.51   54.22   54.06
   53.95   53.84   53.92    54.6   54.57   54.51    54.3    54.6   53.84    53.8
   54.59   54.76   54.81   54.11   54.39   54.41   54.09   54.71   54.47   54.07
   54.36   54.66   54.76   56.01      56   55.81   55.81   56.11   55.61   55.73
   55.76   55.82   55.87    56.1      56   56.01   55.05   54.41   54.39    54.6
   54.58    54.1   53.77    53.9    52.4   51.99    52.1   52.12   52.41   53.01
   52.77   52.11   52.01   50.93   50.41   49.21   48.18    47.9   47.57    46.4
   45.86   46.22   46.82   47.01   46.96   46.74   46.51   45.92   45.24   45.32
   45.89    46.3   46.94    47.2    47.2   47.21   47.11    47.3      49    49.4
    49.3   49.09   47.25   46.61   45.81   43.31    42.7   43.13    42.8   42.76
   42.69   42.65   42.57   42.54   45.74   45.74   45.75   45.76   45.76   45.83
   45.92   46.02   46.06   46.23   46.28   46.29   46.31   46.35   46.36   46.38
    46.4   46.45   46.49   46.41   46.34   46.28   46.26    46.2   46.16   46.16
   46.15   46.15   46.16   46.16   42.96   43.85   44.28   44.28    44.3   44.41
   44.61   44.34   44.21   43.57   43.51   43.78   44.81   44.51   44.61   46.31
   46.31   47.71   50.51   50.81   50.21   51.01   50.81    51.3   51.31   51.61
   51.91   51.71   52.91   53.81   53.85   53.94   54.22   54.77   54.85    55.7
   55.46   55.69    55.8   55.91   56.02   56.11      56    55.4    53.6    53.1
      54    54.3    55.6    54.4
                                                                                
                                                                                
                                                                                
                                                                                
                                                                                
                                                                                
                                                                                
                                                                                
                                                                                
                                                                                
                                                                                
                                                                   35.56   35.63
   35.72   35.82   35.86   36.03   36.08   36.09   36.11   36.15   36.16   36.18
    36.2   36.25   36.29   36.21   36.14   36.08   36.06      36      36
                                                                                
                                                                                
                                                                                
                                                                                
                                                                                
                                
-452.397-439.946-381.476-365.716-321.745-305.985-192.353-132.622-108.982-101.102
 -58.392 -42.631 166.822 221.983 225.292 241.052 300.784 332.304 375.014 398.655
 414.415 430.175 434.746 461.696 466.266 474.146 501.096 516.856 576.588 579.897
 698.099 713.859 718.429  765.71   816.3 820.871 852.391 915.432 934.502 966.022
 994.2331017.8731025.7541112.4351115.7451167.5961191.2361206.9961246.3971352.148
1375.7881423.0691470.349 1549.151572.7911585.2411651.5921695.5631722.5131982.556
1987.1272084.9982100.7582148.0392534.1642557.8042573.5642578.1352586.0152625.416
2636.6052668.1252672.6962688.4562801.299 2864.342895.8612917.3742933.1343106.496
3124.3843145.8963177.4173187.4253193.1773216.8183242.5853256.2183271.9793281.986
3289.8663295.6193329.2673342.899 3390.183392.3083423.8283453.2213468.9813476.861
3484.7413486.8693516.2623534.1493539.902 3557.79 3565.673675.0463778.4333792.223
3814.9963827.5263850.2213860.6153860.7013860.7883861.5683863.8613863.9323872.285
3885.2873898.2893903.0173926.5793933.1983933.8293936.5083941.4723943.2853946.279
3948.7223955.5783960.7783987.0984010.2664030.4394036.7434056.7584066.9244067.002
4072.2034075.9864087.4044087.4914087.5774099.3114118.5314118.6174119.405 4135.56
4163.6134200.7284217.7494260.9324265.0294274.958 4312.31 4328.074333.2714356.912
4364.7924388.3534435.7134451.4734475.1134506.6344514.5144522.3154522.3944545.955
4569.6744585.4354656.3554806.0784821.8384829.7184853.3584900.6394906.8644979.361
4995.1225010.8825018.7625026.6425034.5225040.8265048.7855056.5865064.4665072.347
5080.2275095.9875119.6275151.069
    55.2   55.61   55.21   55.11   54.81   54.63   54.73   55.01   54.51   54.16
   54.12    54.6   54.71   55.21   55.16   54.92   54.16   54.51   54.22   54.06
   53.95   53.84   53.92    54.6   54.57   54.51    54.3    54.6   53.84    53.8
   54.59   54.76   54.81   54.11   54.39   54.41   54.09   54.71   54.47   54.07
   54.36   54.66   54.76   56.01      56   55.81   55.81   56.11   55.61   55.73
   55.76   55.82   55.87    56.1      56   56.01   55.05   54.41   54.39    54.6
   54.58    54.1   53.77    53.9    52.4   51.99    52.1   52.12   52.41   53.01
   52.77   52.11   52.01   50.93   50.41   49.21   48.18    47.9   47.57    46.4
   45.86   46.22   46.82   47.01   46.96   46.74   46.51   45.92   45.24   45.32
   45.89    46.3   46.94    47.2    47.2   47.21   47.11    47.3      49    49.4
    49.3   49.09   47.25   46.61   45.81   43.31    42.7   43.13    42.8   42.76
   42.69   42.65   42.57   42.54   45.74   45.74   45.75   45.76   45.76   45.83
   45.92   46.02   46.06   46.23   46.28   46.29   46.31   46.35   46.36   46.38
    46.4   46.45   46.49   46.41   46.34   46.28   46.26    46.2   46.16   46.16
   46.15   46.15   46.16   46.16   42.96   43.85   44.28   44.28    44.3   44.41
   44.61   44.34   44.21   43.57   43.51   43.78   44.81   44.51   44.61   46.31
   46.31   47.71   50.51   50.81   50.21   51.01   50.81    51.3   51.31   51.61
   51.91   51.71   52.91   53.81   53.85   53.94   54.22   54.77   54.85    55.7
   55.46   55.69    55.8   55.91   56.02   56.11      56    55.4    53.6    53.1
      54    54.3    55.6    54.4
                                                                                
                                                                                
                                                                                
                                                                                
                                                                                
                                                                                
                                                                                
                                                                                
                                                                                
                                                                                
                                                                                
                                                                   35.56   35.63
   35.72   35.82   35.86   36.03   36.08   36.09   36.11   36.15   36.16   36.18
    36.2   36.25   36.29   36.21   36.14   36.08   36.06      36      36
                                                                                
                                                                                
                                                                                
                                                                                
                                                                                
                                
Pier Skew, UpSta & Num, DnSta & Num=  ,3898.289, 2 ,3898.289, 2 , 0 , 0 , 0 ,,
       3       3
   22.75   36.83
       3       3
   22.81   36.89
Pier Skew, UpSta & Num, DnSta & Num=  ,3932.883, 2 ,3932.883, 2 , 0 , 0 , 0 ,,
     3.5     3.5
     7.5   37.09
     3.5     3.5
    7.56   37.15
Pier Skew, UpSta & Num, DnSta & Num=  ,3976.145, 2 ,3976.145, 2 , 0 , 0 , 0 ,,
     3.5     3.5
   16.78   37.25
     3.5     3.5
   16.84   37.31
Pier Skew, UpSta & Num, DnSta & Num=  ,4010.739, 2 ,4010.739, 2 , 0 , 0 , 0 ,,
     1.5     1.5
   24.38   37.14
     1.5     1.5
   24.44    37.2
Pier Skew, UpSta & Num, DnSta & Num=  ,4036.743, 2 ,4036.743, 2 , 0 , 0 , 0 ,,
       3       3
    26.9   37.06
       3       3
   26.96   37.12
BR Coef= 1 , 1 , 0 ,1.25, 0 ,,,0.8,-1,2,0,
WSPro=,,,, 1 ,,,, 0 ,,,, 0 ,,,,-1 ,-1 ,-1 , 0 , 0 , 0 , 0 , 0
BC Design=,, 0 ,, 0 ,,,,,,
BC HTab HWMax=56.08
BC Use User HTab Curves=0
BC User HTab FreeFlow(D)= 0