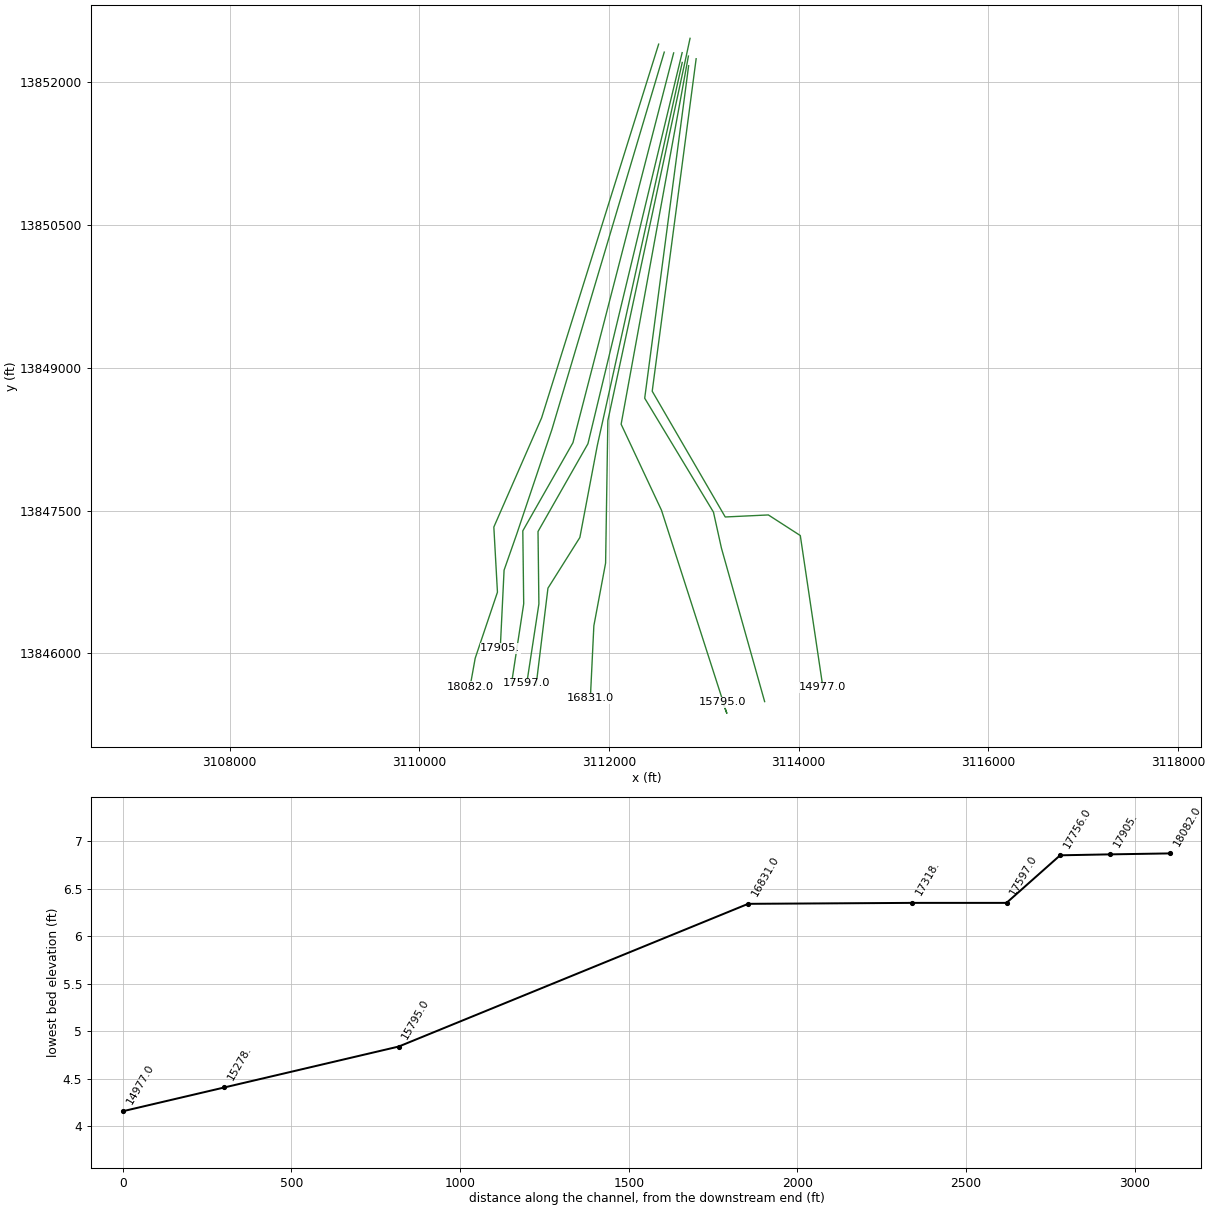
HEC-RAS study E100-00-00.prj: E100-00-00

--- E100-00-00.g02 (geometry) --- (continued)

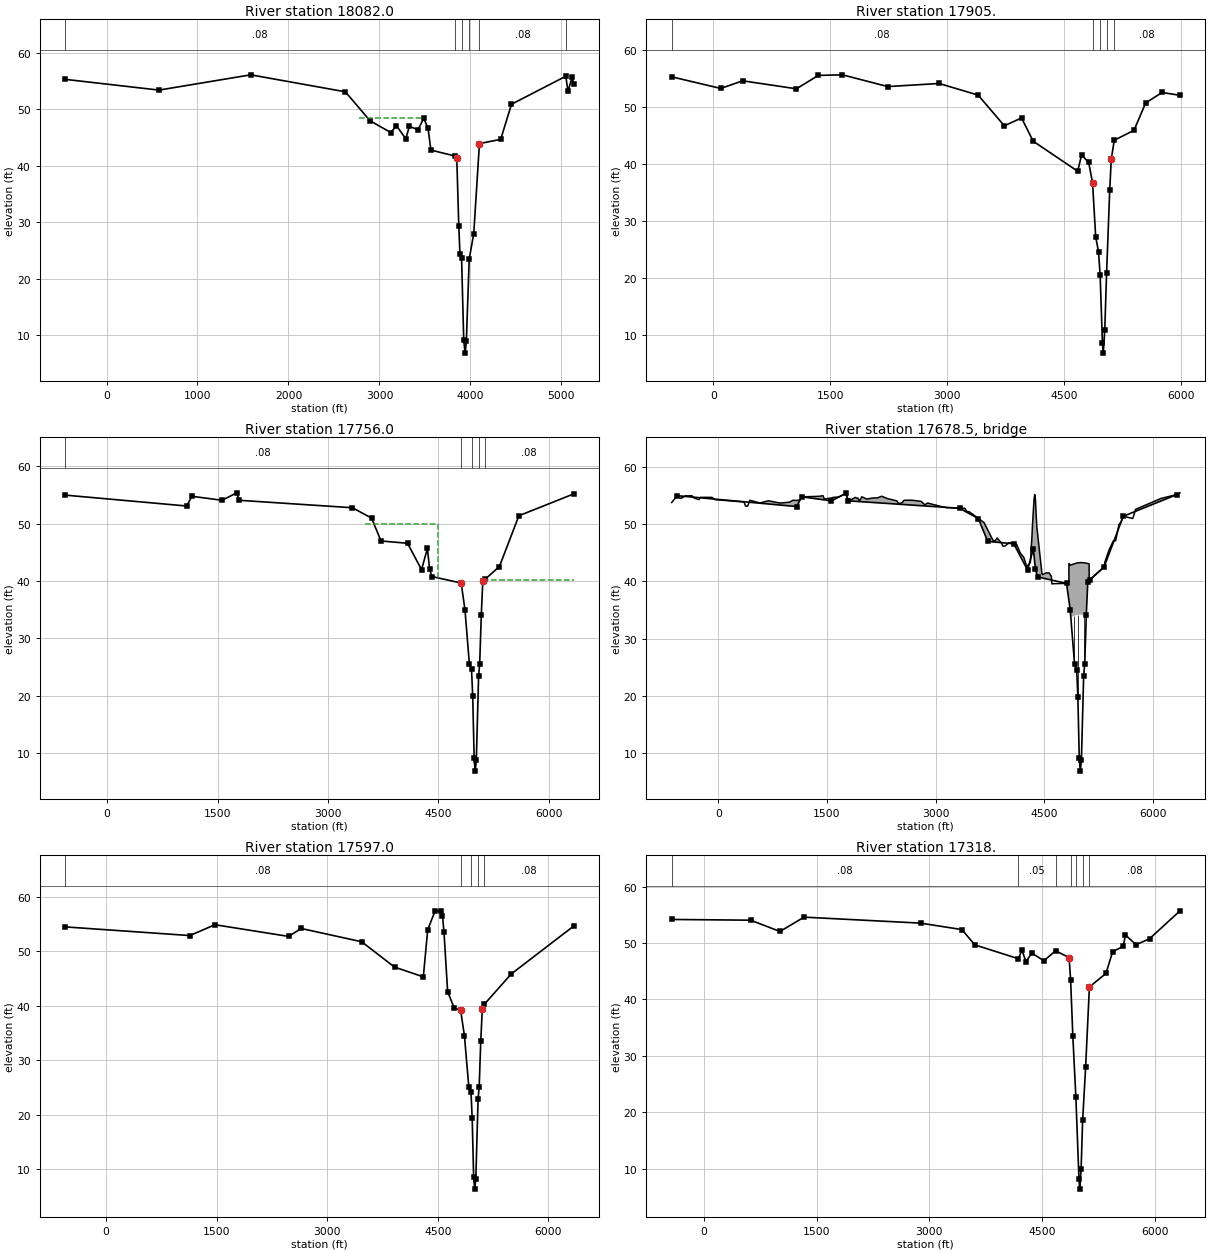
Type RM Length L Ch R = 1 ,18082.0 ,257.1,177,101.8
BEGIN DESCRIPTION:
Downstream Section of Bridge/Culvert/Weir
END DESCRIPTION:
XS GIS Cut Line= 6
      3112523.55     13852399.76      3111289.62     13848474.33
      3110786.18       13847328.      3110824.29     13846643.85
      3110589.89      13845950.9      3110534.99     13845648.14
#Sta/Elev= 30
-454.209   55.26 576.588   53.361585.241   56.062625.416   53.062895.861   47.96
3124.384   45.863187.425   47.063289.866   44.763329.267   46.963423.828   46.36
3486.869   48.363534.149   46.66 3565.67   42.763827.526   41.723850.221   41.38
3872.285   29.373885.287   24.413903.017   23.643926.579    9.233941.471    6.87
3955.578    9.013987.098   23.524036.743   27.994099.311    43.94333.271   44.66
4451.473   50.865048.785   55.815072.347   53.165119.626   55.665133.732   54.46
#Mann= 6 ,-1 , 0
-454.209     .08       03827.526     .04       03903.017    .015       0
3987.098     .04       04099.311     .08       05048.785     .99       0
#XS Ineff= 3 ,-1
 2774.95  3487.3   48.354118.6175133.732    39.5 3500.28 3828.63   39.33
Permanent Ineff=
       F       F       F
Bank Sta=3850.221,4099.311
XS Rating Curve= 0 ,0
Skew Angle= 38
Exp/Cntr=0.5,0.3

Type RM Length L Ch R = 1 ,17905.  ,91,149,193
BEGIN DESCRIPTION:
Heights Blvd. - U/S - XS 4
END DESCRIPTION:
XS GIS Cut Line= 5
      3112582.56     13852315.97      3111398.66     13848353.46
       3111027.3     13847253.41      3110894.18     13846875.04
      3110853.98     13846056.06
#Sta/Elev= 30
  -535.2   55.33    94.8   53.29   374.8   54.63  1064.8   53.23  1344.8   55.58
  1654.8   55.68  2234.8   53.62  2894.8   54.16  3394.8   52.12  3730.4   46.73
  3950.4   48.12  4100.4   44.03  4670.4   38.77  4720.4    41.6  4811.4   40.34
  4861.4   36.72  4901.4   27.27 4937.98   24.62 4958.57   20.49 4987.77    8.71
 4998.52    6.86 5017.73   10.88  5041.4   20.99  5081.4   35.44  5101.4   40.92
    5140   44.21  5392.5   45.94  5542.5   50.75  5752.5   52.58  5982.5   52.09
#Mann= 5 ,-1 , 0
  -535.2     .08       0  4861.4     .04       0 4958.57    .015       0
  5041.4     .04       0    5140     .08       0
Bank Sta=4861.4,5101.4
XS Rating Curve= 0 ,0
Exp/Cntr=0.5,0.3

Type RM Length L Ch R = 1 ,17756.0 ,176.4,159,158
BEGIN DESCRIPTION:
Upstream Section of Bridge/Culvert/Weir
END DESCRIPTION:
XS GIS Cut Line= 5
      3112681.61     13852307.48      3111619.95     13848213.57
      3111091.61     13847288.11      3111100.96     13846521.74
      3110973.32     13845689.32
#Sta/Elev= 30
    -569      55  1080.9    53.1  1150.9    54.8  1560.9    54.1  1760.9    55.4
  1790.9    54.1  3330.9    52.8  3590.9      51  3720.2      47  4080.2    46.6
  4270.2      42  4350.2    45.7  4380.2    42.1  4410.2    40.8    4809   39.66
  4860.1      35  4919.6   25.61  4949.3   24.59  4965.4   19.87  4984.9     9.1
    4999    6.85  5014.5    8.78  5045.5   23.48  5060.2    25.6  5081.8   34.12
  5102.6   39.98  5130.3   40.29  5327.9   42.54  5592.3    51.4  6334.6    55.2
#Mann= 5 ,-1 , 0
    -569     .08       0    4809     .04       0  4949.3    .015       0
  5045.5     .04       0  5130.3     .08       0
#XS Ineff= 3 ,-1
 3507.82 4497.29   49.96 5113.41  6334.6   40.12 4547.39 4785.36   39.46
Permanent Ineff=
       F       F       F
Bank Sta=4809,5102.6
XS Rating Curve= 0 ,0
Exp/Cntr=0.5,0.3

Type RM Length L Ch R = 3 ,17678.5 ,,,
BEGIN DESCRIPTION:
S. HEIGHTS
Structure ID: E100-00-00-16
END DESCRIPTION:
Bridge Culvert--1,0,-1,-1, 0
Deck Dist Width WeirC Skew NumUp NumDn MinLoCord MaxHiCord MaxSubmerge Is_Ogee
10,135,2.6,0, 199, 199, , , 0.95, 0, ,,,
  -645.8  -615.8  -569.1  -519.1  -515.8  -449.1  -435.8  -365.8  -339.1  -325.8
  -269.1  -249.1  -135.8   -89.1   -49.1   200.9   290.9   354.2   374.2   380.9
   404.2   434.2   574.2   690.9   850.9   980.9  1030.9  1080.9  1130.9  1150.9
  1164.2  1390.9  1410.9  1444.2  1464.2  1510.9  1560.9  1584.2  1664.2  1754.2
  1760.9  1774.2  1790.9  1804.2  1824.2  1840.9  1890.9  1910.9  1924.2  1930.9
  1934.2  1940.9  1944.2  1950.9  1974.2  1980.9  1984.2  2050.9  2134.2  2194.2
  2254.2  2260.9  2334.2  2460.9  2464.2  2484.2  2490.9  2504.2  2534.2  2564.2
  2670.9  2800.9  2850.9  2890.9  2924.2  3014.2  3044.2  3064.2  3154.2  3170.9
  3190.9  3330.9  3404.2  3434.2  3464.2  3500.9  3590.9  3610.9  3650.9  3660.2
  3669.2  3720.2  3789.2  3790.2  3819.2  3850.2  3909.2  3910.2  3929.2  3930.2
  3959.2  4019.2  4080.2  4119.2  4169.2  4219.2  4259.2  4270.2  4300.2  4309.2
  4320.2  4329.2  4330.2  4339.2  4340.2  4350.2  4359.2  4360.2  4369.2  4379.2
  4380.2  4389.2  4399.2  4410.2  4469.2  4479.2  4509.2  4530.2  4569.2  4599.2
    4607  4607.1  4640.6  4721.1    4786    4809 4841.69  4841.8 4841.91  4860.1
  4861.7 4869.31  4869.4  4891.7  4919.6  4946.6  4949.3  4956.9  4965.4  4984.9
  4991.6  4993.3  4997.9    4999  5002.1  5003.7  5006.6    5008  5014.5  5045.5
  5049.8  5057.5  5060.2  5081.8 5100.99  5101.1  5102.6 5120.89    5121 5121.11
  5121.5  5121.9  5130.3  5176.3  5232.6  5281.1  5327.8  5327.9  5341.3  5395.9
  5431.3  5455.9  5485.9  5492.3  5532.3  5558.5  5562.3  5592.3  5718.5  5722.3
  5732.3  5758.5  5762.3  6112.3  6168.5  6308.5  6318.5  6334.5  6376.4
    53.8   54.28   55.01   54.51   54.53   55.01   54.96      55   54.61   54.55
   54.31   54.71   54.71   54.71   54.31   54.06   53.96    53.9    53.2   53.16
   53.19    54.2   53.73   54.11   53.71   53.87   54.21   54.16    54.3   54.81
    54.8   54.89   54.93      55   54.42   54.51    54.6    54.7   54.78   55.37
   55.41   54.83   54.32    54.5    54.3   54.35   54.71   54.56    54.6   54.51
   54.38   54.11   54.11   54.11   54.65   54.81   54.79   54.41    54.6   54.61
    54.9   54.87    54.5   54.11    54.1   53.72   53.61   53.65   53.75    54.2
   54.21   54.01   53.41   53.71    53.6   53.31   53.22   53.15    52.9   52.89
   52.89   52.83    52.8    52.2    52.2   51.86   51.03   50.84   50.47   50.38
    50.3   49.03    47.3   47.26   47.04   47.61   46.73   46.71    46.2   46.19
   46.21    46.8   46.62    46.5      45    44.2    42.6   42.75   43.17    43.3
   45.56    47.4   47.66      50   50.22   52.37    54.3   54.39    55.2    54.4
   54.13    51.7    49.5   48.23    41.4   41.21   41.39   41.51    41.5    40.9
   39.58   39.58   39.62   39.64   39.66   39.67   40.05   43.15   43.15   42.88
   42.86   42.89   42.89   42.99   43.11   43.23   43.23   43.25   43.26   43.29
    43.3    43.3   43.31   43.31   43.32   43.32   43.32   43.32   43.31   43.27
   43.27   43.26   43.25   43.19   43.14   43.14   43.14   43.09   43.09    40.2
    40.2   40.21    40.3   40.83   41.47   42.02   42.54   42.55    43.5   45.51
   46.45   47.11   47.11   47.41   49.91   50.35   50.41   51.41   51.02   51.01
   51.31   52.45   52.61   54.51   54.69   55.13   55.16   55.21    55.5
                                                                                
                                                                                
                                                                                
                                                                                
                                                                                
                                                                                
                                                                                
                                                                                
                                                                                
                                                                                
                                                                                
                                                                                
                                                                                
                                                                                
                   33.79   33.89   34.01   34.13   34.13   34.15   34.16   34.19
    34.2    34.2   34.21   34.21   34.22   34.22   34.22   34.22   34.21   34.17
   34.17   34.16   34.15   34.12
                                                                                
                                                                                
                                                                        
  -645.8  -615.8  -569.1  -519.1  -515.8  -449.1  -435.8  -365.8  -339.1  -325.8
  -269.1  -249.1  -135.8   -89.1   -49.1   200.9   290.9   354.2   374.2   380.9
   404.2   434.2   574.2   690.9   850.9   980.9  1030.9  1080.9  1130.9  1150.9
  1164.2  1390.9  1410.9  1444.2  1464.2  1510.9  1560.9  1584.2  1664.2  1754.2
  1760.9  1774.2  1790.9  1804.2  1824.2  1840.9  1890.9  1910.9  1924.2  1930.9
  1934.2  1940.9  1944.2  1950.9  1974.2  1980.9  1984.2  2050.9  2134.2  2194.2
  2254.2  2260.9  2334.2  2460.9  2464.2  2484.2  2490.9  2504.2  2534.2  2564.2
  2670.9  2800.9  2850.9  2890.9  2924.2  3014.2  3044.2  3064.2  3154.2  3170.9
  3190.9  3330.9  3404.2  3434.2  3464.2  3500.9  3590.9  3610.9  3650.9  3660.2
  3669.2  3720.2  3789.2  3790.2  3819.2  3850.2  3909.2  3910.2  3929.2  3930.2
  3959.2  4019.2  4080.2  4119.2  4169.2  4219.2  4259.2  4270.2  4300.2  4309.2
  4320.2  4329.2  4330.2  4339.2  4340.2  4350.2  4359.2  4360.2  4369.2  4379.2
  4380.2  4389.2  4399.2  4410.2  4469.2  4479.2  4509.2  4530.2  4569.2  4599.2
    4607  4607.1  4640.6  4721.1    4786    4809 4841.69  4841.8 4841.91  4860.1
  4861.7 4869.31  4869.4  4891.7  4919.6  4946.6  4949.3  4956.9  4965.4  4984.9
  4991.6  4993.3  4997.9    4999  5002.1  5003.7  5006.6    5008  5014.5  5045.5
  5049.8  5057.5  5060.2  5081.8 5100.99  5101.1  5102.6 5120.89    5121 5121.11
  5121.5  5121.9  5130.3  5176.3  5232.6  5281.1  5327.8  5327.9  5341.3  5395.9
  5431.3  5455.9  5485.9  5492.3  5532.3  5558.5  5562.3  5592.3  5718.5  5722.3
  5732.3  5758.5  5762.3  6112.3  6168.5  6308.5  6318.5  6334.5  6376.4
    53.8   54.28   55.01   54.51   54.53   55.01   54.96      55   54.61   54.55
   54.31   54.71   54.71   54.71   54.31   54.06   53.96    53.9    53.2   53.16
   53.19    54.2   53.73   54.11   53.71   53.87   54.21   54.16    54.3   54.81
    54.8   54.89   54.93      55   54.42   54.51    54.6    54.7   54.78   55.37
   55.41   54.83   54.32    54.5    54.3   54.35   54.71   54.56    54.6   54.51
   54.38   54.11   54.11   54.11   54.65   54.81   54.79   54.41    54.6   54.61
    54.9   54.87    54.5   54.11    54.1   53.72   53.61   53.65   53.75    54.2
   54.21   54.01   53.41   53.71    53.6   53.31   53.22   53.15    52.9   52.89
   52.89   52.83    52.8    52.2    52.2   51.86   51.03   50.84   50.47   50.38
    50.3   49.03    47.3   47.26   47.04   47.61   46.73   46.71    46.2   46.19
   46.21    46.8   46.62    46.5      45    44.2    42.6   42.75   43.17    43.3
   45.56    47.4   47.66      50   50.22   52.37    54.3   54.39    55.2    54.4
   54.13    51.7    49.5   48.23    41.4   41.21   41.39   41.51    41.5    40.9
   39.58   39.58   39.62   39.64   39.66   39.67   40.05   43.15   43.15   42.88
   42.86   42.89   42.89   42.99   43.11   43.23   43.23   43.25   43.26   43.29
    43.3    43.3   43.31   43.31   43.32   43.32   43.32   43.32   43.31   43.27
   43.27   43.26   43.25   43.19   43.14   43.14   43.14   43.09   43.09    40.2
    40.2   40.21    40.3   40.83   41.47   42.02   42.54   42.55    43.5   45.51
   46.45   47.11   47.11   47.41   49.91   50.35   50.41   51.41   51.02   51.01
   51.31   52.45   52.61   54.51   54.69   55.13   55.16   55.21    55.5
                                                                                
                                                                                
                                                                                
                                                                                
                                                                                
                                                                                
                                                                                
                                                                                
                                                                                
                                                                                
                                                                                
                                                                                
                                                                                
                                                                                
                   33.79   33.89   34.01   34.13   34.13   34.15   34.16   34.19
    34.2    34.2   34.21   34.21   34.22   34.22   34.22   34.22   34.21   34.17
   34.17   34.16   34.15   34.12
                                                                                
                                                                                
                                                                        
Pier Skew, UpSta & Num, DnSta & Num=  ,4913.3, 2 ,4913.3, 2 , 0 , 0 , 0 ,,
       3       3
   25.41   34.99
       3       3
   24.91   34.49
Pier Skew, UpSta & Num, DnSta & Num=  ,4965.4, 2 ,4965.4, 2 , 0 , 0 , 0 ,,
       3       3
   18.04   35.16
       3       3
   17.54   34.66
Pier Skew, UpSta & Num, DnSta & Num=  ,5049.8, 2 ,5049.8, 2 , 0 , 0 , 0 ,,
       3       3
   22.67   35.17
       3       3
   22.17   34.67
BR Coef= 1 , 1 , 0 ,1.25, 0 ,,,0.8,0,1.2,0,
WSPro=,,,, 1 ,,,, 0 ,,,, 0 ,,,,-1 ,-1 ,-1 , 0 , 0 , 0 , 0 , 0
BC Design=,, 0 ,, 0 ,,,,,,
BC HTab HWMax=55.5
BC Use User HTab Curves=0
BC User HTab FreeFlow(D)= 0

Type RM Length L Ch R = 1 ,17597.0 ,317.4,279,194.7
BEGIN DESCRIPTION:
Downstream Section of Bridge/Culvert/Weir
END DESCRIPTION:
XS GIS Cut Line= 5
      3112771.18     13852310.21      3111778.13     13848202.82
      3111251.85     13847280.97      3111261.13     13846520.28
      3111133.12     13845685.42
#Sta/Elev= 30
  -553.1   54.49  1136.9    52.9  1476.9   54.89  2476.9   52.74  2646.9    54.2
  3466.9   51.76  3912.6   47.11  4302.6   45.32  4362.6   53.99  4462.6   57.44
  4542.6   57.33  4562.6   56.57  4582.6   53.56  4632.6   42.59  4721.1   39.63
    4809   39.16  4860.1    34.5  4919.6   25.11  4949.3   24.09  4965.4   19.37
  4984.9     8.6    4999    6.35  5014.5    8.28  5045.5   22.98  5060.2    25.1
  5081.8   33.62  5102.6   39.48  5130.3   40.29  5494.1   45.84  6339.5   54.62
#Mann= 5 ,-1 , 0
  -553.1     .08       0    4809     .04       0  4949.3    .015       0
  5045.5     .04       0  5130.3     .08       0
#XS Ineff= 3 ,-1
  -553.1 4506.07   50.02 4784.92 4785.15   37.94  5134.5  6339.5   37.57
Permanent Ineff=
       F       F       F
Bank Sta=4809,5102.6
XS Rating Curve= 0 ,0
Exp/Cntr=0.5,0.3

Type RM Length L Ch R = 1 ,17318.  ,432.6,487,533.6
BEGIN DESCRIPTION:
Heights Blvd. - D/S - XS 1
END DESCRIPTION:
XS GIS Cut Line= 5
      3112771.97     13852207.14      3111877.18     13848185.84
      3111692.94     13847218.37      3111356.62     13846685.86
      3111232.17     13845668.44
#Sta/Elev= 30
  -426.2   54.16   623.8   54.03  1013.8   52.03  1333.8   54.57  2883.8   53.51
  3433.8   52.36  3603.8   49.66  4183.4    47.2  4233.4   48.73  4283.4   46.66
  4363.4    48.2  4523.4   46.83  4678.3   48.61  4858.3    47.4  4878.3    43.5
  4908.3   33.44  4948.3   22.67 4989.64    8.16 4999.51    6.35 5018.29    9.97
  5038.3   18.52  5078.3   27.98  5128.3    42.2  5348.1   44.58  5438.1   48.47
  5578.1   49.38  5608.1   51.41  5748.1   49.68  5928.1   50.74  6333.1   55.69
#Mann= 7 ,-1 , 0
  -426.2     .08       0  4183.4     .05       0  4678.3     .08       0
  4878.3     .04       0  4948.3    .015       0  5038.3     .04       0
  5128.3     .08       0
Bank Sta=4858.3,5128.3
XS Rating Curve= 0 ,0
Exp/Cntr=0.3,0.1

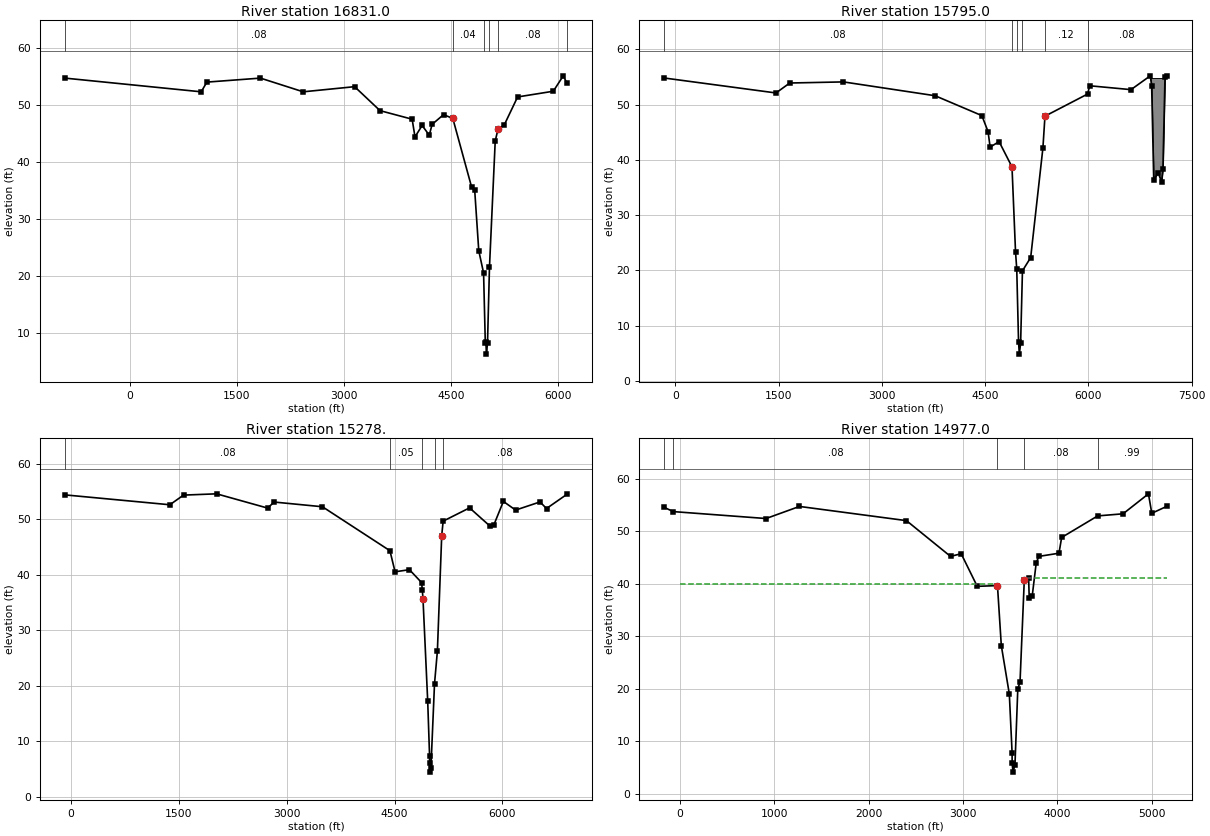
Type RM Length L Ch R = 1 ,16831.0 ,876.9,1036,1037
BEGIN DESCRIPTION:
Cross Section E100-00-00-X11
Located At: DS S.HEIGHTS
END DESCRIPTION:
XS GIS Cut Line= 5
      3112854.49     13852460.71      3111988.15     13848446.75
       3111964.3     13846949.62      3111840.47     13846290.42
      3111803.64     13845529.46
#Sta/Elev= 30
  -907.4    54.7  1002.6    52.3  1082.6      54  1832.6    54.7  2432.6    52.3
  3152.6    53.2    3509      49    3959    47.5    3999    44.4    4099    46.4
    4199    44.7    4239    46.6    4399    48.3    4529   47.64  4793.2   35.57
  4835.5   35.12  4892.7   24.46  4960.2   20.56  4984.5    8.24  4992.5    8.39
  5000.4    6.34  5015.4    8.33  5042.8   21.57  5123.3   43.67  5164.2   45.85
  5246.3    46.4    5437    51.4    5937    52.4    6077    55.1  6128.9    53.8
#Mann= 6 ,-1 , 0
  -907.4     .08       0    4529     .04       0  4960.2    .015       0
  5042.8     .04       0  5164.2     .08       0  6128.9     .99       0
#XS Ineff= 2 , 0
       0    4529   47.64  5164.2       0   45.85
Permanent Ineff=
       F       F
Bank Sta=4529,5164.2
XS Rating Curve= 0 ,0
Exp/Cntr=0.3,0.1

Type RM Length L Ch R = 1 ,15795.0 ,518,517,497.2
BEGIN DESCRIPTION:
Cross Section E100-00-00-X10
Located At: 2ND DS S. HEIGHTS
END DESCRIPTION:
XS GIS Cut Line= 6
      3112837.11     13852274.66      3112127.97     13848407.88
      3112553.44     13847504.41      3112691.09     13847077.96
      3113242.44       13845371.      3113198.79     13845485.86
#Sta/Elev= 30
  -159.4    54.8  1460.6    52.1  1660.6    53.9  2440.6    54.1  3771.9    51.6
  4451.9      48  4541.9    45.1  4571.9    42.3  4701.9    43.3  4889.6   38.72
  4940.8   23.36  4958.6   20.23  4984.8    7.02  4996.4    4.84  5014.9    6.85
  5041.5   19.92  5160.9   22.31  5338.6   42.13  5368.6    47.9  5987.2    51.9
  6018.6    53.4  6618.6    52.7  6898.6    55.2  6918.6    53.4  6948.6    36.4
  7012.4    37.7  7062.4      36  7082.4    38.4  7112.4    54.9  7135.3    55.1
#Mann= 6 ,-1 , 0
  -159.4     .08       0  4889.6     .04       0  4958.6    .015       0
  5041.5     .04       0  5368.6     .12       0  5987.2     .08       0
#Block Obstruct= 1 ,-1
  6891.7 7190.39   54.81
Bank Sta=4889.6,5368.6
XS Rating Curve= 0 ,0
Exp/Cntr=0.3,0.1

Type RM Length L Ch R = 1 ,15278.  ,90.9,301,461.8
BEGIN DESCRIPTION:
I-10 EB Access Rd - U/S - XS 4
END DESCRIPTION:
XS GIS Cut Line= 5
      3112839.56     13852172.71      3112376.46     13848681.01
      3113101.29     13847484.63      3113185.37     13847106.27
       3113640.8     13845494.72
#Sta/Elev= 30
   -84.8   54.37  1375.2   52.59  1565.2   54.33  2025.2   54.56  2735.2   51.99
  2825.2   53.08  3497.5   52.23    4436   44.31  4507.5   40.51  4707.5   40.89
  4876.3   38.57  4886.3   37.31  4896.3   35.56 4961.56   17.19 4987.22    7.39
  4987.4    6.14 4995.89    4.41 5006.44    5.22  5056.3   20.35  5096.3   26.24
  5156.3   47.03  5176.3   49.64  5543.9   52.03  5823.9   48.79  5883.9   49.03
  6013.9   53.19  6183.9   51.63  6523.9    53.1  6613.9   51.91  6898.6   54.48
#Mann= 5 ,-1 , 0
   -84.8     .08       0    4436     .05       0  4886.3    .015       0
  5056.3     .04       0  5176.3     .08       0
Bank Sta=4896.3,5156.3
XS Rating Curve= 0 ,0
Exp/Cntr=0.5,0.3

Type RM Length L Ch R = 1 ,14977.0 ,67.9,80,81
BEGIN DESCRIPTION:
Upstream Section of Bridge/Culvert/Weir
END DESCRIPTION:
XS GIS Cut Line= 6
       3112918.8     13852246.29      3112455.69     13848754.58
      3113225.41     13847433.76      3113680.02     13847455.12
      3114016.71     13847238.67      3114254.95     13845644.08
#Sta/Elev= 30
-160.372   54.51 -67.953   53.73 915.138   52.411268.691   54.712401.688   52.01
2868.379   45.212981.516   45.713151.221   39.513365.545   39.653406.275   28.24
3491.128   19.023520.614    7.783520.826    5.823530.584    4.163550.949    5.58
3580.859   20.013604.334   21.27 3649.59   40.723695.552   41.113701.845   37.21
3733.736   37.713776.162   44.013804.447   45.214016.791   45.814045.075   48.81
4426.914   52.914695.613   53.314964.314   57.114999.669   53.415156.152   54.71
#Mann= 5 ,-1 , 0
-160.372     .99       0 -67.953     .08       03365.545    .015       0
 3649.59     .08       04426.914     .99       0
#XS Ineff= 2 , 0
       03334.829   39.943674.487       0    41.1
Permanent Ineff=
       F       F
Bank Sta=3365.545,3649.59
XS Rating Curve= 0 ,0
Skew Angle= 45
Exp/Cntr=0.5,0.3