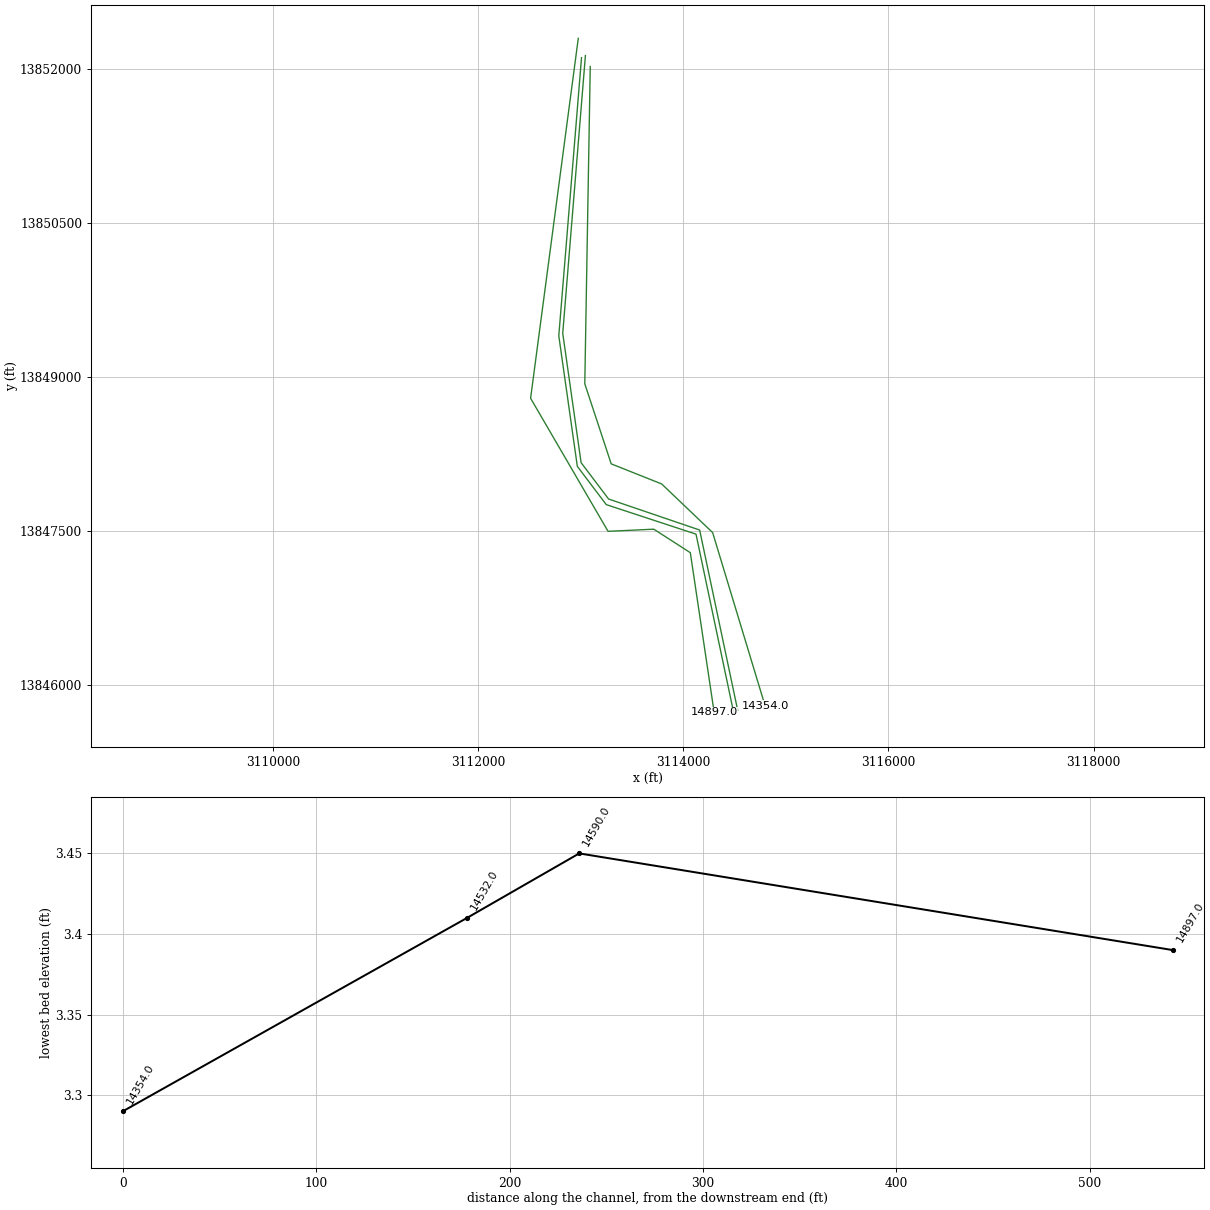
HEC-RAS study E100-00-00.prj: E100-00-00

--- E100-00-00.g02 (geometry) --- (continued)

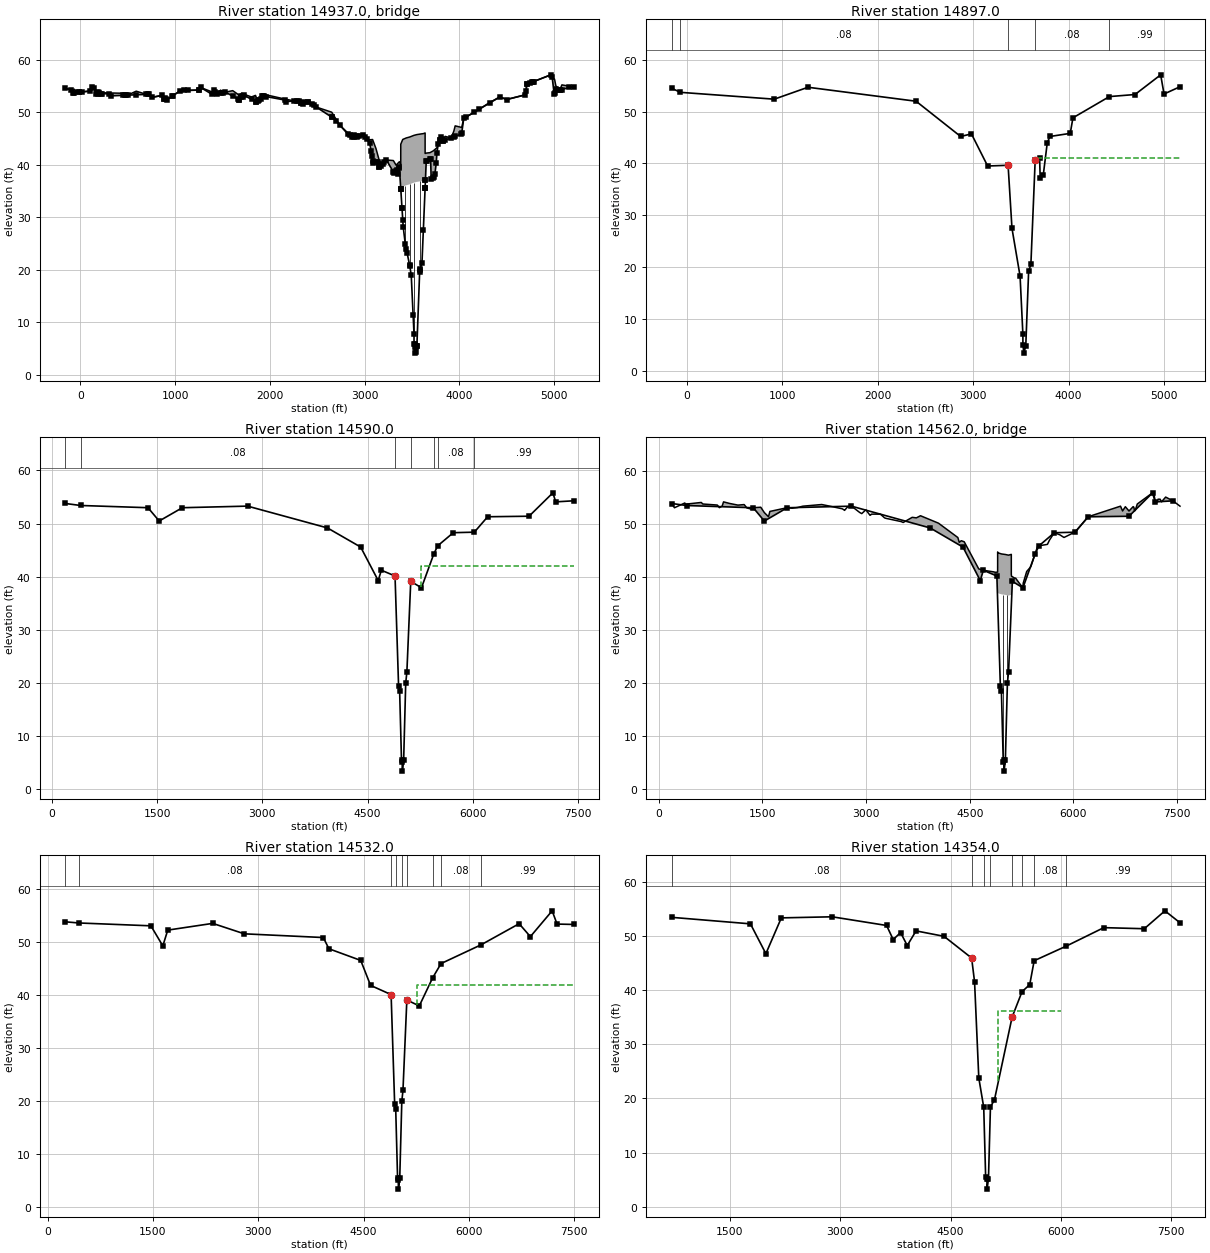
Type RM Length L Ch R = 3 ,14937.0 ,,,
BEGIN DESCRIPTION:
ACCES ROAD I-10
Structure ID: E100-00-00-15
Bridge has 45 degree skew with channel.
END DESCRIPTION:
Bridge Culvert--1,0,-1,-1, 0
Deck Dist Width WeirC Skew NumUp NumDn MinLoCord MaxHiCord MaxSubmerge Is_Ogee
10,60,2.6,45, 199, 199, , , 0.95, 0, ,,,
 -159.67  -96.03  -81.88  -67.95  -18.46  -11.38    16.9  101.97  123.18  144.39
   165.6  179.75  186.82  214.89  229.03  307.03  321.17  455.31  469.45  483.59
  497.73  589.66  695.72  709.87  724.22   752.5  865.64  886.64  886.85  893.92
  907.85  915.14  964.42  978.57 1056.56 1098.77 1134.13 1254.34 1254.55 1268.69
  1388.9 1410.11 1424.04 1431.11  1438.4 1480.61  1508.9 1530.32 1607.89 1664.67
  1678.6 1678.81 1692.96 1699.81 1721.24 1728.31 1805.88 1848.31 1848.52 1869.52
 1876.59 1883.66 1905.09  1919.2 1926.09 1933.16 1961.44 2159.65 2166.72 2258.43
 2286.71 2308.14 2329.35 2330.98 2345.12 2352.19 2401.69 2406.92 2440.01 2461.23
 2489.51 2652.15 2656.25 2698.67    2737 2818.88 2847.17 2868.38 2882.52 2889.59
 2913.78 2920.85 2934.99 2981.52  3005.7 3019.84 3052.23 3066.37 3073.44 3083.48
 3087.58 3118.84 3137.08 3151.22 3154.19 3168.33 3189.55 3203.69    3229 3302.68
 3306.79 3331.46 3342.14 3356.28 3365.55 3366.18 3380.46 3380.54 3380.61  3393.7
 3393.76 3401.75 3406.28 3429.04 3438.38 3448.21 3473.73 3475.01 3491.13 3510.93
 3520.61 3520.83 3528.32 3529.45 3530.58 3539.42 3541.62 3542.61 3546.85 3550.95
 3579.66 3580.86 3582.27 3604.34 3618.83 3637.56 3637.64 3637.72 3641.03 3641.11
 3649.59 3653.55 3688.69 3695.55 3701.85 3723.98 3733.74 3740.81 3754.95 3762.02
 3776.16 3790.94 3792.28 3804.45  3813.5 3825.66 3827.64 3848.85 3912.49 3940.78
 3954.92 4016.79 4023.86 4045.08 4069.82 4154.68 4204.17 4324.38 4426.91 4497.62
 4695.61 4702.69 4709.76 4713.29 4748.65 4769.86 4776.93    4784 4964.31 4978.46
 4999.67 5003.21 5017.35 5020.88 5059.77 5063.31 5080.99 5156.86  5203.6
    54.5    54.3    53.7    54.4    53.8   53.83   53.87   54.01   54.71   54.51
    54.1   54.13   54.14    54.2    53.7   53.67   53.66    53.6   53.22    53.4
   53.24      54    53.4    53.4   53.41   52.81   53.21   52.52   52.51   52.71
   52.51   52.41      53   53.17   54.11   54.13   54.15   54.21   54.21   54.71
   53.86   54.31   53.87   53.64    53.6    54.2   53.72   53.81    54.1   53.38
    53.2    53.2   53.47    53.6   53.46   53.41    52.9    53.2   53.18    52.2
   52.26   52.32   52.51   53.11   53.09   53.06    53.3    52.5   52.47   52.14
   52.18   52.21   51.71   51.81   51.91   51.51   52.01   51.95   51.56   51.31
   50.98      50   49.88   48.63   47.54   46.11   45.71   45.27   45.61   45.21
   45.34   45.38   45.46   45.71    45.4    44.9   44.75   44.77   44.78    44.8
    44.6    43.1   41.91   40.99    40.8    40.4    40.2   40.45   40.91    40.8
   40.67   39.92   40.12   40.39   40.57   40.58      40    43.9    43.9   44.47
   44.47   44.82   44.85   45.03    45.1   45.15   45.27   45.28    45.4   45.55
    45.6    45.6   45.64   45.64   45.65   45.69    45.7   45.71   45.73   45.74
   45.83   45.84   45.84   45.89   45.92   46.05   46.05   42.15   42.17   42.17
   42.21   42.23    42.3   42.37   42.43   42.65    42.8   42.91   43.13   43.23
   44.01   44.64   44.69   45.21   44.91   44.51    44.6    45.4    45.1    46.4
    47.4   47.13    47.1   48.81   49.08   49.99   50.52    51.9   52.91   52.41
   53.31   54.01   55.31   55.34   55.59   55.74   55.79   55.84   57.11   56.61
   56.26    56.3      55   54.94    54.3   54.45    55.2   54.95    54.8
                                                                                
                                                                                
                                                                                
                                                                                
                                                                                
                                                                                
                                                                                
                                                                                
                                                                                
                                                                                
                                                                                
                                                                                
   35.47   35.82   35.85   36.03    36.1   36.15   36.27   36.28    36.4   36.55
    36.6    36.6   36.64   36.64   36.65   36.69    36.7   36.71   36.73   36.74
   36.83   36.84   36.84   36.89   36.92   37.05   37.05
                                                                                
                                                                                
                                                                                
                                                                                
                                                                        
 -159.67  -96.03  -81.88  -67.95  -18.46  -11.38    16.9  101.97  123.18  144.39
   165.6  179.75  186.82  214.89  229.03  307.03  321.17  455.31  469.45  483.59
  497.73  589.66  695.72  709.87  724.22   752.5  865.64  886.64  886.85  893.92
  907.85  915.14  964.42  978.57 1056.56 1098.77 1134.13 1254.34 1254.55 1268.69
  1388.9 1410.11 1424.04 1431.11  1438.4 1480.61  1508.9 1530.32 1607.89 1664.67
  1678.6 1678.81 1692.96 1699.81 1721.24 1728.31 1805.88 1848.31 1848.52 1869.52
 1876.59 1883.66 1905.09 1919.24 1926.09 1933.16 1961.44 2159.65 2166.72 2258.43
 2286.71 2308.14 2329.35 2330.98 2345.12 2352.19 2401.69 2406.92 2440.01 2461.23
 2489.51 2652.15 2656.25 2698.67    2737 2818.88 2847.17 2868.38 2882.52 2889.59
 2913.78 2920.85 2934.99 2981.52  3005.7 3019.84 3052.23 3066.37 3073.44 3083.48
 3087.58 3118.84 3137.08 3151.22 3154.19 3168.33 3189.55 3203.69    3229 3302.68
 3306.79 3331.46 3342.14 3356.28 3365.55 3366.18 3380.46 3380.54 3380.61  3393.7
 3393.76 3401.75 3406.28 3429.04 3438.38 3448.21 3473.73 3475.01 3491.13 3510.93
 3520.61 3520.83 3528.32 3529.45 3530.58 3539.42 3541.62 3542.61 3546.85 3550.95
 3579.66 3580.86 3582.27 3604.34 3618.83 3637.56 3637.64 3637.72 3641.03 3641.11
 3649.59 3653.55 3688.69 3695.55 3701.85 3723.98 3733.74 3740.81 3754.95 3762.02
 3776.16 3790.94 3792.28 3804.45  3813.5 3825.66 3827.64 3848.85 3912.49 3940.78
 3954.92 4016.79 4023.86 4045.08 4069.82 4154.68 4204.17 4324.38 4426.91 4497.62
 4695.61 4702.69 4709.76 4713.29 4748.65 4769.86 4776.93    4784 4964.31 4978.46
 4999.67 5003.21 5017.35 5020.88 5059.77 5063.31 5080.99 5156.86  5203.6
    54.5    54.3    53.7    54.4    53.8   53.83   53.87   54.01   54.71   54.51
    54.1   54.13   54.14    54.2    53.7   53.67   53.66    53.6   53.22    53.4
   53.24      54    53.4    53.4   53.41   52.81   53.21   52.52   52.51   52.71
   52.51   52.41      53   53.17   54.11   54.13   54.15   54.21   54.21   54.71
   53.86   54.31   53.87   53.64    53.6    54.2   53.72   53.81    54.1   53.38
    53.2    53.2   53.47    53.6   53.46   53.41    52.9    53.2   53.18    52.2
   52.26   52.32   52.51   53.11   53.09   53.06    53.3    52.5   52.47   52.14
   52.18   52.21   51.71   51.81   51.91   51.51   52.01   51.95   51.56   51.31
   50.98      50   49.88   48.63   47.54   46.11   45.71   45.27   45.61   45.21
   45.34   45.38   45.46   45.71    45.4    44.9   44.75   44.77   44.78    44.8
    44.6    43.1   41.91   40.99    40.8    40.4    40.2   40.45   40.91    40.8
   40.67   39.92   40.12   40.39   40.57   40.58      40    43.9    43.9   44.47
   44.47   44.82   44.85   45.03    45.1   45.15   45.27   45.28    45.4   45.55
    45.6    45.6   45.64   45.64   45.65   45.69    45.7   45.71   45.73   45.74
   45.83   45.84   45.84   45.89   45.92   46.05   46.05   42.15   42.17   42.17
   42.21   42.23    42.3   42.37   42.43   42.65    42.8   42.91   43.13   43.23
   44.01   44.64   44.69   45.21   44.91   44.51    44.6    45.4    45.1    46.4
    47.4   47.13    47.1   48.81   49.08   49.99   50.52    51.9   52.91   52.41
   53.31   54.01   55.31   55.34   55.59   55.74   55.79   55.84   57.11   56.61
   56.26    56.3      55   54.94    54.3   54.45    55.2   54.95    54.8
                                                                                
                                                                                
                                                                                
                                                                                
                                                                                
                                                                                
                                                                                
                                                                                
                                                                                
                                                                                
                                                                                
                                                                                
   35.47   35.82   35.85   36.03    36.1   36.15   36.27   36.28    36.4   36.55
    36.6    36.6   36.64   36.64   36.65   36.69    36.7   36.71   36.73   36.74
   36.83   36.84   36.84   36.89   36.92   37.05   37.05
                                                                                
                                                                                
                                                                                
                                                                                
                                                                        
Pier Skew, UpSta & Num, DnSta & Num=  ,3429.04, 2 ,3429.04, 2 , 0 , 0 , 0 ,,
     2.5     2.5
   23.74   37.04
     2.5     2.5
   22.98   36.28
Pier Skew, UpSta & Num, DnSta & Num=  ,3475.01, 2 ,3475.01, 2 , 0 , 0 , 0 ,,
     2.5     2.5
   19.71   37.29
     2.5     2.5
   18.95   36.53
Pier Skew, UpSta & Num, DnSta & Num=  ,3520.61, 2 ,3520.61, 2 , 0 , 0 , 0 ,,
     2.5     2.5
    4.81    37.6
     2.5     2.5
    4.05   36.84
Pier Skew, UpSta & Num, DnSta & Num=  ,3580.86, 2 ,3580.86, 2 , 0 , 0 , 0 ,,
     2.5     2.5
   18.72   37.84
     2.5     2.5
   17.96   37.08
BR Coef= 1 , 1 , 0 ,1.25, 0 ,,,0.8,-1,1.2,0,
WSPro=,,,, 1 ,,,, 0 ,,,, 0 ,,,,-1 ,-1 ,-1 , 0 , 0 , 0 , 0 , 0
BR U #Sta/Elev= 199
 -159.67   54.51  -96.03   54.31  -81.88   53.71  -67.95   53.73  -18.46   53.81
  -11.38   53.83    16.9   53.87  101.97   54.01  123.18   54.71  144.39   54.51
   165.6   53.41  179.75   53.91  186.82   53.51  214.89   53.51  229.03   53.51
  307.03   53.51  321.17   53.11  455.31   53.21  469.45   53.22  483.59   53.23
  497.73   53.24  589.66   53.31  695.72   53.39  709.87    53.4  724.22   53.41
   752.5   52.81  865.64   53.21  886.64   52.52  886.85   52.51  893.92   52.71
  907.85   52.51  915.14   52.41  964.42      53  978.57   53.17 1056.56   54.11
 1098.77   54.13 1134.13   54.15 1254.34   54.21 1254.55   54.21 1268.69   54.71
  1388.9   53.41 1410.11   54.31 1424.04   53.87 1431.11   53.64  1438.4   53.41
 1480.61   53.59  1508.9   53.72 1530.32   53.81 1607.89   53.06 1664.67   52.51
  1678.6   52.41 1678.81   52.41 1692.96   53.01 1699.81   52.96 1721.24   52.81
 1728.31   53.21 1805.88   52.44 1848.31   52.01 1848.52   52.01 1869.52    52.2
 1876.59   52.26 1883.66   52.32 1905.09   52.51 1919.23   53.11 1926.09   53.09
 1933.16   53.06 1961.44   52.97 2159.65   52.31 2166.72   52.01 2258.43   52.14
 2286.71   52.18 2308.14   52.21 2329.35   51.71 2330.98   51.81 2345.12   51.91
 2352.19   51.51 2401.69   52.01 2406.92   51.95 2440.01   51.56 2461.23   51.31
 2489.51   50.98 2652.15   49.06 2656.25   49.01 2698.67   48.31    2737   47.54
 2818.88   45.91 2847.17   45.71 2868.38   45.21 2882.52   45.61 2889.59   45.21
 2913.78   45.34 2920.85   45.38 2934.99   45.46 2981.52   45.71  3005.7    45.2
 3019.84    44.9 3052.23   44.21 3066.37   42.71 3073.44   41.61 3083.48   40.76
 3087.58   40.41 3118.84   40.47 3137.08   40.51 3151.22   39.51 3154.19   39.56
 3168.33   39.82 3189.55    40.2 3203.69   40.45    3229   40.91 3302.68   38.64
 3306.79   38.51 3331.46   38.86 3342.14   39.01 3356.28   38.21 3365.55   39.65
 3366.18   39.47 3380.46   35.47 3380.54   35.45 3380.61   35.43  3393.7   31.76
 3393.76   31.75 3401.75   29.51 3406.28   28.24 3429.04   24.83 3438.38   24.01
 3448.21   23.15 3473.73   20.93 3475.01   20.82 3491.13   19.02 3510.93   11.47
 3520.61    7.78 3520.83    5.82 3528.32    5.82 3529.45     5.3 3530.58    4.16
 3539.42    4.33 3541.62    5.37 3542.61    5.54 3546.85    5.56 3550.95    5.58
 3579.66   19.63 3580.86   20.01 3582.27   20.09 3604.34   21.27 3618.83    27.5
 3637.56   35.55 3637.64   35.58 3637.72   35.62 3641.03   37.04 3641.11   37.07
 3649.59   40.72 3653.55   40.75 3688.69   41.05 3695.55   41.11 3701.85   37.21
 3723.98   37.56 3733.74   37.71 3740.81   38.21 3754.95   40.31 3762.02   42.21
 3776.16   44.01 3790.94   44.64 3792.28   44.69 3804.45   45.21  3813.5   44.91
 3825.66   44.51 3827.64   44.52 3848.85   44.67 3912.49    45.1 3940.78   45.29
 3954.92   45.39 4016.79   45.81 4023.86   46.01 4045.08   48.81 4069.82   49.08
 4154.68   49.99 4204.17   50.52 4324.38   51.81 4426.91   52.91 4497.62   52.41
 4695.61   53.31 4702.69   54.01 4709.76   55.31 4713.29   55.34 4748.65   55.59
 4769.86   55.74 4776.93   55.79    4784   55.84 4964.31   57.11 4978.46   56.61
 4999.67   53.41 5003.21   53.58 5017.35   54.24 5020.88   54.41 5059.77   54.23
 5063.31   54.21 5080.99    54.3 5156.86   54.71  5203.6   54.81
BR U #Mann= 5
 -159.67     .99  -67.95     .08 3365.55    .015 3649.59     .08 4426.91     .99
BR U Banks=3365.55,
BR D #Sta/Elev= 199
 -159.67   54.51  -96.03   54.31  -81.88   53.71  -67.95   53.73  -18.46   53.81
  -11.38   53.83    16.9   53.87  101.97   54.01  123.18   54.71  144.39   54.51
   165.6   53.41  179.75   53.91  186.82   53.51  214.89   53.51  229.03   53.51
  307.03   53.51  321.17   53.11  455.31   53.21  469.45   53.22  483.59   53.23
  497.73   53.24  589.66   53.31  695.72   53.39  709.87    53.4  724.22   53.41
   752.5   52.81  865.64   53.21  886.64   52.52  886.85   52.51  893.92   52.71
  907.85   52.51  915.14   52.41  964.42      53  978.57   53.17 1056.56   54.11
 1098.77   54.13 1134.13   54.15 1254.34   54.21 1254.55   54.21 1268.69   54.71
  1388.9   53.41 1410.11   54.31 1424.04   53.87 1431.11   53.64  1438.4   53.41
 1480.61   53.59  1508.9   53.72 1530.32   53.81 1607.89   53.06 1664.67   52.51
  1678.6   52.41 1678.81   52.41 1692.96   53.01 1699.81   52.96 1721.24   52.81
 1728.31   53.21 1805.88   52.44 1848.31   52.01 1848.52   52.01 1869.52    52.2
 1876.59   52.26 1883.66   52.32 1905.09   52.51 1919.23   53.11 1926.09   53.09
 1933.16   53.06 1961.44   52.97 2159.65   52.31 2166.72   52.01 2258.43   52.14
 2286.71   52.18 2308.14   52.21 2329.35   51.71 2330.98   51.81 2345.12   51.91
 2352.19   51.51 2401.69   52.01 2406.92   51.95 2440.01   51.56 2461.23   51.31
 2489.51   50.98 2652.15   49.06 2656.25   49.01 2698.67   48.31    2737   47.54
 2818.88   45.91 2847.17   45.71 2868.38   45.21 2882.52   45.61 2889.59   45.21
 2913.78   45.34 2920.85   45.38 2934.99   45.46 2981.52   45.71  3005.7    45.2
 3019.84    44.9 3052.23   44.21 3066.37   42.71 3073.44   41.61 3083.48   40.76
 3087.58   40.41 3118.84   40.47 3137.08   40.51 3151.22   39.51 3154.19   39.56
 3168.33   39.82 3189.55    40.2 3203.69   40.45    3229   40.91 3302.68   38.64
 3306.79   38.51 3331.46   38.86 3342.14   39.01 3356.28   38.21 3365.55   39.65
 3366.18    38.7 3380.46    34.7 3380.54   34.68 3380.61   34.66  3393.7   30.99
 3393.76   30.98 3401.75   28.74 3406.28   27.47 3429.04   24.06 3438.38   23.24
 3448.21   22.38 3473.73   20.16 3475.01   20.05 3491.13   18.25 3510.93    10.7
 3520.61    7.01 3520.83    5.05 3528.32    5.05 3529.45    4.53 3530.58    3.39
 3539.42    3.56 3541.62     4.6 3542.61    4.77 3546.85    4.79 3550.95    4.81
 3579.66   18.86 3580.86   19.24 3582.27   19.32 3604.34    20.5 3618.83   26.73
 3637.56   34.78 3637.64   34.81 3637.72   34.85 3641.03   36.27 3641.11    36.3
 3649.59   40.72 3653.55   40.75 3688.69   41.05 3695.55   41.11 3701.85   37.21
 3723.98   37.56 3733.74   37.71 3740.81   38.21 3754.95   40.31 3762.02   42.21
 3776.16   44.01 3790.94   44.64 3792.28   44.69 3804.45   45.21  3813.5   44.91
 3825.66   44.51 3827.64   44.52 3848.85   44.67 3912.49    45.1 3940.78   45.29
 3954.92   45.39 4016.79   45.81 4023.86   46.01 4045.08   48.81 4069.82   49.08
 4154.68   49.99 4204.17   50.52 4324.38   51.81 4426.91   52.91 4497.62   52.41
 4695.61   53.31 4702.69   54.01 4709.76   55.31 4713.29   55.34 4748.65   55.59
 4769.86   55.74 4776.93   55.79    4784   55.84 4964.31   57.11 4978.46   56.61
 4999.67   53.41 5003.21   53.58 5017.35   54.24 5020.88   54.41 5059.77   54.23
 5063.31   54.21 5080.99    54.3 5156.86   54.71  5203.6   54.81
BR D #Mann= 5
 -159.67     .99  -67.95     .08 3365.55    .015 3649.59     .08 4426.91     .99
BR D Banks=3365.55,
BC Design=,, 0 ,, 0 ,,,,,,
BC HTab HWMax=57.11
BC Use User HTab Curves=0
BC User HTab FreeFlow(D)= 0

Type RM Length L Ch R = 1 ,14897.0 ,386.5,307,296.5
BEGIN DESCRIPTION:
Downstream Section of Bridge/Culvert/Weir
END DESCRIPTION:
XS GIS Cut Line= 6
 3112975.0106429 13852294.784718        3112510.     13848788.68
      3113265.39     13847492.44       3113711.4     13847513.39
      3114067.58     13847284.42 3114300.161037913845727.7001752
#Sta/Elev= 30
-159.665   54.51 -67.953   53.73 915.138   52.411268.691   54.712401.688   52.01
2868.379   45.212981.516   45.713151.221   39.513365.545   39.653406.275   27.47
3491.128   18.253520.614    7.013520.826    5.053530.584    3.393550.949    4.81
3580.859   19.243604.334    20.5 3649.59   40.723695.552   41.113701.845   37.21
3733.736   37.713776.162   44.013804.447   45.214016.791   45.814045.075   48.81
4426.914   52.914695.613   53.314964.314   57.114999.669   53.41  5166.9   54.81
#Mann= 5 ,-1 , 0
-159.665     .99       0 -67.953     .08       03365.545    .015       0
 3649.59     .08       04426.914     .99       0
#XS Ineff= 2 , 0
       03341.002   39.423668.307       0    41.1
Permanent Ineff=
       F       F
Bank Sta=3365.545,3649.59
XS Rating Curve= 0 ,0
Skew Angle= 45
Exp/Cntr=0.5,0.3

Type RM Length L Ch R = 1 ,14590.0 ,54.4,58,59
BEGIN DESCRIPTION:
Upstream Section of Bridge/Culvert/Weir
END DESCRIPTION:
XS GIS Cut Line= 6
      3113006.52     13852106.04      3112784.92     13849396.96
      3112965.65      13848125.6      3113247.96     13847752.55
      3114123.08      13847465.1      3114491.88     13845719.11
#Sta/Elev= 30
   189.9    53.8     408   53.42  1369.9      53  1529.9    50.5  1859.9      53
  2789.9    53.3    3928    49.2  4402.2    45.6  4652.2    39.3    4697   41.24
  4892.2   40.16  4942.6   19.55  4957.7   18.58  4984.8    5.25  4993.1    5.55
  4996.6    3.45  5015.2    5.56  5044.5   20.02    5061   22.08  5116.2   39.15
  5269.3   37.94  5445.6   44.33  5501.1   45.84  5722.8    48.3  6022.8    48.4
  6212.8    51.3  6802.8    51.4  7142.8    55.8  7182.8    54.1  7437.1    54.3
#Mann= 7 ,-1 , 0
   189.9     .99       0     408     .08       0  4892.2    .015       0
  5116.2     .08       0  5445.6     .05       0  5501.1     .08       0
  6022.8     .99       0
#XS Ineff= 2 , 0
       0 4841.92   40.16    5258       0      42
Permanent Ineff=
       F       T
Bank Sta=4892.2,5116.2
XS Rating Curve= 0 ,0
Exp/Cntr=0.5,0.3

Type RM Length L Ch R = 3 ,14562.0 ,,,
BEGIN DESCRIPTION:
I-10 ACCESS ROAD
Structure ID: E100-00-00-14
END DESCRIPTION:
Bridge Culvert--1,0,-1,-1, 0
Deck Dist Width WeirC Skew NumUp NumDn MinLoCord MaxHiCord MaxSubmerge Is_Ogee
10,36,2.6,0, 172, 172, , , 0.95, 0, ,,,
   189.9   229.9   379.9   399.9     408   489.9     618   639.9     648   849.9
   879.9   919.9   939.9    1028    1148    1238    1278  1349.9  1369.9    1478
  1529.9  1589.9  1609.9    1638    1658    1698    1708    1728    1778    1808
    1838  1859.9  1929.9    1978    2008    2088  2359.9    2368    2478    2658
  2669.9    2678  2689.9  2729.9    2758  2789.9  2899.9    2908    2938    2998
    3008    3028    3058    3068    3078    3158    3208    3268    3288    3508
    3538    3668    3728    3788    3868    3898    3928    4048    4078  4192.2
  4212.2  4252.2  4312.2    4328    4348    4378  4402.2    4420  4602.2  4612.2
    4630  4652.2    4660  4681.9    4697  4697.1  4759.7  4789.2    4817  4840.8
  4869.7 4885.51  4885.6  4892.2 4903.29  4903.4 4903.51  4906.8  4942.6  4957.7
  4959.1  4982.7  4984.8  4993.1    4994  4996.6  5003.9  5006.1  5006.3  5010.7
  5015.2  5042.8  5044.5  5059.7    5061 5100.99  5101.1 5101.21  5104.5 5108.09
  5108.2  5116.2    5150  5163.1  5202.7  5213.5  5269.2  5269.3  5273.2  5323.2
  5357.1  5383.2  5445.6  5477.1  5483.2  5501.1  5617.1  5623.2  5647.1  5652.8
  5722.8    5760  5802.8  5862.8  6022.8    6190  6212.8    6680    6710    6750
  6802.8  6862.8  6872.8    6880  6882.8  6892.8  6922.8    7140  7142.8  7162.8
  7182.8  7212.8  7222.8  7252.8  7272.8    7280    7330  7332.8    7360    7370
  7437.4  7540.3
    53.8      53    53.9    53.4    53.7   53.82      54   53.71    53.7   53.51
   53.02   53.31   54.11   53.81    53.5    53.6   52.96   52.72   53.01    53.1
   52.09   51.31   52.31   52.39   52.44   52.56   52.58   52.64   52.78   52.86
   52.95   53.01   52.91   52.99   53.04    53.3   53.61   53.59    53.3    52.8
   52.71   52.63   52.51   53.11    53.2   53.31   52.18   52.12    51.9   52.61
   52.44    52.1   51.58   51.65    51.8    51.8    51.8    51.1   51.01    50.4
   50.23    51.2    51.1    51.5   51.07   50.91   50.75    50.1   49.81   48.71
   48.52   48.13   47.55    47.4    46.5    46.8   46.68    46.6   42.18   41.93
    41.5   41.41   41.38    41.3   41.24   41.24   41.12   41.07   41.03   40.95
   40.86   40.87   40.87   40.88   40.89   44.69   44.69   44.53   44.38   44.32
   44.31   44.27   44.27   44.25   44.25   44.24   44.23   44.23   44.23   44.22
   44.21   44.12   44.12   44.07   44.08   44.23   44.23   40.43   40.12   40.09
   40.09   40.03   39.76   39.76   39.06   38.86   37.94   37.94   38.81   41.01
   41.52   41.91   44.34   45.57   45.81   45.85    46.1   46.11   46.76   46.91
   48.31   48.12   47.91   47.41   48.43   50.96   51.31    53.3    52.4    53.2
   52.39   53.21   53.11   52.61   52.41   52.51   53.71   55.78   55.81   55.61
   54.11   54.11   54.61   54.61   54.11   54.22   54.97   55.01   54.83   54.76
   54.31    53.3
                                                                                
                                                                                
                                                                                
                                                                                
                                                                                
                                                                                
                                                                                
                                                                                
                                                                                
                                                   37.09   36.93   36.78   36.72
   36.71   36.67   36.67   36.65   36.65   36.64   36.63   36.63   36.63   36.62
   36.61   36.52   36.52   36.47   36.48   36.63
                                                                                
                                                                                
                                                                                
                                                                                
                                                                                
                
   189.9   229.9   379.9   399.9     408   489.9     618   639.9     648   849.9
   879.9   919.9   939.9    1028    1148    1238    1278  1349.9  1369.9    1478
  1529.9  1589.9  1609.9    1638    1658    1698    1708    1728    1778    1808
    1838  1859.9  1929.9    1978    2008    2088  2359.9    2368    2478    2658
  2669.9    2678  2689.9  2729.9    2758  2789.9  2899.9    2908    2938    2998
    3008    3028    3058    3068    3078    3158    3208    3268    3288    3508
    3538    3668    3728    3788    3868    3898    3928    4048    4078  4192.2
  4212.2  4252.2  4312.2    4328    4348    4378  4402.2    4420  4602.2  4612.2
    4630  4652.2    4660  4681.9    4697  4697.1  4759.7  4789.2    4817  4840.8
  4869.7 4885.51  4885.6  4892.2 4903.29  4903.4 4903.51  4906.8  4942.6  4957.7
  4959.1  4982.7  4984.8  4993.1    4994  4996.6  5003.9  5006.1  5006.3  5010.7
  5015.2  5042.8  5044.5  5059.7    5061 5100.99  5101.1 5101.21  5104.5 5108.09
  5108.2  5116.2    5150  5163.1  5202.7  5213.5  5269.2  5269.3  5273.2  5323.2
  5357.1  5383.2  5445.6  5477.1  5483.2  5501.1  5617.1  5623.2  5647.1  5652.8
  5722.8    5760  5802.8  5862.8  6022.8    6190  6212.8    6680    6710    6750
  6802.8  6862.8  6872.8    6880  6882.8  6892.8  6922.8    7140  7142.8  7162.8
  7182.8  7212.8  7222.8  7252.8  7272.8    7280    7330  7332.8    7360    7370
  7437.4  7540.3
    53.8      53    53.9    53.4    53.7   53.82      54   53.71    53.7   53.51
   53.02   53.31   54.11   53.81    53.5    53.6   52.96   52.72   53.01    53.1
   52.09   51.31   52.31   52.39   52.44   52.56   52.58   52.64   52.78   52.86
   52.95   53.01   52.91   52.99   53.04    53.3   53.61   53.59    53.3    52.8
   52.71   52.63   52.51   53.11    53.2   53.31   52.18   52.12    51.9   52.61
   52.44    52.1   51.58   51.65    51.8    51.8    51.8    51.1   51.01    50.4
   50.23    51.2    51.1    51.5   51.07   50.91   50.75    50.1   49.81   48.71
   48.52   48.13   47.55    47.4    46.5    46.8   46.68    46.6   42.18   41.93
    41.5   41.41   41.38    41.3   41.24   41.24   41.12   41.07   41.03   40.95
   40.86   40.87   40.87   40.88   40.89   44.69   44.69   44.53   44.38   44.32
   44.31   44.27   44.27   44.25   44.25   44.24   44.23   44.23   44.23   44.22
   44.21   44.12   44.12   44.07   44.08   44.23   44.23   40.43   40.12   40.09
   40.09   40.03   39.76   39.76   39.06   38.86   37.94   37.94   38.81   41.01
   41.52   41.91   44.34   45.57   45.81   45.85    46.1   46.11   46.76   46.91
   48.31   48.12   47.91   47.41   48.43   50.96   51.31    53.3    52.4    53.2
   52.39   53.21   53.11   52.61   52.41   52.51   53.71   55.78   55.81   55.61
   54.11   54.11   54.61   54.61   54.11   54.22   54.97   55.01   54.83   54.76
   54.31    53.3
                                                                                
                                                                                
                                                                                
                                                                                
                                                                                
                                                                                
                                                                                
                                                                                
                                                                                
                                                   37.09   36.93   36.78   36.72
   36.71   36.67   36.67   36.65   36.65   36.64   36.63   36.63   36.63   36.62
   36.61   36.52   36.52   36.47   36.48   36.63
                                                                                
                                                                                
                                                                                
                                                                                
                                                                                
                
Pier Skew, UpSta & Num, DnSta & Num=  ,4982.7, 2 ,4982.7, 2 , 0 , 0 , 0 ,,
     2.5     2.5
    4.96   37.67
     2.5     2.5
    4.93   37.64
Pier Skew, UpSta & Num, DnSta & Num=  ,5042.8, 2 ,5042.8, 2 , 0 , 0 , 0 ,,
     2.5     2.5
   16.88   37.52
     2.5     2.5
   16.85   37.49
BR Coef= 1 , 1 , 0 ,1.25, 0 ,,,0.8,0,1.2,0,
WSPro=,,,, 1 ,,,, 0 ,,,, 0 ,,,,-1 ,-1 ,-1 , 0 , 0 , 0 , 0 , 0
BC Design=,, 0 ,, 0 ,,,,,,
BC HTab HWMax=55.8
BC Use User HTab Curves=0
BC User HTab FreeFlow(D)= 0

Type RM Length L Ch R = 1 ,14532.0 ,196.4,178,136
BEGIN DESCRIPTION:
Downstream Section of Bridge/Culvert/Weir
END DESCRIPTION:
XS GIS Cut Line= 6
      3113044.71     13852127.48      3112823.39     13849421.74
      3113002.55     13848161.39      3113270.58     13847807.21
      3114158.64     13847505.06      3114529.52     13845749.19
#Sta/Elev= 30
   251.9   53.86   441.9   53.64  1471.9    53.1  1641.9   49.31  1711.9   52.29
  2351.9   53.56  2801.9   51.59  3926.7   50.89  4006.7   48.77  4459.7   46.57
  4599.7   41.86  4892.2   40.12  4942.6   19.51  4957.7   18.54  4984.8    5.21
  4993.1    5.51  4996.6    3.41  5015.2    5.52  5044.5   19.98    5061   22.04
  5116.2   39.11  5293.3   37.98  5483.3   43.28  5603.3   45.98    6175   49.53
    6715    53.5    6875   51.06    7185   55.93    7255   53.43  7489.6   53.36
#Mann= 9 ,-1 , 0
   251.9     .99       0   441.9     .08       0  4892.2     .04       0
  4957.7    .015       0  5044.5     .04       0  5116.2     .08       0
  5483.3     .05       0  5603.3     .08       0    6175     .99       0
#XS Ineff= 2 , 0
       0 4848.91   39.07    5258       0      42
Permanent Ineff=
       F       T
Bank Sta=4892.2,5116.2
XS Rating Curve= 0 ,0
Exp/Cntr=0.5,0.3

Type RM Length L Ch R = 1 ,14354.0 ,468.5,430,347.2
BEGIN DESCRIPTION:
Cross Section E100-00-00-X09
END DESCRIPTION:
XS GIS Cut Line= 6
      3113091.71     13852020.06      3113038.48     13848929.94
      3113296.08     13848149.67      3113788.33     13847953.92
      3114285.36     13847480.21       3114797.4     13845791.05
#Sta/Elev= 30
   710.5    53.4  1780.5    52.2  1990.5    46.7  2200.5    53.3  2890.5    53.5
  3630.5    51.9  3720.5    49.3  3821.1    50.6  3911.1    48.2  4031.1    50.9
  4411.1    49.9    4786    45.9    4826    41.5  4883.5   23.79  4950.4   18.39
  4976.7    5.47  4993.2    5.23  4996.2    3.29  5014.9    5.21  5041.8   18.45
  5095.9   19.74    5336      35  5470.8   39.69  5575.7      41  5635.7    45.4
  6072.3    48.1  6582.3    51.5  7132.3    51.3  7412.3    54.6  7617.3    52.4
#Mann= 8 ,-1 , 0
   710.5     .08       0    4786     .04       0  4950.4    .015       0
  5041.8     .04       0    5336     .12       0  5470.8     .05       0
  5635.7     .08       0  6072.3     .99       0
#XS Ineff= 1 ,-1
    5150    6000    36.2
Permanent Ineff=
       T
Bank Sta=4786,5336
XS Rating Curve= 0 ,0
Exp/Cntr=0.5,0.3