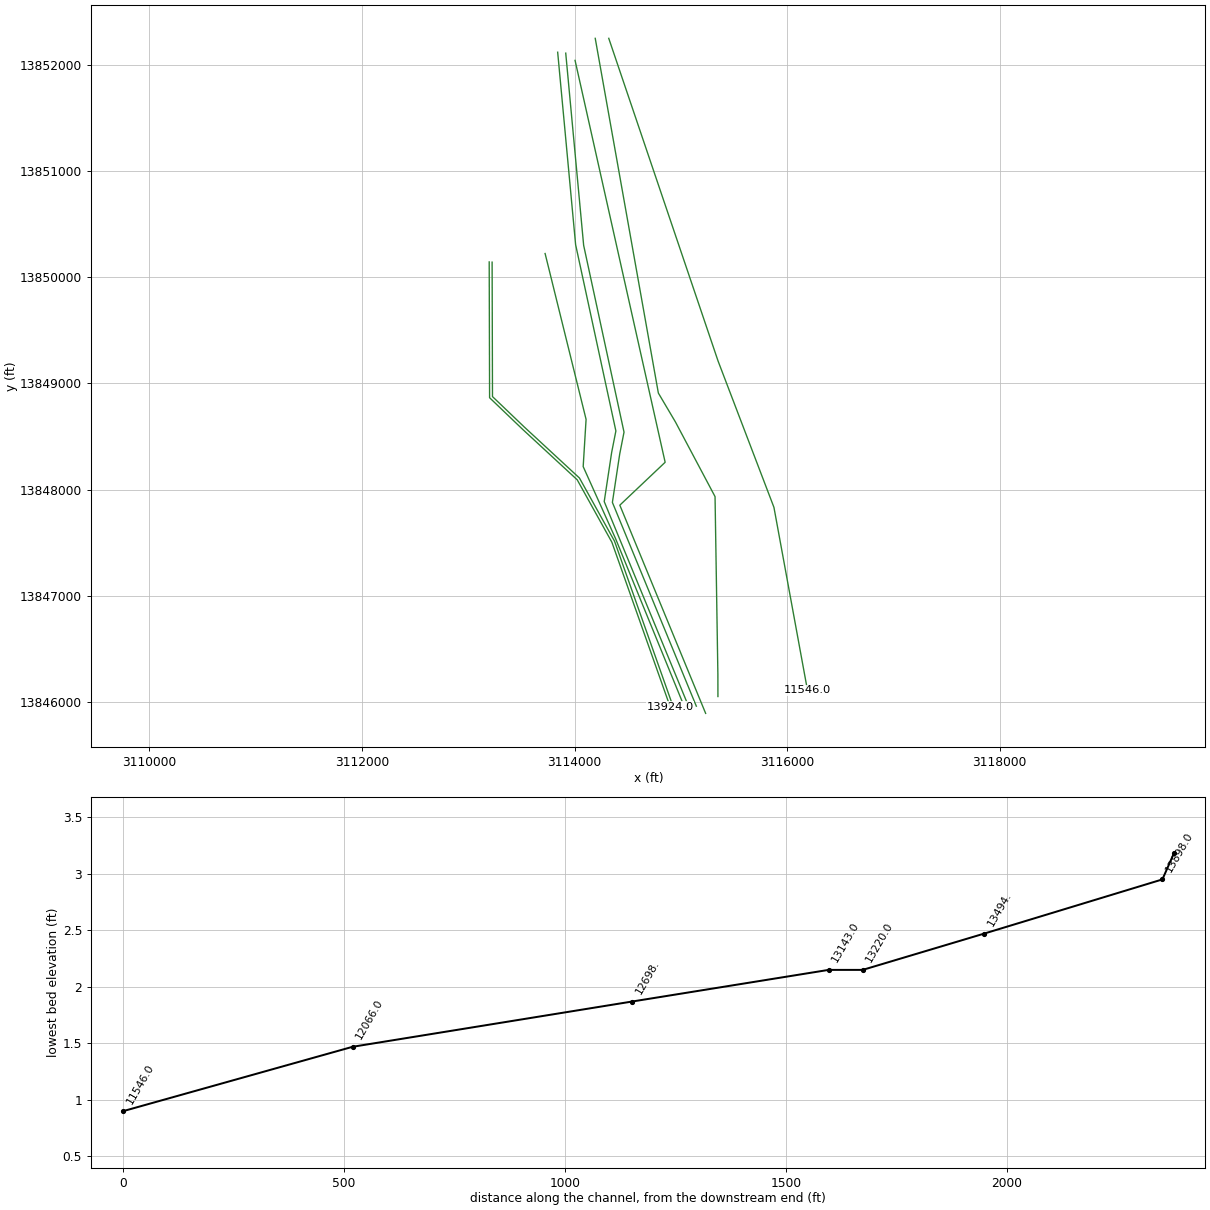
HEC-RAS study E100-00-00.prj: E100-00-00

--- E100-00-00.g02 (geometry) --- (continued)

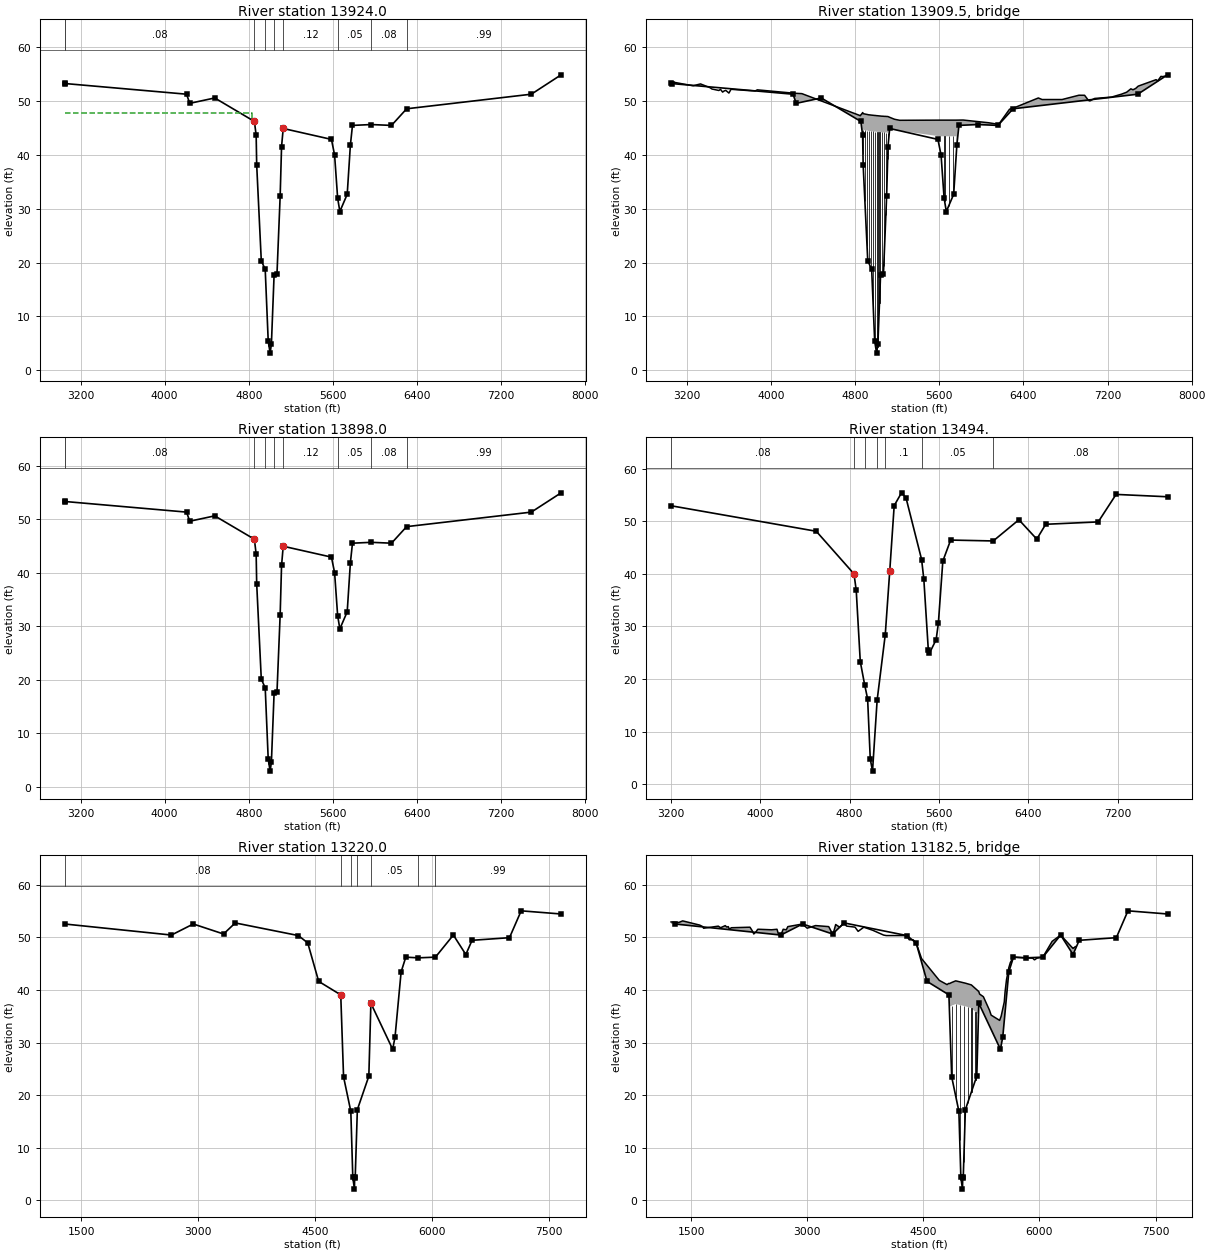
Type RM Length L Ch R = 1 ,13924.0 ,25,26,38.6
BEGIN DESCRIPTION:
Upstream Section of Bridge/Culvert/Weir
END DESCRIPTION:
XS GIS Cut Line= 6
      3113197.26     13850142.38      3113200.88     13848864.48
      3113510.77     13848567.96      3114025.51     13848091.94
      3114351.45     13847505.17      3114900.07     13845956.28
#Sta/Elev= 30
  3048.5    53.3  3053.2   53.28  4208.5    51.3  4238.5    49.6  4476.4    50.6
  4853.4   46.24  4870.3   43.69  4875.4   38.16  4919.1   20.36  4956.5   18.73
  4985.1    5.38  5003.4    3.18  5015.5    4.93  5040.9    17.7  5068.5   17.94
  5098.7   32.41  5111.9   41.57  5127.7   44.93  5586.4    42.9  5616.4      40
  5645.4   31.98  5666.4    29.5  5736.4    32.7  5766.4    41.8  5786.4    45.5
  5965.1   45.66  6157.6    45.5  6301.6   48.59  7487.6    51.3  7770.8    54.9
#Mann= 9 ,-1 , 0
  3048.5     .99       0  3053.2     .08       0  4853.4     .04       0
  4956.5    .015       0  5040.9     .04       0  5127.7     .12       0
  5645.4     .05       0  5965.1     .08       0  6301.6     .99       0
#XS Ineff= 2 , 0
       0 4829.69   47.85 5613.59       0    36.2
Permanent Ineff=
       F       F
Bank Sta=4853.4,5127.7
XS Rating Curve= 0 ,0
Exp/Cntr=0.5,0.3

Type RM Length L Ch R = 3 ,13909.5 ,,,
BEGIN DESCRIPTION:
UNION PAC. RR
Structure ID: E100-00-00-13
END DESCRIPTION:
Bridge Culvert--1,0,-1,-1, 0
Deck Dist Width WeirC Skew NumUp NumDn MinLoCord MaxHiCord MaxSubmerge Is_Ogee
10,9,2.6,0, 118, 118, , , 0.95, 0, ,,,
  3048.5  3053.2  3163.2  3238.5  3258.5  3328.5  3418.5  3438.5  3448.5  3453.2
  3503.2  3518.5  3538.5  3553.2  3568.5  3583.2  3598.5  3618.5  3673.2  3703.2
  3733.2  3763.2  3828.5  3848.5  3868.5  4208.5  4238.5  4258.5  4268.5  4278.5
  4288.5  4293.2    4835    4848  4853.4 4860.69  4860.8 4860.91  4870.3  4871.3
  4871.5  4875.4  4891.6    4904  4914.3  4919.1  4925.2  4935.4  4956.5  4985.1
  4992.8  4993.4  4995.5  4997.1  5003.4  5006.6  5007.4  5015.5  5040.9  5048.6
  5049.7  5060.9  5068.5    5071  5080.8  5087.5  5098.7  5110.3  5111.9  5121.5
 5123.89    5124  5127.7 5130.69  5130.8 5130.91  5171.2  5171.9  5222.9 5616.99
    5617    5762 5762.01  5826.1  5965.1  6066.1  6127.6  6157.6  6171.6  6267.6
  6301.6  6347.6  6541.6  6577.6  6591.6  6767.6  6851.6  6927.6  6981.6  7017.6
  7031.6  7077.6  7237.6  7331.6  7381.6  7421.6  7441.6  7467.6  7487.6  7491.6
  7661.6  7677.6  7707.6  7711.6  7721.6  7747.6  7749.8  7770.8
    53.3    53.6    53.2   52.94   52.87   53.21   52.51   52.25   52.22    52.2
   51.99   52.21   51.69    51.9   52.01   51.77   51.51   52.21   52.13   52.09
   52.05      52   51.93    51.9   52.11    51.5   51.46   51.44   51.43   51.42
   51.41    51.4   47.41    47.3   47.44   47.62   47.62   47.62   47.86   47.89
   47.71   47.69   47.62   47.57   47.53   47.51   47.48   47.46   47.41   47.35
   47.34   47.33   47.33   47.33   47.31   47.31   47.31   47.29   47.24   47.22
   47.22   47.21    47.2   47.19   47.18   47.18   47.16   47.15   47.14   47.06
   47.04   47.04      47   46.98   46.98   46.98   46.66   46.65   46.45   46.48
   46.48   46.48   46.48    46.5   46.21      46   45.81   45.65   45.89   48.51
    48.7   49.06    50.6   50.31   50.31   50.31   50.73   51.11    51.1   50.16
   50.05   50.51   50.76    51.3   51.67    52.3   52.12   52.37   52.73    52.8
      54   53.78   54.61    54.6   54.57   54.65    54.7    54.9
                                                                                
                                                                                
                                                                                
                                                                           44.89
   44.71   44.69   44.62   44.57   44.53   44.51   44.48   44.46   44.41   44.35
   44.34   44.33   44.33   44.33   44.31   44.31   44.31   44.29   44.24   44.22
   44.22   44.21    44.2   44.19   44.18   44.18   44.16   44.15
                                                                                
   43.48   43.48
                                                                                
                                                                                
                                                                
  3048.5  3053.2  3163.2  3238.5  3258.5  3328.5  3418.5  3438.5  3448.5  3453.2
  3503.2  3518.5  3538.5  3553.2  3568.5  3583.2  3598.5  3618.5  3673.2  3703.2
  3733.2  3763.2  3828.5  3848.5  3868.5  4208.5  4238.5  4258.5  4268.5  4278.5
  4288.5  4293.2    4835    4848  4853.4 4860.69  4860.8 4860.91  4870.3  4871.3
  4871.5  4875.4  4891.6    4904  4914.3  4919.1  4925.2  4935.4  4956.5  4985.1
  4992.8  4993.4  4995.5  4997.1  5003.4  5006.6  5007.4  5015.5  5040.9  5048.6
  5049.7  5060.9  5068.5    5071  5080.8  5087.5  5098.7  5110.3  5111.9  5121.5
 5123.89    5124  5127.7 5130.69  5130.8 5130.91  5171.2  5171.9  5222.9 5616.99
    5617    5762 5762.01  5826.1  5965.1  6066.1  6127.6  6157.6  6171.6  6267.6
  6301.6  6347.6  6541.6  6577.6  6591.6  6767.6  6851.6  6927.6  6981.6  7017.6
  7031.6  7077.6  7237.6  7331.6  7381.6  7421.6  7441.6  7467.6  7487.6  7491.6
  7661.6  7677.6  7707.6  7711.6  7721.6  7747.6  7749.8  7770.8
    53.3    53.6    53.2   52.94   52.87   53.21   52.51   52.25   52.22    52.2
   51.99   52.21   51.69    51.9   52.01   51.77   51.51   52.21   52.13   52.09
   52.05      52   51.93    51.9   52.11    51.5   51.46   51.44   51.43   51.42
   51.41    51.4   47.41    47.3   47.44   47.62   47.62   47.62   47.86   47.89
   47.71   47.69   47.62   47.57   47.53   47.51   47.48   47.46   47.41   47.35
   47.34   47.33   47.33   47.33   47.31   47.31   47.31   47.29   47.24   47.22
   47.22   47.21    47.2   47.19   47.18   47.18   47.16   47.15   47.14   47.06
   47.04   47.04      47   46.98   46.98   46.98   46.66   46.65   46.45   46.48
   46.48   46.48   46.48    46.5   46.21      46   45.81   45.65   45.89   48.51
    48.7   49.06    50.6   50.31   50.31   50.31   50.73   51.11    51.1   50.16
   50.05   50.51   50.76    51.3   51.67    52.3   52.12   52.37   52.73    52.8
      54   53.78   54.61    54.6   54.57   54.65    54.7    54.9
                                                                                
                                                                                
                                                                                
                                                                           44.89
   44.71   44.69   44.62   44.57   44.53   44.51   44.48   44.46   44.41   44.35
   44.34   44.33   44.33   44.33   44.31   44.31   44.31   44.29   44.24   44.22
   44.22   44.21    44.2   44.19   44.18   44.18   44.16   44.15
                                                                                
   43.48   43.48
                                                                                
                                                                                
                                                                
Pier Skew, UpSta & Num, DnSta & Num=  ,4873.5, 2 ,4873.5, 2 , 0 , 0 , 0 ,,
       1       1
   38.68    45.7
       1       1
   38.47   45.49
Pier Skew, UpSta & Num, DnSta & Num=  ,4891.7, 2 ,4891.7, 2 , 0 , 0 , 0 ,,
       1       1
   29.84   45.62
       1       1
   29.63   45.41
Pier Skew, UpSta & Num, DnSta & Num=  ,4912.3, 2 ,4912.3, 2 , 0 , 0 , 0 ,,
       1       1
   22.44   45.54
       1       1
   22.23   45.33
Pier Skew, UpSta & Num, DnSta & Num=  ,4932.8, 2 ,4932.8, 2 , 0 , 0 , 0 ,,
       1       1
   18.45   45.47
       1       1
   18.24   45.26
Pier Skew, UpSta & Num, DnSta & Num=  ,4952.5, 2 ,4952.5, 2 , 0 , 0 , 0 ,,
       1       1
   17.83   45.42
       1       1
   17.62   45.21
Pier Skew, UpSta & Num, DnSta & Num=  ,4971.6, 2 ,4971.6, 2 , 0 , 0 , 0 ,,
       1       1
   10.45   45.38
       1       1
   10.24   45.17
Pier Skew, UpSta & Num, DnSta & Num=  ,4991, 2 ,4991, 2 , 0 , 0 , 0 ,,
       1       1
    4.25   45.34
       1       1
    4.04   45.13
Pier Skew, UpSta & Num, DnSta & Num=  ,5011.7, 2 ,5011.7, 2 , 0 , 0 , 0 ,,
       1       1
    4.03    45.3
       1       1
    3.82   45.09
Pier Skew, UpSta & Num, DnSta & Num=  ,5030.5, 2 ,5030.5, 2 , 0 , 0 , 0 ,,
       1       1
   11.22   45.26
       1       1
   11.01   45.05
Pier Skew, UpSta & Num, DnSta & Num=  ,5050.8, 2 ,5050.8, 2 , 0 , 0 , 0 ,,
       1       1
   16.11   45.22
       1       1
    15.9   45.01
Pier Skew, UpSta & Num, DnSta & Num=  ,5071.4, 2 ,5071.4, 2 , 0 , 0 , 0 ,,
       1       1
    18.5   45.19
       1       1
   18.29   44.98
Pier Skew, UpSta & Num, DnSta & Num=  ,5091.3, 2 ,5091.3, 2 , 0 , 0 , 0 ,,
       1       1
   27.51   45.17
       1       1
    27.3   44.96
Pier Skew, UpSta & Num, DnSta & Num=  ,5108.7, 2 ,5108.7, 2 , 0 , 0 , 0 ,,
       1       1
      38   45.15
       1       1
   37.79   44.94
Pier Skew, UpSta & Num, DnSta & Num=  ,5649.5, 2 ,5649.5, 2 , 0 , 0 , 0 ,,
       4       4
       0      45
       4       4
       0      45
Pier Skew, UpSta & Num, DnSta & Num=  ,5689.5, 2 ,5689.5, 2 , 0 , 0 , 0 ,,
       4       4
       0      45
       4       4
       0      45
Pier Skew, UpSta & Num, DnSta & Num=  ,5729.5, 2 ,5729.5, 2 , 0 , 0 , 0 ,,
       4       4
       0      45
       4       4
       0      45
BR Coef= 1 , 1 , 0 ,1.25, 0 ,,,0.8,0,1.2,0,
WSPro=,,,, 1 ,,,, 0 ,,,, 0 ,,,,-1 ,-1 ,-1 , 0 , 0 , 0 , 0 , 0
BC Design=,, 0 ,, 0 ,,,,,,
BC HTab HWMax=54.9
BC Use User HTab Curves=0
BC User HTab FreeFlow(D)= 0

Type RM Length L Ch R = 1 ,13898.0 ,468.6,404,259.9
BEGIN DESCRIPTION:
Downstream Section of Bridge/Culvert/Weir
END DESCRIPTION:
XS GIS Cut Line= 6
      3113224.61     13850140.25      3113228.19     13848875.12
      3113528.68      13848587.6      3114046.75      13848108.5
      3114376.24     13847515.34       3114925.7     13845964.08
#Sta/Elev= 30
  3048.5    53.3  3053.2   53.28  4208.5    51.3  4238.5    49.6  4476.4    50.6
  4853.4   46.24  4870.3   43.46  4875.4   37.93  4919.1   20.13  4956.5    18.5
  4985.1    5.15  5003.4    2.95  5015.5     4.7  5040.9   17.47  5068.5   17.71
  5098.7   32.18  5111.9   41.34  5127.7   44.93  5586.4    42.9  5616.4      40
  5645.4   31.98  5666.4    29.5  5736.4    32.7  5766.4    41.8  5786.4    45.5
  5965.1   45.66  6157.6    45.5  6301.6   48.59  7487.6    51.3  7770.8    54.9
#Mann= 9 ,-1 , 0
  3048.5     .99       0  3053.2     .08       0  4853.4     .04       0
  4956.5    .015       0  5040.9     .04       0  5127.7     .12       0
  5645.4     .05       0  5965.1     .08       0  6301.6     .99       0
#XS Ineff= 2 , 0
       0 4838.43   46.36 5592.79       0    36.2
Permanent Ineff=
       F       F
Bank Sta=4853.4,5127.7
XS Rating Curve= 0 ,0
Exp/Cntr=0.5,0.3

Type RM Length L Ch R = 1 ,13494.  ,284,274,256.3
BEGIN DESCRIPTION:
Union Pacific RR5 - D/S - XS 1
END DESCRIPTION:
XS GIS Cut Line= 5
      3113723.26     13850221.42      3114108.88     13848660.81
      3114081.66     13848216.21      3114385.61     13847540.25
      3115010.59     13846012.19
#Sta/Elev= 30
  3201.1   52.92  4501.1   48.07  4838.6   39.97  4858.6   36.88 4894.98    23.3
    4934    18.9 4960.78    16.2 4984.36    4.79 5004.53    2.47    5046   15.98
  5118.6   28.41  5158.6   40.45  5198.6   52.95  5264.1   55.38  5304.1   54.45
  5444.1    42.7  5464.1   38.92  5504.1   25.52  5514.1   24.88  5574.1   27.46
  5594.1   30.58  5634.1    42.4  5704.1    46.4  6085.2   46.23  6315.2   50.26
  6475.2   46.58  6555.2    49.4  7025.2   49.85  7185.2   55.08  7646.2   54.63
#Mann= 7 ,-1 , 0
  3201.1     .08       0  4838.6     .04       0    4934    .015       0
    5046     .04       0  5118.6      .1       0  5444.1     .05       0
  6085.2     .08       0
#XS Ineff= 2 , 0
       0                 5428.42       0    36.2
Permanent Ineff=
       F       F
Bank Sta=4838.6,5158.6
XS Rating Curve= 0 ,0
Exp/Cntr=0.5,0.3

Type RM Length L Ch R = 1 ,13220.0 ,76,77,120.9
BEGIN DESCRIPTION:
Upstream Section of Bridge/Culvert/Weir
END DESCRIPTION:
XS GIS Cut Line= 6
      3113841.57     13852115.72      3114010.39     13850305.04
      3114389.31     13848551.63      3114349.65     13848350.26
      3114279.59     13847887.22      3115072.56     13845962.09
#Sta/Elev= 30
  1287.9   52.51  2657.9   50.41  2937.9   52.51  3326.4   50.61  3476.4   52.71
  4286.4   50.31  4406.4   48.91  4546.4   41.61  4829.6   39.05  4865.8   23.47
  4958.8   16.92  4984.2    4.38  5005.3    2.15  5007.8    4.25  5015.3    4.47
  5042.6   17.25  5189.8   23.61  5216.2   37.45  5495.6   28.71  5525.6   31.01
  5603.9   43.41  5663.9   46.21  5822.5   46.08  6043.9   46.21  6273.9   50.41
  6433.9   46.71  6513.9   49.41  6993.9   49.91  7143.8   55.01  7655.9   54.41
#Mann= 7 ,-1 , 0
  1287.9     .08       0  4829.6     .04       0  4958.8    .015       0
  5042.6     .04       0  5216.2     .05       0  5822.5     .08       0
  6043.9     .99       0
#XS Ineff= 2 , 0
       0 4802.62   39.25  5238.6       0    36.2
Permanent Ineff=
       F       F
Bank Sta=4829.6,5216.2
XS Rating Curve= 0 ,0
Exp/Cntr=0.5,0.3

Type RM Length L Ch R = 3 ,13182.5 ,,,
BEGIN DESCRIPTION:
STUDEMONT
Structure ID: E100-00-00-12
END DESCRIPTION:
Bridge Culvert--1,0,-1,-1, 0
Deck Dist Width WeirC Skew NumUp NumDn MinLoCord MaxHiCord MaxSubmerge Is_Ogee
10,55,2.6,0, 148, 148, , , 0.95, 0, ,,,
  1238.9  1287.9  1307.9  1327.9  1338.9  1388.9  1497.9  1608.9  1647.9  1657.9
  1658.9  1848.9  1878.9  1937.9  1938.9  1957.9  1977.9  1987.9  1988.9  1998.9
  2018.9  2258.9  2277.9  2288.9  2307.9  2308.9  2338.9  2358.9  2367.9  2488.9
  2498.9  2537.9  2578.9  2598.9  2607.9  2618.9  2627.9  2638.9  2657.9  2668.9
  2687.9  2698.9  2727.9  2747.9  2937.9  2958.9  2997.9  3106.4  3159.9  3276.4
  3289.9  3326.4  3336.4  3366.4  3416.4  3469.9  3476.4  3506.4  3609.9  3616.4
  3649.9  3656.4  3729.9  3846.4  3986.4  4019.9  4199.9  4286.4  4289.9  4316.4
  4366.4  4406.4  4476.4  4526.4  4546.4  4676.4  4705.6  4762.5  4805.6  4826.6
  4829.6  4831.1 4831.21  4831.3    4838  4838.1  4865.8  4912.9  4917.5  4958.8
  4984.2  4992.2  4994.7  5005.3  5007.8  5015.3  5020.7  5042.6  5094.4  5119.6
  5141.4  5189.8 5210.19  5210.3  5210.4  5214.9  5226.6  5268.5  5275.2  5317.3
  5325.6  5335.6  5355.2  5375.2  5375.6  5475.6  5485.2  5495.6  5505.2  5525.6
  5545.2  5553.9  5555.6  5573.8  5573.9  5583.9  5603.8  5603.9  5623.9  5663.9
  5693.9  5822.5  5913.9  5923.9  5933.9  5943.9  5963.9  6043.9  6053.9  6163.9
  6183.9  6193.9  6213.9  6223.9  6273.9  6433.9  6443.9  6463.9
    52.9   52.85   52.83   52.81    52.8    53.1    52.7    52.3   52.01   51.71
    51.7    52.1    51.8   52.19    52.2   51.93   52.01   51.61   51.61    51.6
    51.8    51.9   51.46    51.2   50.61   50.63   51.08    51.5   51.51   51.44
   51.43   51.41   51.47    51.5   51.51   50.96    50.5   50.47   50.41   50.81
   51.51   51.48   51.41   52.01   52.51   52.23   51.71   52.21   52.15   52.01
   51.63   50.61   50.81   52.41   51.91   52.62   52.71   52.11   51.92   51.91
   51.24   51.11    51.9   51.31    50.4   50.31   50.31   50.31   50.22   49.51
   49.51   48.91   45.94   45.03   44.67   42.33    41.8   41.34      41   41.22
   41.21    41.2    41.2    41.2    41.2    41.2    41.4   41.68   41.71   41.57
   41.48   41.46   41.45   41.41    41.4   41.38   41.36   41.27   41.05   40.94
   40.65   40.02   39.75   39.75   39.75   39.72    39.2   38.77    38.7   37.33
   37.06   36.74    36.1    35.2    35.2   34.29    34.2   34.62      35   36.38
    37.7    39.4   39.61    41.9   41.91   42.67    44.2    44.2    45.2   46.21
   46.19   46.08   46.01   45.86   45.71   45.76      46   46.21   46.46   49.21
   49.43   49.54   49.76   49.86   50.41   47.86   47.96   48.21
                                                                                
                                                                                
                                                                                
                                                                                
                                                                                
                                                                                
                                                                                
                                                                                
                                            36.8      37   37.28   37.31   37.17
   37.08   37.06   37.05   37.01      37   36.98   36.96   36.87   36.65   36.54
   36.25   35.62   35.35   34.35
                                                                                
                                                                                
                                                                                
                                                                
  1238.9  1287.9  1307.9  1327.9  1338.9  1388.9  1497.9  1608.9  1647.9  1657.9
  1658.9  1848.9  1878.9  1937.9  1938.9  1957.9  1977.9  1987.9  1988.9  1998.9
  2018.9  2258.9  2277.9  2288.9  2307.9  2308.9  2338.9  2358.9  2367.9  2488.9
  2498.9  2537.9  2578.9  2598.9  2607.9  2618.9  2627.9  2638.9  2657.9  2668.9
  2687.9  2698.9  2727.9  2747.9  2937.9  2958.9  2997.9  3106.4  3159.9  3276.4
  3289.9  3326.4  3336.4  3366.4  3416.4  3469.9  3476.4  3506.4  3609.9  3616.4
  3649.9  3656.4  3729.9  3846.4  3986.4  4019.9  4199.9  4286.4  4289.9  4316.4
  4366.4  4406.4  4476.4  4526.4  4546.4  4676.4  4705.6  4762.5  4805.6  4826.6
  4829.6  4831.1 4831.21  4831.3    4838  4838.1  4865.8  4912.9  4917.5  4958.8
  4984.2  4992.2  4994.7  5005.3  5007.8  5015.3  5020.7  5042.6  5094.4  5119.6
  5141.4  5189.8 5210.19  5210.3  5210.4  5214.9  5226.6  5268.5  5275.2  5317.3
  5325.6  5335.6  5355.2  5375.2  5375.6  5475.6  5485.2  5495.6  5505.2  5525.6
  5545.2  5553.9  5555.6  5573.8  5573.9  5583.9  5603.8  5603.9  5623.9  5663.9
  5693.9  5822.5  5913.9  5923.9  5933.9  5943.9  5963.9  6043.9  6053.9  6163.9
  6183.9  6193.9  6213.9  6223.9  6273.9  6433.9  6443.9  6463.9
    52.9   52.85   52.83   52.81    52.8    53.1    52.7    52.3   52.01   51.71
    51.7    52.1    51.8   52.19    52.2   51.93   52.01   51.61   51.61    51.6
    51.8    51.9   51.46    51.2   50.61   50.63   51.08    51.5   51.51   51.44
   51.43   51.41   51.47    51.5   51.51   50.96    50.5   50.47   50.41   50.81
   51.51   51.48   51.41   52.01   52.51   52.23   51.71   52.21   52.15   52.01
   51.63   50.61   50.81   52.41   51.91   52.62   52.71   52.11   51.92   51.91
   51.24   51.11    51.9   51.31    50.4   50.31   50.31   50.31   50.22   49.51
   49.51   48.91   45.94   45.03   44.67   42.33    41.8   41.34      41   41.22
   41.21    41.2    41.2    41.2    41.2    41.2    41.4   41.68   41.71   41.57
   41.48   41.46   41.45   41.41    41.4   41.38   41.36   41.27   41.05   40.94
   40.65   40.02   39.75   39.75   39.75   39.72    39.2   38.77    38.7   37.33
   37.06   36.74    36.1    35.2    35.2   34.29    34.2   34.62      35   36.38
    37.7    39.4   39.61    41.9   41.91   42.67    44.2    44.2    45.2   46.21
   46.19   46.08   46.01   45.86   45.71   45.76      46   46.21   46.46   49.21
   49.43   49.54   49.76   49.86   50.41   47.86   47.96   48.21
                                                                                
                                                                                
                                                                                
                                                                                
                                                                                
                                                                                
                                                                                
                                                                                
                                            36.8      37   37.28   37.31   37.17
   37.08   37.06   37.05   37.01      37   36.98   36.96   36.87   36.65   36.54
   36.25   35.62   35.35   34.35
                                                                                
                                                                                
                                                                                
                                                                
Pier Skew, UpSta & Num, DnSta & Num=  ,4869.2, 2 ,4869.2, 2 , 0 , 0 , 0 ,,
       3       3
    22.1   38.03
       3       3
   22.43   38.36
Pier Skew, UpSta & Num, DnSta & Num=  ,4919.9, 2 ,4919.9, 2 , 0 , 0 , 0 ,,
       3       3
   18.44   38.31
       3       3
   18.77   38.64
Pier Skew, UpSta & Num, DnSta & Num=  ,4969.9, 2 ,4969.9, 2 , 0 , 0 , 0 ,,
       3       3
    9.69   38.14
       3       3
   10.02   38.47
Pier Skew, UpSta & Num, DnSta & Num=  ,5021.2, 2 ,5021.2, 2 , 0 , 0 , 0 ,,
       3       3
    5.52   37.96
       3       3
    5.85   38.29
Pier Skew, UpSta & Num, DnSta & Num=  ,5071.7, 2 ,5071.7, 2 , 0 , 0 , 0 ,,
       3       3
   17.39   37.75
       3       3
   17.72   38.08
Pier Skew, UpSta & Num, DnSta & Num=  ,5122.2, 2 ,5122.2, 2 , 0 , 0 , 0 ,,
       3       3
   19.29   37.53
       3       3
   19.62   37.86
Pier Skew, UpSta & Num, DnSta & Num=  ,5172.7, 2 ,5172.7, 2 , 0 , 0 , 0 ,,
       3       3
    21.6   36.86
       3       3
   21.93   37.19
BR Coef= 1 , 1 , 0 ,1.25, 0 ,,,0.8,0,1.2,0,
WSPro=,,,, 1 ,,,, 0 ,,,, 0 ,,,,-1 ,-1 ,-1 , 0 , 0 , 0 , 0 , 0
BC Design=,, 0 ,, 0 ,,,,,,
BC HTab HWMax=55.31
BC Use User HTab Curves=0
BC User HTab FreeFlow(D)= 0

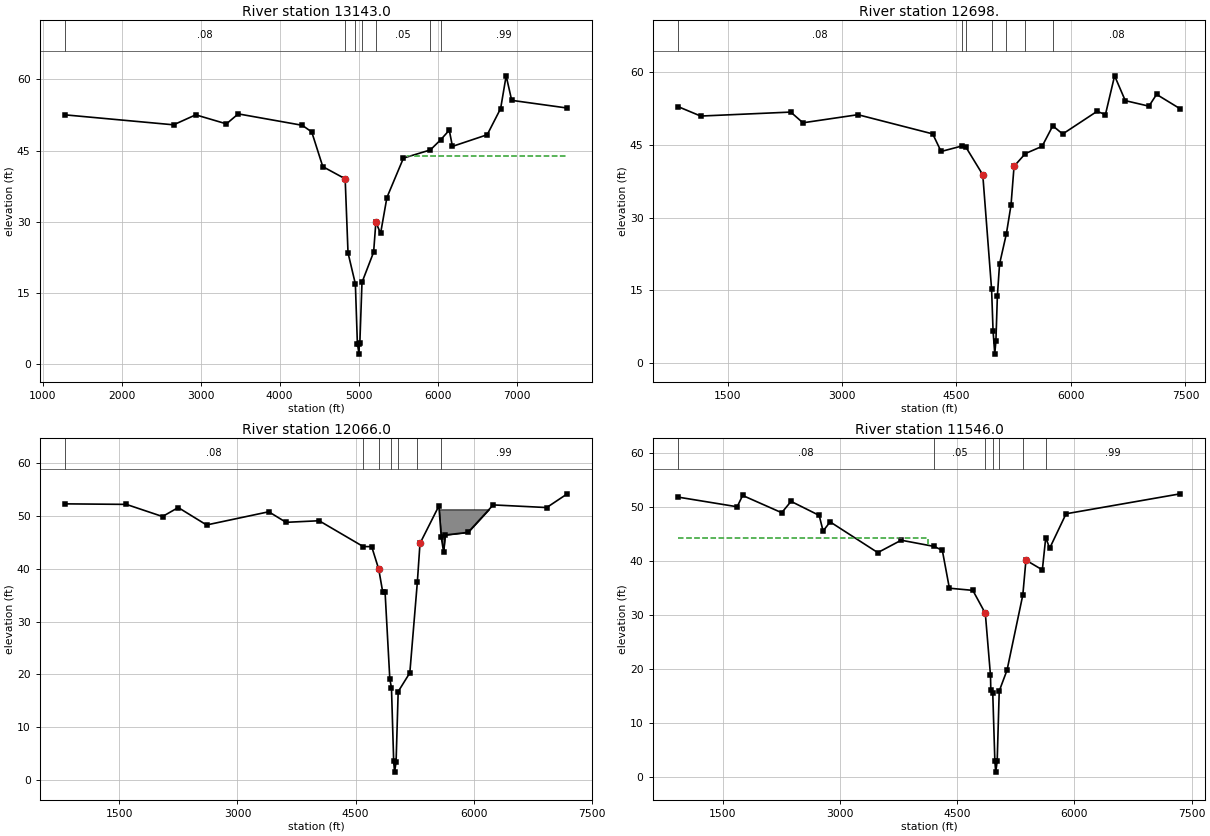
Type RM Length L Ch R = 1 ,13143.0 ,474.9,445,235.2
BEGIN DESCRIPTION:
Downstream Section of Bridge/Culvert/Weir
END DESCRIPTION:
XS GIS Cut Line= 6
      3113917.43     13852107.01      3114086.09     13850298.12
      3114465.93     13848540.41       3114425.2     13848333.61
      3114356.48     13847879.46      3115146.28     13845962.02
#Sta/Elev= 30
  1282.3   52.51  2657.9   50.41  2937.9   52.51  3326.4   50.61  3476.4   52.71
  4286.4   50.31  4406.4   48.91  4546.4   41.61  4829.6   39.05  4865.8   23.47
  4958.8   16.92  4984.2    4.38  5005.3    2.15  5007.8    4.25  5015.3    4.47
  5042.6   17.25  5189.8   23.61  5218.1    29.9  5278.1   27.57  5358.1   35.11
  5567.4   43.41  5907.4   45.12  6037.4   47.24  6147.4   49.28  6187.4   45.87
  6627.4   48.32  6797.4   53.83  6867.4   60.72  6937.4   55.56  7641.1   53.94
#Mann= 7 ,-1 , 0
  1282.3     .08       0  4829.6     .04       0  4958.8    .015       0
  5042.6     .04       0  5218.1     .05       0  5907.4     .08       0
  6037.4     .99       0
#XS Ineff= 2 , 0
       0 4790.39   39.25 5612.79       0   43.84
Permanent Ineff=
       F       F
Bank Sta=4829.6,5218.1
XS Rating Curve= 0 ,0
Exp/Cntr=0.5,0.3

Type RM Length L Ch R = 1 ,12698.  ,515.8,632,800.1
BEGIN DESCRIPTION:
Studemont - D/S - XS 1
END DESCRIPTION:
XS GIS Cut Line= 4
      3114005.16     13852039.09      3114852.89     13848257.04
      3114426.44     13847853.28      3115234.01      13845894.1
#Sta/Elev= 30
   848.4   52.96  1148.4   50.99  2328.4   51.81  2488.4    49.6  3208.4   51.27
  4188.4   47.31  4298.4   43.68  4578.4   44.84  4618.4    44.7  4844.3   38.88
    4960   15.23 4979.21    6.68 5001.54    1.87 5016.75    4.68 5035.75   13.89
  5064.3   20.46  5154.3   26.75  5214.3   32.61  5254.3   40.62    5402   43.25
  5621.6   44.74  5761.6   48.97  5891.6   47.29  6341.6   51.96  6451.6    51.3
  6571.6   59.29  6711.6   54.17  7021.6   53.03  7121.6   55.46  7430.7   52.49
#Mann= 7 ,-1 , 0
   848.4     .08       0  4578.4     .05       0  4618.4     .04       0
    4960    .015       0  5154.3     .04       0    5402     .05       0
  5761.6     .08       0
Bank Sta=4844.3,5254.3
XS Rating Curve= 0 ,0
Exp/Cntr=0.3,0.1

Type RM Length L Ch R = 1 ,12066.0 ,532.8,520,490.4
BEGIN DESCRIPTION:
Cross Section E100-00-00-X08
END DESCRIPTION:
XS GIS Cut Line= 6
      3114194.98     13852246.38      3114789.05     13848908.28
      3114950.43     13848635.11       3115322.5      13847933.9
      3115349.17     13846260.18      3115349.64     13846052.64
#Sta/Elev= 30
   807.8    52.3  1587.8    52.2  2047.8    49.9  2247.8    51.6  2607.8    48.3
  3397.8    50.8  3617.8    48.8  4037.8    49.1  4599.1    44.2  4705.6    44.2
  4795.6    39.9  4845.6    35.6  4875.9   35.54  4936.3   19.05  4956.9   17.49
    4985    3.56  4996.2    1.47  5015.6    3.37  5042.3   16.73  5190.2   20.28
  5285.5   37.41  5319.4    44.8  5559.4    51.9  5589.4      46  5619.4    43.2
  5639.4    46.4  5929.4    46.9  6249.4    52.1  6929.4    51.6  7190.9    54.2
#Mann= 7 ,-1 , 0
   807.8     .08       0  4599.1     .05       0  4795.6     .04       0
  4956.9    .015       0  5042.3     .04       0  5285.5     .05       0
  5589.4     .99       0
#Block Obstruct= 1 ,-1
  5547.6  6239.3   51.25
Bank Sta=4795.6,5319.4
XS Rating Curve= 0 ,0
Exp/Cntr=0.3,0.1

Type RM Length L Ch R = 1 ,11546.0 ,582.1,525,460.4
BEGIN DESCRIPTION:
Cross Section E100-00-00-X07
END DESCRIPTION:
XS GIS Cut Line= 4
      3114322.28     13852246.38      3115351.09     13849209.29
      3115876.74     13847832.76      3116192.54     13846110.77
#Sta/Elev= 30
   922.5    51.9  1682.5    50.1  1752.5    52.2  2252.5      49  2372.5    51.1
  2732.5    48.5  2782.5    45.6  2872.5    47.3  3482.5    41.6  3782.5    43.9
  4206.9   42.74  4309.1      42  4399.1      35  4699.1    34.6  4859.1   30.34
  4925.2   18.84  4929.6   16.11  4954.4   15.51  4981.2    2.95  4992.2      .9
    5011    2.92  5037.2   15.94  5136.9    19.8  5339.1   33.75  5379.1    40.2
  5589.1    38.4  5632.6    44.4  5682.6    42.4  5892.6    48.8  7353.3    52.5
#Mann= 7 ,-1 , 0
   922.5     .08       0  4206.9     .05       0  4859.1     .04       0
  4954.4    .015       0  5037.2     .04       0  5339.1     .05       0
  5632.6     .99       0
#XS Ineff= 2 , 0
         4128.87   44.26
Permanent Ineff=
       F       F
Bank Sta=4859.1,5379.1
XS Rating Curve= 0 ,0
Exp/Cntr=0.3,0.1