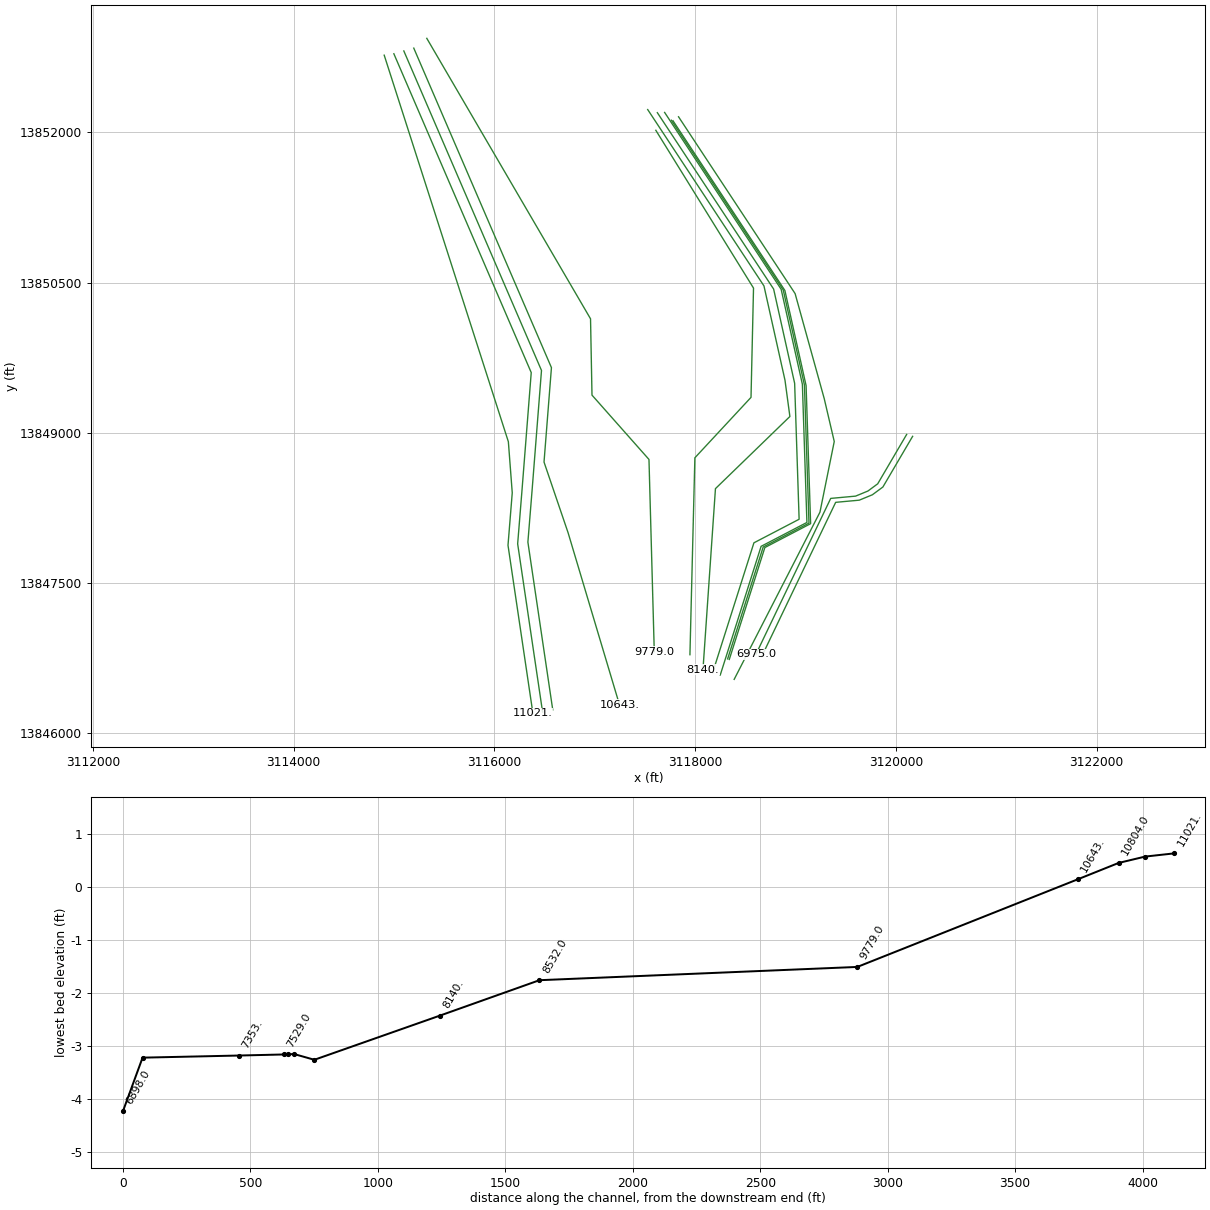
HEC-RAS study E100-00-00.prj: E100-00-00

--- E100-00-00.g02 (geometry) --- (continued)

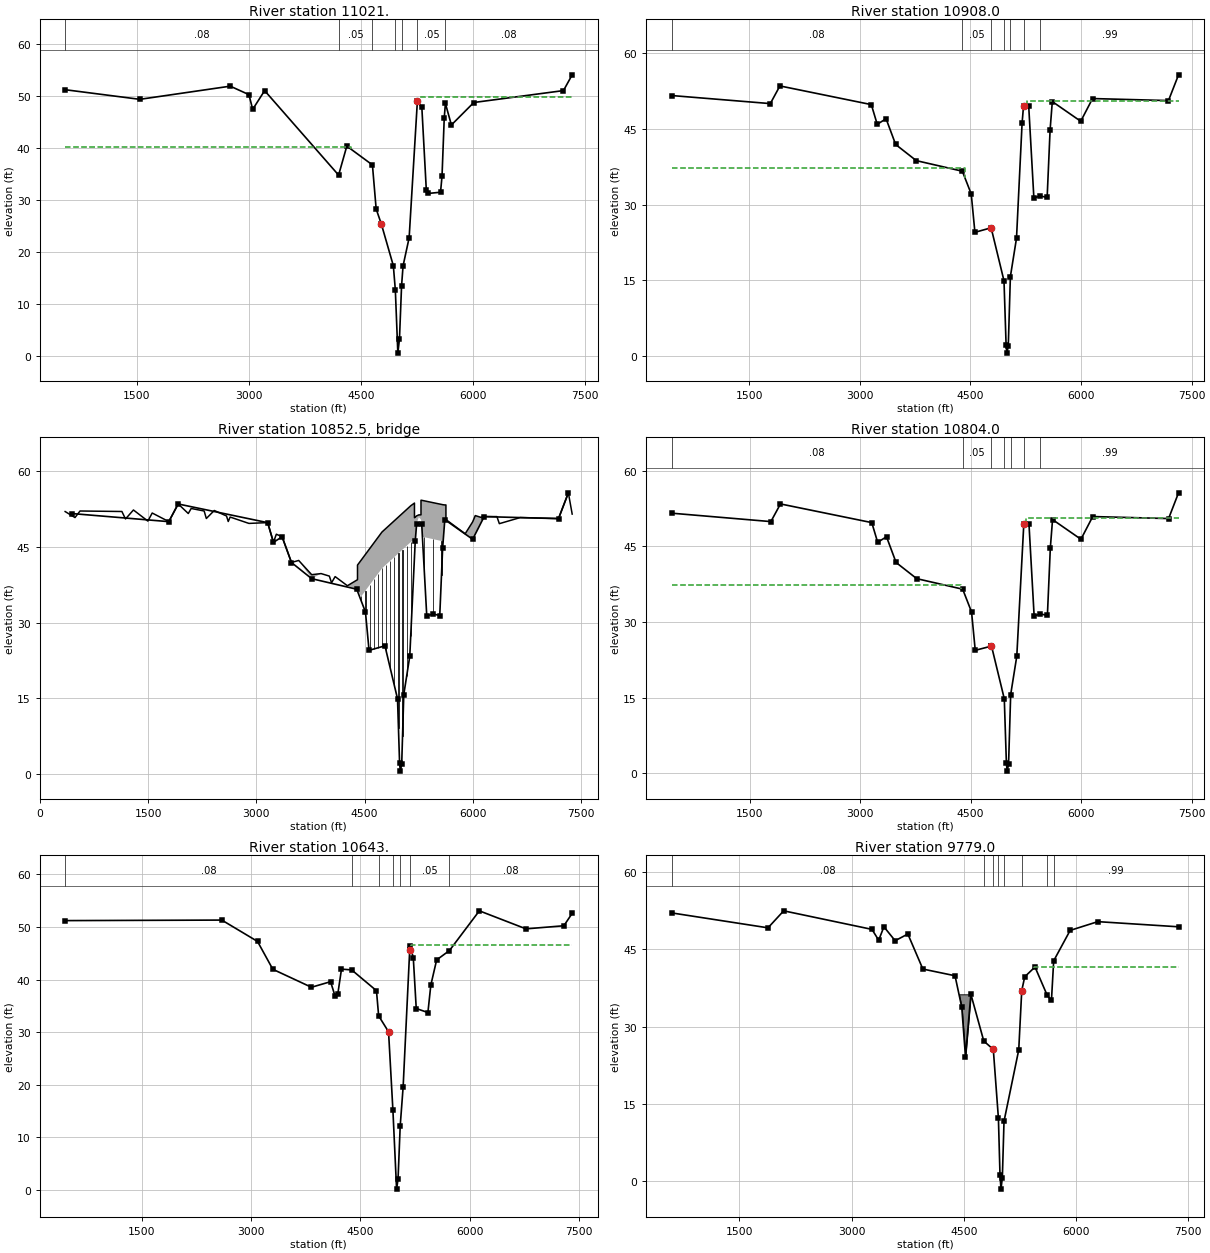
Type RM Length L Ch R = 1 ,11021.  ,146.3,113,104.7
BEGIN DESCRIPTION:
Taylor (Sawyer/Watson) - U/S - XS 4
-Left bank changed from 4654.4 to 4774.4 to maintain bank width consistency.  Manning's n-values were not modified (PBS&J June 2009).
END DESCRIPTION:
XS GIS Cut Line= 5
       3114902.2     13852771.34      3116139.19     13848912.01
      3116177.88      13848402.1      3116135.55     13847878.27
       3116383.8     13846199.97
#Sta/Elev= 30
   541.7   51.27  1541.7   49.42  2751.7   51.95  3001.7   50.32  3051.7   47.49
  3211.7   51.09  4201.7   34.85  4311.7   40.43  4654.4   36.81  4704.4   28.34
  4774.4   25.42  4934.4   17.43 4961.04   12.78 4994.67     .63 5016.39    3.36
  5044.4   13.55  5064.4    17.4  5145.8   22.81  5255.8   49.01  5315.8   47.88
  5375.8   31.95  5395.8   31.32  5565.8   31.56  5585.8    34.6  5615.8    45.9
  5631.3   48.63  5711.3   44.49  6011.3   48.81  7211.3    51.1  7327.9   54.13
#Mann= 7 ,-1 , 0
   541.7     .08       0  4201.7     .05       0  4654.4     .04       0
 4961.04    .015       0  5044.4     .04       0  5255.8     .05       0
  5631.3     .08       0
#XS Ineff= 2 , 0
       0    4363   40.27  5279.3       0   49.96
Permanent Ineff=
       F       F
Bank Sta=4774.4,5255.8
XS Rating Curve= 0 ,0
Exp/Cntr=0.5,0.3

Type RM Length L Ch R = 1 ,10908.0 ,102.3,104,104.6
BEGIN DESCRIPTION:
Upstream Section of Bridge/Culvert/Weir
-Left bank changed from 4482.1 to 4782.1 to maintain bank width consistency.  Manning's n-values were not modified (PBS&J June 2009).
END DESCRIPTION:
XS GIS Cut Line= 5
      3114998.42     13852785.49      3116367.02     13849602.35
       3116274.1     13848416.25      3116231.77     13847892.42
      3116480.02     13846214.12
#Sta/Elev= 30
   447.1    51.6  1787.2      50  1917.2    53.5  3157.2    49.8  3237.2    45.9
  3357.2      47  3487.2    41.9  3767.2    38.7  4391.5   36.61  4512.1    32.1
  4562.1    24.5  4782.1    25.4  4956.5    14.9    4985     2.2  4995.2     .57
  5014.5    1.94  5043.2   15.73  5126.2   23.33  5201.8    46.1  5221.8    49.6
  5291.8    49.5  5361.8    31.3  5446.7   31.72  5541.8    31.4  5581.8    44.8
  5611.8    50.4  5997.4    46.5  6157.4      51  7187.4    50.6  7323.8    55.7
#Mann= 7 ,-1 , 0
   447.1     .08       0  4391.5     .05       0  4782.1     .04       0
  4956.5    .015       0  5043.2     .04       0  5221.8     .05       0
  5446.7     .99       0
#XS Ineff= 2 , 0
       0    4428    37.3 5264.65       0   50.51
Permanent Ineff=
       F       F
Bank Sta=4782.1,5221.8
XS Rating Curve= 0 ,0
Exp/Cntr=0.5,0.3

Type RM Length L Ch R = 3 ,10852.5 ,,,
BEGIN DESCRIPTION:
TAYLOR (SAWYER/WATSON)  E100-00-00-11
Structure ID: E100-00-00-11
END DESCRIPTION:
Bridge Culvert--1,0,-1,-1, 0
Deck Dist Width WeirC Skew NumUp NumDn MinLoCord MaxHiCord MaxSubmerge Is_Ogee
10,91,2.6,0, 60, 60, , , 0.95, 0, ,,,
   350.8   487.2   557.2  1137.2  1187.2  1297.2  1497.2  1557.2  1787.2  1917.2
  2057.2  2097.2  2277.2  2307.2  2417.2  2587.2  2610.8  2637.2  2897.2  3157.2
  3237.2  3277.2  3357.2  3487.2  3587.2  3767.2  3897.2  4012.1  4042.1  4092.1
    4262 4401.99  4402.1  4452.1  4740.8    5140  5191.3 5191.41  5204.7  5221.8
  5251.8  5281.7  5281.8  5301.8  5311.8    5587  5611.8  5627.4  5627.5    5894
  5997.4    6034  6107.4  6157.4    6334  6367.4  6657.4  7187.4  7323.9  7376.7
      52   50.81   52.11   52.01   50.53   52.31   50.11   51.71   50.01   53.51
   51.61   52.61   52.11   50.62   52.21   51.12   50.03   50.91   49.65   49.81
   45.91   47.51   47.01   41.91   42.31   39.49   39.71   39.21   37.89   39.11
    37.3    38.5    41.4   42.36   47.94   53.15   53.68   50.78   50.94   51.15
   51.34   51.35   54.25    54.2   54.17   53.35   53.31   53.31   50.41    47.6
   49.95    51.2   50.87   51.01      51    49.6   50.81   50.61   55.71    51.5
      52    50.8    52.1      52    50.2    52.3    50.1    51.7      50    53.5
    51.6    52.6    52.1    50.5    52.2    49.8   50.02    50.9    49.1    49.8
    45.9    47.5      47    41.9    42.3    38.7    39.7    39.2    37.7    39.1
    37.3   36.55   36.55   35.16   40.74   45.95   46.48   46.48   46.64    49.6
    50.9    50.4    50.4   47.05   46.97    46.1    50.4    50.4    50.3   47.59
    46.5   47.45    48.1      51   50.71    49.4    50.8    50.6    55.7    51.5
   350.8   487.2   557.2  1137.2  1190.8  1297.2  1457.2  1497.2  1557.2  1787.2
  1917.2  2057.2  2097.2  2277.2  2307.2  2417.2  2590.8  2610.8  2637.2  2840.8
  2940.8  3157.2  3237.2  3277.2  3357.2  3487.2  3587.2  3767.2  4012.1  4042.1
  4092.1    4262 4401.99  4402.1 4439.11  4439.2  4740.8  5089.4  5191.3 5191.41
  5204.7  5221.8  5281.7  5281.8  5291.8  5301.8 5586.89    5587  5627.4  5627.5
    5894    6034    6334    6364  6657.4  7187.4  7217.4  7247.4  7323.9  7376.7
      52   50.81   52.11   52.01    50.4   52.31   51.41   50.11   51.71   50.01
   53.51   51.61   52.61   52.11   50.62   52.21    51.1   50.03   50.91    50.5
   49.23   49.81   45.91   47.51   47.01   41.91   42.31   39.49   39.21   37.89
   39.11    37.3    38.5    41.4   42.11   42.11   47.94   52.59   53.68   50.78
   50.94   51.15   51.35   54.25   54.23    54.2   53.35   53.35   53.31   50.41
    47.6    51.2      51    49.6   50.81   50.61   50.91   53.51   55.71    51.5
                                                                                
                                                                                
                                                                                
                                           35.01   40.74   45.39   46.48   46.48
   46.64                                   47.05   46.15
                                                                                
Pier Skew, UpSta & Num, DnSta & Num=  ,4456.1, 2 ,4456.1, 2 , 0 , 0 , 0 ,,
     2.5     2.5
   33.25   36.26
     2.5     2.5
   33.15   36.16
Pier Skew, UpSta & Num, DnSta & Num=  ,4513.1, 2 ,4513.1, 2 , 0 , 0 , 0 ,,
     2.5     2.5
   30.74   37.37
     2.5     2.5
   30.64   37.27
Pier Skew, UpSta & Num, DnSta & Num=  ,4570.1, 2 ,4570.1, 2 , 0 , 0 , 0 ,,
     2.5     2.5
   23.35   38.47
     2.5     2.5
   23.25   38.37
Pier Skew, UpSta & Num, DnSta & Num=  ,4627.1, 2 ,4627.1, 2 , 0 , 0 , 0 ,,
     2.5     2.5
   22.42   39.57
     2.5     2.5
   22.32   39.47
Pier Skew, UpSta & Num, DnSta & Num=  ,4684.1, 2 ,4684.1, 2 , 0 , 0 , 0 ,,
     2.5     2.5
   22.77   40.67
     2.5     2.5
   22.67   40.57
Pier Skew, UpSta & Num, DnSta & Num=  ,4741.1, 2 ,4741.1, 2 , 0 , 0 , 0 ,,
     2.5     2.5
   23.57   41.76
     2.5     2.5
   23.47   41.66
Pier Skew, UpSta & Num, DnSta & Num=  ,4798.1, 2 ,4798.1, 2 , 0 , 0 , 0 ,,
     2.5     2.5
   22.85   42.56
     2.5     2.5
   22.75   42.46
Pier Skew, UpSta & Num, DnSta & Num=  ,4855.1, 2 ,4855.1, 2 , 0 , 0 , 0 ,,
     2.5     2.5
   19.08   43.48
     2.5     2.5
   18.98   43.38
Pier Skew, UpSta & Num, DnSta & Num=  ,4912.2, 2 ,4912.2, 2 , 0 , 0 , 0 ,,
     2.5     2.5
   16.31   44.18
     2.5     2.5
   16.21   44.08
Pier Skew, UpSta & Num, DnSta & Num=  ,4969.4, 2 ,4969.4, 2 , 0 , 0 , 0 ,,
     2.5     2.5
    7.59   44.96
     2.5     2.5
    7.49   44.86
Pier Skew, UpSta & Num, DnSta & Num=  ,5026.2, 2 ,5026.2, 2 , 0 , 0 , 0 ,,
     2.5     2.5
    5.96   45.66
     2.5     2.5
    5.86   45.56
Pier Skew, UpSta & Num, DnSta & Num=  ,5082.8, 2 ,5082.8, 2 , 0 , 0 , 0 ,,
     2.5     2.5
   18.69   46.33
     2.5     2.5
   18.59   46.23
Pier Skew, UpSta & Num, DnSta & Num=  ,5139.7, 2 ,5139.7, 2 , 0 , 0 , 0 ,,
     2.5     2.5
   25.66   46.96
     2.5     2.5
   25.56   46.86
Pier Skew, UpSta & Num, DnSta & Num=  ,5326, 2 ,5326, 2 , 0 , 0 , 0 ,,
       4       4
   38.22   47.93
       4       4
   38.12   47.83
Pier Skew, UpSta & Num, DnSta & Num=  ,5446, 2 ,5446, 2 , 0 , 0 , 0 ,,
       4       4
   30.71   47.58
       4       4
   30.61   47.48
Pier Skew, UpSta & Num, DnSta & Num=  ,5566, 2 ,5566, 2 , 0 , 0 , 0 ,,
       4       4
   37.03   47.22
       4       4
   36.93   47.12
BR Coef= 1 , 1 , 0 ,1.25, 0 ,,,0.8,0,1.2,0,
WSPro=,,,, 1 ,,,, 0 ,,,, 0 ,,,,-1 ,-1 ,-1 , 0 , 0 , 0 , 0 , 0
BC Design=,, 0 ,, 0 ,,,,,,
BC HTab HWMax=55.7
BC Use User HTab Curves=0
BC User HTab FreeFlow(D)= 0

Type RM Length L Ch R = 1 ,10804.0 ,99.3,161,212.2
BEGIN DESCRIPTION:
Downstream Section of Bridge/Culvert/Weir
-Left bank changed from 4482.1 to 4772.1 to maintain bank width consistency.  Manning's n-values were not modified (PBS&J June 2009).
END DESCRIPTION:
XS GIS Cut Line= 5
      3115097.73     13852813.55      3116469.25      13849623.6
      3116375.75     13848430.09       3116333.7     13847909.64
      3116581.44     13846234.73
#Sta/Elev= 30
   437.8   51.55  1787.2   49.88  1917.2   53.38  3157.2   49.68  3237.2   45.78
  3357.2   46.88  3487.2   41.78  3767.2   38.58  4391.5   36.49  4512.1   31.98
  4562.1   24.38  4772.1   25.18  4782.1   25.28  4956.5   14.78    4985    2.08
  4995.2     .45  5014.5    1.82  5043.2   15.61  5126.2   23.21  5221.8   49.48
  5291.8   49.38  5361.8   31.18  5446.7    31.6  5541.8   31.28  5581.8   44.68
  5611.8   50.28  5997.4   46.38  6157.4   50.88  7187.4   50.48  7322.6   55.58
#Mann= 7 ,-1 , 0
   437.8     .08       0  4391.5     .05       0  4782.1     .04       0
  4956.5    .015       0  5043.2     .04       0  5221.8     .05       0
  5446.7     .99       0
#XS Ineff= 2 , 0
       0  4373.8    37.3 5250.44       0   50.51
Permanent Ineff=
       F       F
Bank Sta=4772.1,5221.8
XS Rating Curve= 0 ,0
Exp/Cntr=0.5,0.3

Type RM Length L Ch R = 1 ,10643.  ,778.3,864,945.3
BEGIN DESCRIPTION:
Taylor (Sawyer/Watson) - D/S - XS 1
END DESCRIPTION:
XS GIS Cut Line= 5
      3115196.78     13852841.85       3116568.3      13849651.9
      3116494.43     13848708.93      3116734.43     13848002.69
      3117246.94     13846283.44
#Sta/Elev= 30
     447   51.22    2597   51.32    3087   47.26    3297   41.96    3827   38.54
  4089.3    39.6  4149.3   36.95  4189.3    37.3  4239.3   41.99  4379.3   41.84
  4719.3   37.89  4749.3    33.1  4885.2   30.07  4945.2    15.1 4995.47     .14
 5015.45    2.04  5045.2    12.2  5085.2   19.55  5175.2   45.54  5185.2   46.47
  5225.2   44.04  5265.2    34.5  5425.2   33.73  5465.2   38.95  5545.2   43.74
  5721.1   45.53  6131.1   53.08  6771.1   49.65  7291.1   50.24  7405.1    52.6
#Mann= 7 ,-1 , 0
     447     .08       0  4379.3     .05       0  4749.3     .04       0
  4945.2    .015       0  5045.2     .04       0  5185.2     .05       0
  5721.1     .08       0
#XS Ineff= 2 , 0
       0                    5188       0  46.632
Permanent Ineff=
       F       F
Bank Sta=4885.2,5175.2
XS Rating Curve= 0 ,0
Exp/Cntr=0.3,0.1

Type RM Length L Ch R = 1 ,9779.0  ,1492.6,1247,918.7
BEGIN DESCRIPTION:
Cross Section E100-00-00-X06
Located At: 2ND US HOUSTON RD
END DESCRIPTION:
XS GIS Cut Line= 5
      3115326.54     13852939.45      3116957.82     13850139.21
      3116972.33     13849377.36      3117539.99     13848735.15
       3117592.8     13846816.49
#Sta/Elev= 30
   591.6    52.1  1881.6    49.2  2091.6    52.5  3271.6    48.9  3361.6    46.8
  3431.6    49.4  3581.6    46.7  3751.6      48  3952.3    41.2  4382.3    39.9
  4472.3    33.8  4522.3    24.2  4594.3    36.3  4766.8   27.23  4894.2    25.6
  4962.5   12.23  4983.6    1.26  4996.9   -1.51  5015.1     .72  5037.4   11.66
  5234.2   25.51  5274.3      37  5314.3    39.7  5451.5    41.6  5615.9   36.07
  5671.5    35.1  5701.5    42.8  5921.5    48.7  6291.5    50.4  7370.8    49.4
#Mann= 8 ,-1 , 0
   591.6     .08       0  4766.8     .05       0  4894.2     .04       0
  4962.5    .015       0  5037.4     .04       0  5274.3     .12       0
  5615.9     .08       0  5701.5     .99       0
#XS Ineff= 2 , 0
                         5441.91           41.62
Permanent Ineff=
       F       F
#Block Obstruct= 1 ,-1
  4432.3  4594.3    36.3
Bank Sta=4894.2,5274.3
XS Rating Curve= 0 ,0
Exp/Cntr=0.3,0.1

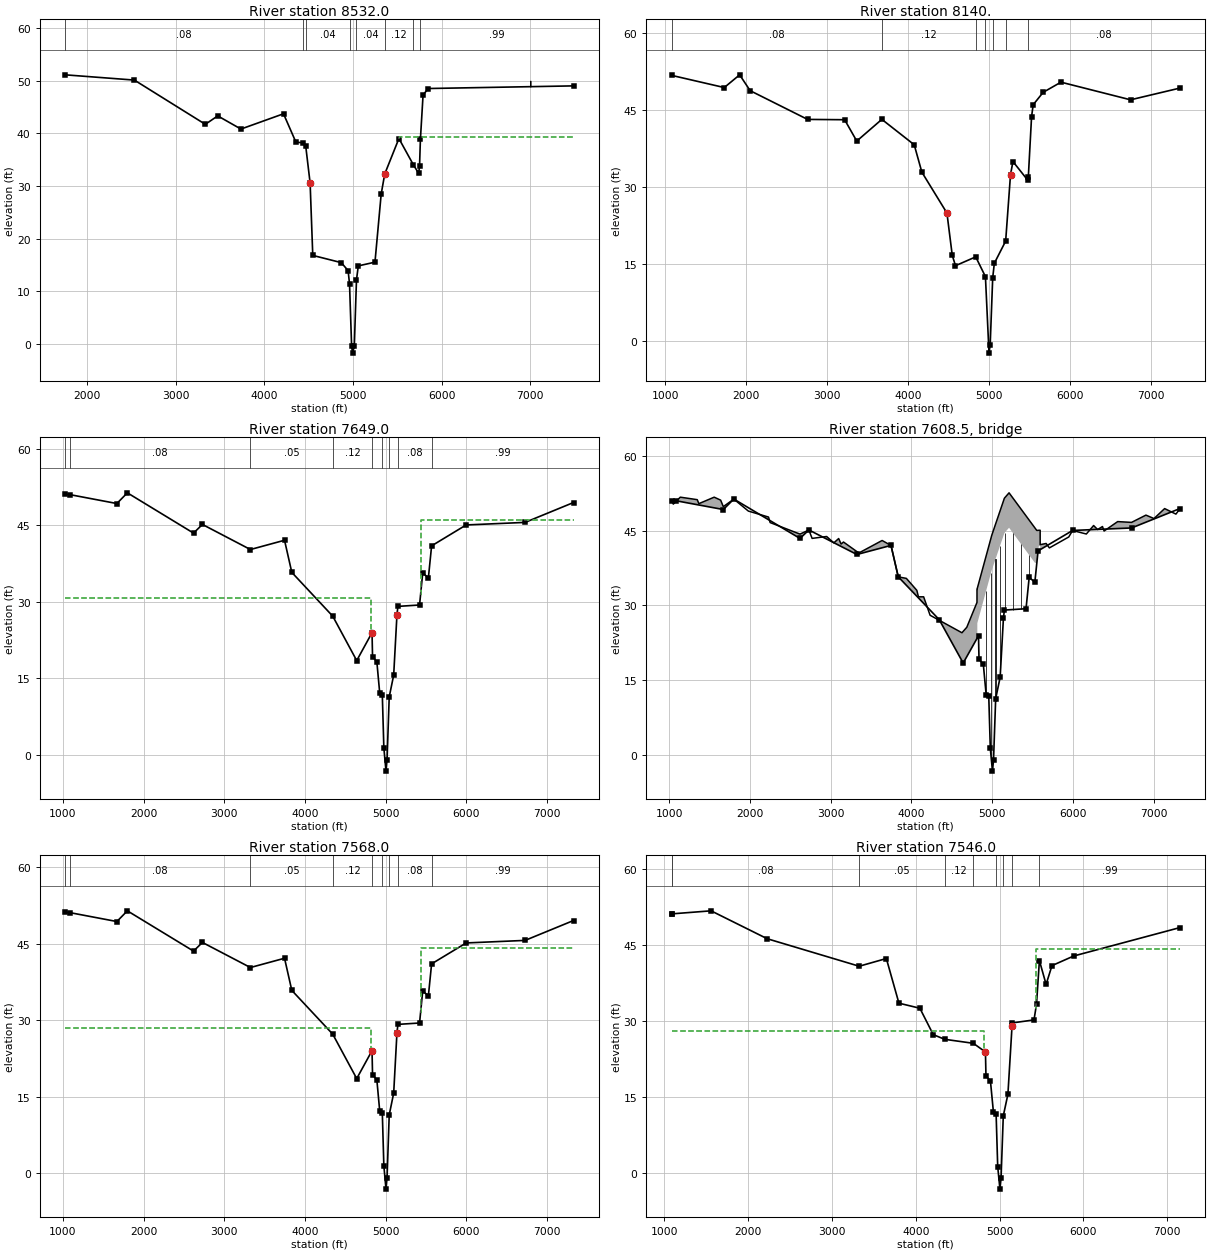
Type RM Length L Ch R = 1 ,8532.0  ,420.6,392,382.8
BEGIN DESCRIPTION:
Cross Section E100-00-00-X05
Located At: US HOUSTON RD
END DESCRIPTION:
XS GIS Cut Line= 5
      3117608.25      13852021.3      3118581.53     13850445.95
      3118556.56      13849354.8       3117997.3     13848751.65
      3117948.03      13846785.6
#Sta/Elev= 30
  1755.2    51.1  2535.2    50.1  3335.2    41.7  3475.2    43.3    3737    40.8
    4217    43.7    4357    38.3  4435.4    38.2  4466.9   37.66    4517   30.55
    4547    16.8  4868.4   15.43  4945.5   13.91  4961.4    11.4  4984.9    -.37
  4995.1   -1.76  5015.3    -.42    5040   12.18  5060.5   14.81  5248.4   15.52
  5318.4   28.45  5358.4   32.26  5518.4      39  5682.8   33.97  5740.9    32.4
  5750.9    33.7  5760.9    38.9  5790.9    47.3  5850.9    48.5  7487.6      49
#Mann= 8 ,-1 , 0
  1755.2     .08       0  4435.4     .12       0  4466.9     .04       0
  4961.4    .015       0    5040     .04       0  5358.4     .12       0
  5682.8     .08       0  5760.9     .99       0
#XS Ineff= 2 , 0
       0                 5518.37       0    39.3
Permanent Ineff=
       F       F
#Block Obstruct= 1 ,-1
    7000    7001      50
Bank Sta=4517,5358.4
XS Rating Curve= 0 ,0
Exp/Cntr=0.3,0.1

Type RM Length L Ch R = 1 ,8140.   ,185.6,491,632
BEGIN DESCRIPTION:
Houston Ave. - U/S - XS 4
END DESCRIPTION:
XS GIS Cut Line= 6
      3117527.24     13852228.33      3118685.58     13850467.65
      3118895.04     13849526.32      3118943.83     13849163.87
      3118202.33     13848443.76      3118077.97     13846637.04
#Sta/Elev= 30
  1077.4    51.7  1727.4   49.33  1917.4   51.81  2047.4   48.72  2757.4   43.12
  3214.9   43.06  3364.9    38.9  3674.9   43.13  4074.9   38.18  4169.3   32.84
  4479.3   24.87    4545   16.63    4585   14.61    4835   16.33    4955   12.48
 4999.23   -2.43 5013.81    -.76    5045   12.27    5065   15.08    5205   19.41
    5265   32.36    5295   34.91    5475   31.33    5485   31.87    5525   43.61
    5545   45.98  5668.6    48.4  5888.6   50.38  6748.6   46.94  7359.6   49.23
#Mann= 7 ,-1 , 0
  1077.4     .08       0  3674.9     .12       0    4835     .04       0
    4955    .015       0    5045     .04       0    5205     .05       0
    5475     .08       0
Bank Sta=4479.3,5265
XS Rating Curve= 0 ,0
Exp/Cntr=0.5,0.3

Type RM Length L Ch R = 1 ,7649.0  ,80,81,82.9
BEGIN DESCRIPTION:
Upstream Section of Bridge/Culvert/Weir
END DESCRIPTION:
XS GIS Cut Line= 6
      3117623.46      13852197.2       3118781.8     13850436.52
      3118991.26      13849495.2       3119035.8     13848138.11
      3118585.54     13847902.75      3118174.19     13846605.91
#Sta/Elev= 30
  1029.7   51.02  1086.6   50.97  1669.7   49.22  1799.7   51.32  2619.7   43.42
  2729.7   45.12  3324.5    40.2  3747.2   42.02  3837.2   35.72  4344.5   27.13
  4641.6   18.42  4831.4    23.9  4837.6    19.2  4891.1   18.17  4926.4   12.08
  4958.6   11.74  4977.8     1.3  5004.4   -3.26  5017.6    -.99  5044.3    11.3
  5099.6   15.57  5140.1   27.38    5152   29.05  5420.2   29.32  5459.4   35.62
  5529.4   34.62  5569.4   40.92  5997.5   45.02  6727.5   45.52    7328   49.42
#Mann= 9 ,-1 , 0
  1029.7     .99       0  1086.6     .08       0  3324.5     .05       0
  4344.5     .12       0  4831.4     .04       0  4958.6    .015       0
  5044.3     .04       0    5152     .08       0  5569.4     .99       0
#XS Ineff= 2 , 0
       0    4813    30.6 5432.31       0   46.04
Permanent Ineff=
       F       F
Bank Sta=4831.4,5140.1
XS Rating Curve= 0 ,0
Exp/Cntr=0.5,0.3

Type RM Length L Ch R = 3 ,7608.5  ,,,
BEGIN DESCRIPTION:
HOUSTON
Structure ID: E100-00-00-10
Bridge has 21.7 degree skew.  Did not model skew.
END DESCRIPTION:
Bridge Culvert--1,0,-1,-1, 0
Deck Dist Width WeirC Skew NumUp NumDn MinLoCord MaxHiCord MaxSubmerge Is_Ogee
10,61,2.6,0, 60, 60, , , 0.95, 0, ,,,
  1029.7  1049.7  1136.6  1346.6  1366.6  1556.6  1636.6  1669.7  1799.7  1979.7
  2229.7  2249.7  2619.7  2729.7  2769.7  2949.7  3038.7  3098.7  3128.7  3158.7
  3348.7  3637.2  3747.2  3837.2  3937.2  4067.2  4087.2  4151.6  4231.6  4626.3
  4686.3  4812.4 4812.49  4812.6 4812.71 4816.91    4817  4995.6    5152    5210
  5553.7  5579.4  5595.4  5595.5  5669.4  5709.4  5949.4  5997.5  6167.5  6257.5
  6307.5  6367.5  6387.5  6555.9  6727.5  6905.9  7005.9  7137.5  7277.5    7328
      51    50.3    51.7    51.2    50.4    51.7    51.1    49.8   51.31   48.91
   47.71    46.6   44.29   45.11   43.43   43.81   42.53    43.4    42.3    42.7
    40.5   43.01   42.01   35.71   35.41   33.01   31.71   31.71   28.01    24.5
    25.6   30.58    30.6    33.2    33.2   33.43   33.44   44.05   51.49   52.57
   45.02   45.06   45.06   42.17   42.41   41.52   43.71   45.01   44.31   46.01
   45.21   45.81   44.91    46.8   46.64    48.1   47.41   49.41    48.3    49.4
                                                                                
                                                                                
                                                                                
                                   22.92   23.13   26.44   37.05   44.49   45.57
   38.02    41.9   41.99
                                                                                
  1029.7  1049.7  1136.6  1346.6  1366.6  1556.6  1636.6  1669.7  1799.7  1979.7
  2229.7  2249.7  2619.7  2729.7  2769.7  2949.7  3038.7  3098.7  3128.7  3158.7
  3348.7  3637.2  3747.2  3837.2  3937.2  4067.2  4087.2  4151.6  4231.6  4626.3
  4686.3  4812.4 4812.49  4812.6 4812.71 4816.91    4817  4995.6    5152    5210
  5553.7  5579.4  5595.4  5595.5  5669.4  5709.4  5949.4  5997.5  6167.5  6257.5
  6307.5  6367.5  6387.5  6555.9  6727.5  6905.9  7005.9  7137.5  7277.5    7328
      51    50.3    51.7    51.2    50.4    51.7    51.1    49.8   51.31   48.91
   47.71    46.6   44.29   45.11   43.43   43.81   42.53    43.4    42.3    42.7
    40.5   43.01   42.01   35.71   35.41   33.01   31.71   31.71   28.01    24.5
    25.6   30.58    30.6    33.2    33.2   33.43   33.44   44.05   51.49   52.57
   45.02   45.06   45.06   42.17   42.41   41.52   43.71   45.01   44.31   46.01
   45.21   45.81   44.91    46.8   46.64    48.1   47.41   49.41    48.3    49.4
                                                                                
                                                                                
                                                                                
                                   22.92   23.13   26.44   37.05   44.49   45.57
   38.02    41.9   41.99
                                                                                
Pier Skew, UpSta & Num, DnSta & Num=  ,4927, 2 ,4927, 2 , 0 , 0 , 0 ,,
     2.5     2.5
   11.14   33.97
     2.5     2.5
   11.27    34.1
Pier Skew, UpSta & Num, DnSta & Num=  ,4987.1, 2 ,4987.1, 2 , 0 , 0 , 0 ,,
     2.5     2.5
   -1.61   37.62
     2.5     2.5
   -1.48   37.75
Pier Skew, UpSta & Num, DnSta & Num=  ,5043.1, 2 ,5043.1, 2 , 0 , 0 , 0 ,,
     2.5     2.5
    9.17    40.8
     2.5     2.5
     9.3   40.93
Pier Skew, UpSta & Num, DnSta & Num=  ,5099.6, 2 ,5099.6, 2 , 0 , 0 , 0 ,,
     2.5     2.5
   14.66   43.41
     2.5     2.5
   14.79   43.54
Pier Skew, UpSta & Num, DnSta & Num=  ,5155.1, 2 ,5155.1, 2 , 0 , 0 , 0 ,,
     2.5     2.5
   28.05    45.6
     2.5     2.5
   28.18   45.73
Pier Skew, UpSta & Num, DnSta & Num=  ,5255.1, 2 ,5255.1, 2 , 0 , 0 , 0 ,,
     2.5     2.5
   28.44   45.63
     2.5     2.5
   28.57   45.76
Pier Skew, UpSta & Num, DnSta & Num=  ,5355.1, 2 ,5355.1, 2 , 0 , 0 , 0 ,,
     2.5     2.5
   29.16   43.49
     2.5     2.5
   29.29   43.62
Pier Skew, UpSta & Num, DnSta & Num=  ,5460, 2 ,5460, 2 , 0 , 0 , 0 ,,
     2.5     2.5
   29.16   43.49
     2.5     2.5
   29.29   43.62
BR Coef= 1 , 1 , 0 ,1.25, 0 ,,,0.8,0,2,0,
WSPro=,,,, 1 ,,,, 0 ,,,, 0 ,,,,-1 ,-1 ,-1 , 0 , 0 , 0 , 0 , 0
BC Design=,, 0 ,, 0 ,,,,,,
BC HTab HWMax=51.72
BC Use User HTab Curves=0
BC User HTab FreeFlow(D)= 0

Type RM Length L Ch R = 1 ,7568.0  ,21.5,22,23
BEGIN DESCRIPTION:
Downstream Section of Bridge/Culvert/Weir
END DESCRIPTION:
XS GIS Cut Line= 6
      3117695.94     13852199.59      3118856.92     13850433.98
      3119068.24      13849486.1       3119113.5     13848106.15
      3118657.16     13847867.61      3118250.13      13846582.9
#Sta/Elev= 30
  1029.7   51.13  1086.6   51.08  1669.7   49.33  1799.7   51.43  2619.7   43.53
  2729.7   45.23  3324.5   40.31  3747.2   42.13  3837.2   35.83  4344.5   27.24
  4641.6   18.53  4831.4   24.01  4837.6   19.31  4891.1   18.28  4926.4   12.19
  4958.6   11.85  4977.8    1.41  5004.4   -3.15  5017.6    -.88  5044.3   11.41
  5099.6   15.68  5140.1   27.49    5152   29.16  5420.2   29.43  5459.4   35.73
  5529.4   34.73  5569.4   41.03  5997.5   45.13  6727.5   45.63    7328   49.53
#Mann= 9 ,-1 , 0
  1029.7     .99       0  1086.6     .08       0  3324.5     .05       0
  4344.5     .12       0  4831.4     .04       0  4958.6    .015       0
  5044.3     .04       0    5152     .08       0  5569.4     .99       0
#XS Ineff= 2 , 0
       0    4813    28.4 5432.31       0   44.08
Permanent Ineff=
       F       F
Bank Sta=4831.4,5140.1
XS Rating Curve= 0 ,0
Exp/Cntr=0.5,0.3

Type RM Length L Ch R = 1 ,7546.0  ,16,17,17.3
BEGIN DESCRIPTION:
Upstream Section of Bridge/Culvert/Weir
END DESCRIPTION:
XS GIS Cut Line= 6
 3117762.982613713852121.8861266      3118877.58     13850427.71
      3119088.84     13849478.28      3119134.09     13848099.56
      3118678.09      13847861.2 3118323.602299213846743.6171028
#Sta/Elev= 30
  1086.4   51.09  1086.6   51.09  1556.6   51.69  2226.5   46.19  3324.5   40.77
  3648.6   42.29  3798.7   33.49  4048.7   32.49  4208.6   27.29  4344.5   26.37
    4687   25.58  4831.4   23.87  4837.6   19.17  4891.1   18.14  4926.4   12.05
  4958.6   11.71  4977.8    1.27  5004.4   -3.16  5017.6   -1.02  5044.3   11.27
  5099.6   15.54    5149   29.05    5152    29.6  5410.9   30.19  5440.8   33.27
  5475.4   41.89  5555.4   37.19  5625.3   40.89  5885.3   42.79  7153.5   48.39
#Mann= 9 ,-1 , 0
  1086.4     .99       0  1086.6     .08       0  3324.5     .05       0
  4344.5     .12       0    4687     .04       0  4958.6    .015       0
  5044.3     .04       0    5152     .08       0  5475.4     .99       0
#XS Ineff= 2 , 0
       0    4813      28 5432.31       0   44.08
Permanent Ineff=
       F       F
Bank Sta=4831.4,5149
XS Rating Curve= 0 ,0
Exp/Cntr=0.5,0.3

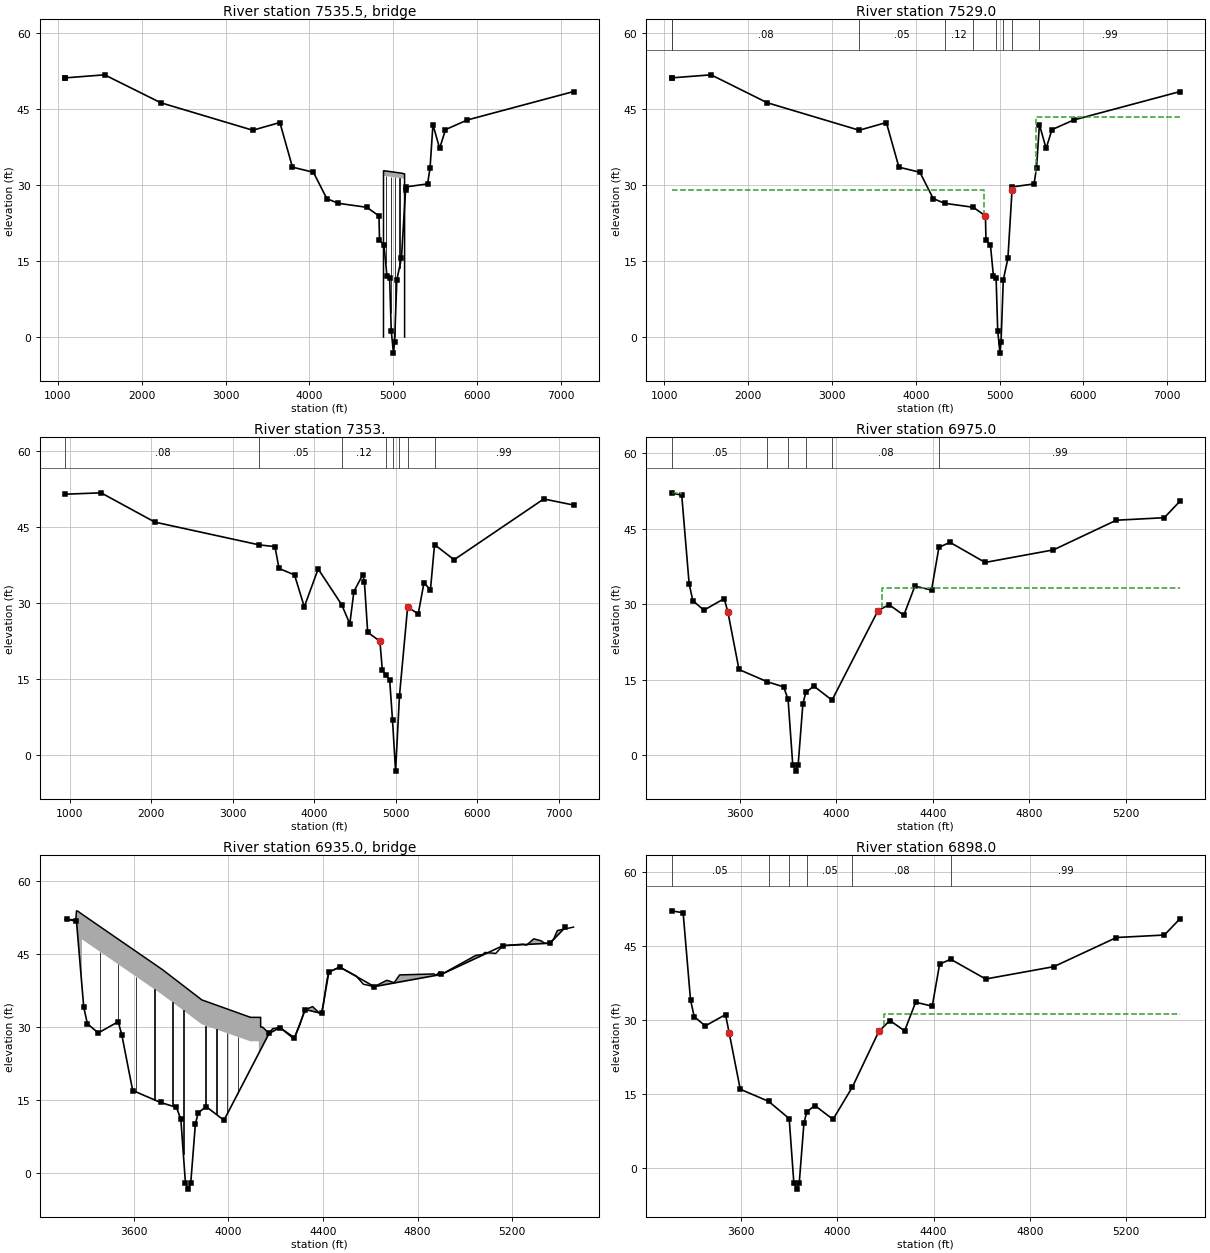
Type RM Length L Ch R = 3 ,7535.5  ,,,
BEGIN DESCRIPTION:
PL1_E100-00-00-10
80' US Houston
Pipeline has 18 degree skew with channel.
END DESCRIPTION:
Bridge Culvert--1,0,-1,-1, 0
Deck Dist Width WeirC Skew NumUp NumDn MinLoCord MaxHiCord MaxSubmerge Is_Ogee
10,1,2.6,0, 23, 23, , , 0.95, 0, ,,,
  4885.2  4885.3  4886.2  4886.3  4900.8  4926.4  4946.6  4958.6  4977.8  4992.4
  4995.6  5004.4  5008.3  5017.6  5022.2  5044.3  5073.4  5097.2  5099.6    5136
 5136.01    5137 5137.01
       0   32.77   32.77   32.77   32.77   32.71   32.66   32.64   32.59   32.56
   32.55   32.53   32.52    32.5   32.49   32.44   32.37   32.31   32.31   32.18
   32.18   32.18       0
                           31.76   31.76    31.7   31.65   31.63   31.58   31.55
   31.54   31.52   31.51   31.49   31.48   31.43   31.36    31.3    31.3   31.17
                        
  4885.2  4885.3  4886.2  4886.3  4900.8  4926.4  4946.6  4958.6  4977.8  4992.4
  4995.6  5004.4  5008.3  5017.6  5022.2  5044.3  5073.4  5097.2  5099.6    5136
 5136.01    5137 5137.01
       0   32.77   32.77   32.77   32.77   32.71   32.66   32.64   32.59   32.56
   32.55   32.53   32.52    32.5   32.49   32.44   32.37   32.31   32.31   32.18
   32.18   32.18       0
                           31.76   31.76    31.7   31.65   31.63   31.58   31.55
   31.54   31.52   31.51   31.49   31.48   31.43   31.36    31.3    31.3   31.17
                        
Pier Skew, UpSta & Num, DnSta & Num=  ,4911.5, 2 ,4911.5, 2 , 0 , 0 , 0 ,,
     1.1     1.1
   13.53   32.74
     1.1     1.1
   13.53   32.74
Pier Skew, UpSta & Num, DnSta & Num=  ,4971.5, 2 ,4971.5, 2 , 0 , 0 , 0 ,,
     1.1     1.1
     3.4    32.6
     1.1     1.1
     3.4    32.6
Pier Skew, UpSta & Num, DnSta & Num=  ,5019.9, 2 ,5019.9, 2 , 0 , 0 , 0 ,,
     1.1     1.1
   -1.15   32.49
     1.1     1.1
   -1.15   32.49
Pier Skew, UpSta & Num, DnSta & Num=  ,5075.8, 2 ,5075.8, 2 , 0 , 0 , 0 ,,
     1.1     1.1
   13.74   32.36
     1.1     1.1
   13.74   32.36
Pier Skew, UpSta & Num, DnSta & Num=  ,5131.4, 2 ,5131.4, 2 , 0 , 0 , 0 ,,
     1.1     1.1
   23.09   32.22
     1.1     1.1
   23.09   32.22
BR Coef= 1 , 1 , 0 ,1.25, 0 ,,,0.8,0,2,0,
WSPro=,,,, 1 ,,,, 0 ,,,, 0 ,,,,-1 ,-1 ,-1 , 0 , 0 , 0 , 0 , 0
BC Design=,, 0 ,, 0 ,,,,,,
BC HTab HWMax=51.69
BC Use User HTab Curves=0
BC User HTab FreeFlow(D)= 0

Type RM Length L Ch R = 1 ,7529.0  ,267.4,176,128.9
BEGIN DESCRIPTION:
Downstream Section of Bridge/Culvert/Weir
END DESCRIPTION:
XS GIS Cut Line= 6
 3117779.227270313852116.5864355      3118893.98     13850422.15
      3119105.24     13849472.72      3119150.49       13848094.
      3118694.49     13847855.64 3118340.092944113846738.3428761
#Sta/Elev= 30
  1086.4   51.09  1086.6   51.09  1556.6   51.69  2226.5   46.19  3324.5   40.77
  3648.6   42.29  3798.7   33.49  4048.7   32.49  4208.6   27.29  4344.5   26.37
    4687   25.58  4831.4   23.87  4837.6   19.17  4891.1   18.14  4926.4   12.05
  4958.6   11.71  4977.8    1.27  5004.4   -3.16  5017.6   -1.02  5044.3   11.27
  5099.6   15.54    5149   29.05    5152    29.6  5410.9   30.19  5440.8   33.27
  5475.4   41.89  5555.4   37.19  5625.3   40.89  5885.3   42.79  7153.5   48.39
#Mann= 9 ,-1 , 0
  1086.4     .99       0  1086.6     .08       0  3324.5     .05       0
  4344.5     .12       0    4687     .04       0  4958.6    .015       0
  5044.3     .04       0    5152     .08       0  5475.4     .99       0
#XS Ineff= 2 , 0
       0    4813      29 5432.31       0   43.43
Permanent Ineff=
       F       F
Bank Sta=4831.4,5149
XS Rating Curve= 0 ,0
Exp/Cntr=0.5,0.3

Type RM Length L Ch R = 1 ,7353.   ,578.3,378,63.5
BEGIN DESCRIPTION:
PL1 - D/S - XS 1
END DESCRIPTION:
XS GIS Cut Line= 6
      3117834.49      13852156.3      3118995.86     13850391.02
      3119286.06     13849342.11      3119385.87     13848914.32
      3119243.28     13848208.48      3118388.76     13846539.45
#Sta/Elev= 30
   947.3   51.45  1387.3   51.72  2047.3   45.94  3330.3   41.44  3520.3   41.11
  3570.3    36.8  3760.3   35.53  3880.3   29.23  4050.3    36.7  4338.7   29.66
  4438.7   25.88  4488.7   32.25  4597.9   35.59  4617.9   34.09  4657.9    24.2
  4807.9   22.45  4837.9   16.68  4877.9   15.75  4927.9   14.74 4962.74    6.83
    5000   -3.18  5047.9    11.7  5147.9   29.18  5277.9   27.84    5348   33.93
    5428   32.61    5478   41.51    5718   38.52    6818   50.51  7183.1   49.31
#Mann= 8 ,-1 , 0
   947.3     .08       0  3330.3     .05       0  4338.7     .12       0
  4877.9     .04       0 4962.74    .015       0  5047.9     .04       0
  5147.9     .08       0    5478     .99       0
Bank Sta=4807.9,5147.9
XS Rating Curve= 0 ,0
Exp/Cntr=0.5,0.3

Type RM Length L Ch R = 1 ,6975.0  ,61,77,78
BEGIN DESCRIPTION:
Upstream Section of Bridge/Culvert/Weir
END DESCRIPTION:
XS GIS Cut Line= 6
 3120107.084920913848984.6653059      3119818.88     13848491.98
      3119721.31     13848419.86      3119598.29     13848368.96
      3119350.72     13848346.22 3118606.161196713846791.0010712
#Sta/Elev= 30
3316.896    52.13358.568    51.73389.209    34.13404.531    30.73450.494    28.8
3534.759    31.1 3550.08    28.43596.042      173713.783   14.553781.042   13.54
 3799.58   11.063818.885   -1.943831.601   -3.223841.406   -1.953860.941   10.16
3872.967   12.43 3906.29    13.73981.746    10.94172.261    28.74218.224    29.9
4279.507    27.8 4325.47    33.64394.414    32.84425.056    41.34471.019    42.3
4616.567    38.34900.003    40.85160.458    46.7 5359.63    47.25424.667    50.5
#Mann= 6 ,-1 , 0
3316.896     .05       03713.783     .04       0 3799.58    .015       0
3872.967     .04       03981.746     .08       04425.056     .99       0
#XS Ineff= 2 , 0
       03354.539   52.154190.738       0   33.31
Permanent Ineff=
       F       F
Bank Sta=3550.08,4172.261
XS Rating Curve= 0 ,0
Skew Angle= 40
Exp/Cntr=0.5,0.3

Type RM Length L Ch R = 3 ,6935.0  ,,,
BEGIN DESCRIPTION:
I-10 EAST ON RAMP
Structure ID: E100-09b
Bridge has a 40 degree skew with the channel.
END DESCRIPTION:
Bridge Culvert--1,0,-1,-1, 0
Deck Dist Width WeirC Skew NumUp NumDn MinLoCord MaxHiCord MaxSubmerge Is_Ogee
10,60,2.6,40, 64, 64, , , 0.95, 0, ,,,
 3310.92 3318.58  3333.9 3341.56 3349.22 3350.91 3355.12 3355.21 3355.28 3358.57
 3366.23 3373.89 3381.55 3722.44 3888.06 4092.82  4092.9 4092.98 4111.97 4128.98
 4129.06 4136.72 4136.72 4142.62 4144.84 4172.26 4187.58 4218.22 4271.85 4279.51
 4302.49 4317.81 4325.47 4356.11 4386.75 4394.41 4402.07  4417.4 4425.06 4471.02
 4539.96  4570.6 4616.57 4670.19 4700.83 4723.81 4869.36 4877.02 4892.34    4900
 5045.55 5076.19 5083.85 5129.82 5160.46 5244.72 5260.04 5290.69 5321.33 5336.65
 5359.63 5374.95 5390.27 5458.68
52.09999   52.09   52.05   52.03   52.01   52.01   51.85   51.84   51.84   53.84
   53.71   53.42   53.16   41.76   35.58   32.02      32      32      32      32
      32      32      30      30      30    28.7    29.7    29.9    27.8    27.8
    30.5    32.8    33.6    34.2    32.8    32.8    34.7    39.8    41.3    42.3
    40.5    38.8    38.3    39.6    39.1    40.7    40.9    40.6    41.3    40.8
    44.7    44.9    45.3    45.1    46.7      47    46.8    48.1    47.7    47.2
    47.2    48.1    49.850.49999
                                                                                
                   48.01   36.61   30.57    27.1   27.08   27.08   27.08   27.08
                                                                                
                                                                                
                                                                                
                                                                                
                                
 3310.92 3318.58  3333.9 3341.56 3349.22 3350.91 3355.12 3355.21 3355.28 3358.57
 3366.23 3373.89 3381.55 3722.44 3888.06 4092.82  4092.9 4092.98 4111.97 4128.98
 4129.06 4136.72 4136.72 4142.62 4144.84 4172.26 4187.58 4218.22 4271.85 4279.51
 4302.49 4317.81 4325.47 4356.11 4386.75 4394.41 4402.07  4417.4 4425.06 4471.02
 4539.96  4570.6 4616.57 4670.19 4700.83 4723.81 4869.36 4877.02 4892.34    4900
 5045.55 5076.19 5083.85 5129.82 5160.46 5244.72 5260.04 5290.69 5321.33 5336.65
 5359.63 5374.95 5390.27 5458.68
52.09999   52.09   52.05   52.03   52.01   52.01   51.85   51.84   51.84   53.84
   53.71   53.42   53.16   41.76   35.58   32.02      32      32      32      32
      32      32      30      30      30    28.7    29.7    29.9    27.8    27.8
    30.5    32.8    33.6    34.2    32.8    32.8    34.7    39.8    41.3    42.3
    40.5    38.8    38.3    39.6    39.1    40.7    40.9    40.6    41.3    40.8
    44.7    44.9    45.3    45.1    46.7      47    46.8    48.1    47.7    47.2
    47.2    48.1    49.850.49999
                                                                                
                   48.01   36.61   30.57    27.1   27.08   27.08   27.08   27.08
                                                                                
                                                                                
                                                                                
                                                                                
                                
Pier Skew, UpSta & Num, DnSta & Num=  ,3457.388, 2 ,3457.388, 2 , 0 , 0 , 0 ,,
       3       3
   29.81      50
       3       3
   29.81      50
Pier Skew, UpSta & Num, DnSta & Num=  ,3533.993, 2 ,3533.993, 2 , 0 , 0 , 0 ,,
       3       3
   19.66      50
       3       3
   19.66      50
Pier Skew, UpSta & Num, DnSta & Num=  ,3610.597, 2 ,3610.597, 2 , 0 , 0 , 0 ,,
       3       3
   15.28      45
       3       3
   15.28      45
Pier Skew, UpSta & Num, DnSta & Num=  ,3687.202, 2 ,3687.202, 2 , 0 , 0 , 0 ,,
       3       3
    14.5   38.26
       3       3
    14.5   38.26
Pier Skew, UpSta & Num, DnSta & Num=  ,3763.806, 2 ,3763.806, 2 , 0 , 0 , 0 ,,
     2.5     2.5
   13.02   35.45
     2.5     2.5
   13.02   35.45
Pier Skew, UpSta & Num, DnSta & Num=  ,3810.075, 2 ,3810.075, 2 , 0 , 0 , 0 ,,
     2.5     2.5
    2.15   33.77
     2.5     2.5
    2.15   33.77
Pier Skew, UpSta & Num, DnSta & Num=  ,3902.69, 2 ,3902.69, 2 , 0 , 0 , 0 ,,
     2.5     2.5
   12.17   31.88
     2.5     2.5
   12.17   31.88
Pier Skew, UpSta & Num, DnSta & Num=  ,3948.653, 2 ,3948.653, 2 , 0 , 0 , 0 ,,
       3       3
    5.97   32.13
       3       3
    5.97   32.13
Pier Skew, UpSta & Num, DnSta & Num=  ,3994.615, 2 ,3994.615, 2 , 0 , 0 , 0 ,,
     2.5     2.5
   15.26   31.63
     2.5     2.5
   15.26   31.63
Pier Skew, UpSta & Num, DnSta & Num=  ,4040.578, 2 ,4040.578, 2 , 0 , 0 , 0 ,,
     2.5     2.5
   22.13   31.39
     2.5     2.5
   22.13   31.39
BR Coef= 1 , 1 , 0 ,1.25, 0 ,,,0.8,0,1.2,0,
WSPro=,,,, 1 ,,,, 0 ,,,, 0 ,,,,-1 ,-1 ,-1 , 0 , 0 , 0 , 0 , 0
BR D #Sta/Elev= 101
 3310.92    52.1 3318.58   52.08  3333.9   52.04 3341.56   52.02 3349.22      52
 3350.91      52 3355.12   51.84 3355.21   51.83 3355.28   51.83 3358.57    51.7
 3366.23    48.8 3373.89    43.8 3381.55    38.1 3389.21    34.1 3396.87    31.8
 3404.53    30.7 3419.85      30 3427.51    29.3 3450.49    28.8  3488.8    30.6
 3504.12    30.5  3527.1    31.1 3534.76    31.1 3542.42    30.2 3550.08   27.39
 3580.72   18.49 3588.38   16.89 3596.04   15.99 3623.39   15.79 3676.86   15.39
 3713.78   13.54 3714.93   13.48 3722.44   13.48 3749.71   13.46 3750.09   13.45
 3781.04   12.53 3799.58   10.05 3816.36   -1.53 3818.89   -2.95 3824.32   -3.17
  3831.6   -4.23  3832.6   -4.08 3835.51   -3.05 3841.41   -2.96 3844.16   -1.35
 3853.59    4.69 3856.73     6.7 3860.94    9.15 3872.97   11.42 3881.39   11.86
 3888.06   12.21 3906.29   12.69 3981.75    9.89 4061.95    16.4 4088.99   18.59
 4091.98   18.94 4092.82   19.04  4092.9   19.05 4092.98   19.06 4111.97   21.29
 4142.62   25.49 4144.84   25.65 4172.26   27.69 4187.58    29.7 4218.22    29.9
 4271.85    27.8 4279.51    27.8 4302.49    30.5 4317.81    32.8 4325.47    33.6
 4356.11    34.2 4386.75    32.8 4394.41    32.8 4402.07    34.7  4417.4    39.8
 4425.06    41.3 4471.02    42.3 4539.96    40.5  4570.6    38.8 4616.57    38.3
 4670.19    39.6 4700.83    39.1 4723.81    40.7 4869.36    40.9 4877.02    40.6
 4892.34    41.3    4900    40.8 5045.55    44.7 5076.19    44.9 5083.85    45.3
 5129.82    45.1 5160.46    46.7 5244.72      47 5260.04    46.8 5290.69    48.1
 5321.33    47.7 5336.65    47.2 5359.63    47.2 5374.95    48.1 5390.27    49.8
 5458.68    50.5
BR D #Mann= 6
 3310.92     .05 3713.78     .05 3799.58    .015 3872.97     .05 4061.95     .08
 4471.02     .99
BR D Banks=,4172.26
BC Design=,, 0 ,, 0 ,,,,,,
BC HTab HWMax=52.1
BC Use User HTab Curves=0
BC User HTab FreeFlow(D)= 0

Type RM Length L Ch R = 1 ,6898.0  ,74.5,123,402
BEGIN DESCRIPTION:
Downstream Section of Bridge/Culvert/Weir
N-values raised to account for the pier of the main lanes not included in the model.
END DESCRIPTION:
XS GIS Cut Line= 6
 3120166.700094913848966.0206275      3119870.36     13848459.91
      3119765.77     13848382.61      3119635.15     13848328.56
      3119400.01     13848306.96 3118662.811337813846767.1010037
#Sta/Elev= 30
3310.921    52.13358.568    51.73389.209    34.13404.531    30.73450.494    28.8
3534.759    31.1 3550.08   27.393596.042   15.993713.783   13.54 3799.58   10.05
3818.885   -2.953831.601   -4.233841.406   -2.963860.941    9.153872.967   11.42
 3906.29   12.693981.746    9.894061.951    16.44172.261   27.694218.224    29.9
4279.507    27.8 4325.47    33.64394.414    32.84425.056    41.34471.019    42.3
4616.567    38.34900.003    40.85160.458    46.7 5359.63    47.25424.667    50.5
#Mann= 6 ,-1 , 0
3310.921     .05       03713.783     .05       0 3799.58    .015       0
3872.967     .05       04061.951     .08       04471.019     .99       0
#XS Ineff= 2 , 0
       03354.539   51.064195.181       0   31.26
Permanent Ineff=
       F       F
Bank Sta=3550.08,4172.261
XS Rating Curve= 0 ,0
Skew Angle= 40
Exp/Cntr=0.5,0.3