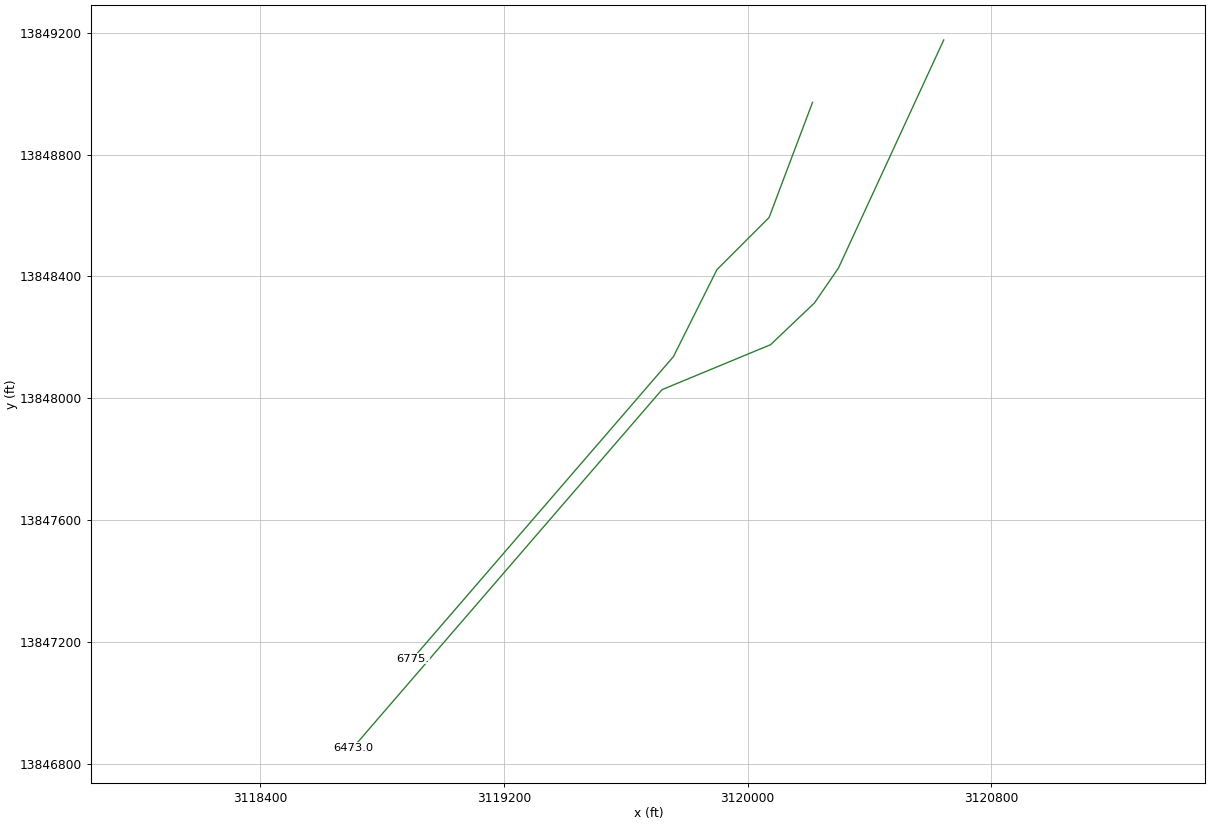
HEC-RAS study E100-00-00.prj: E100-00-00

--- E100-00-00.g02 (geometry) --- (continued)

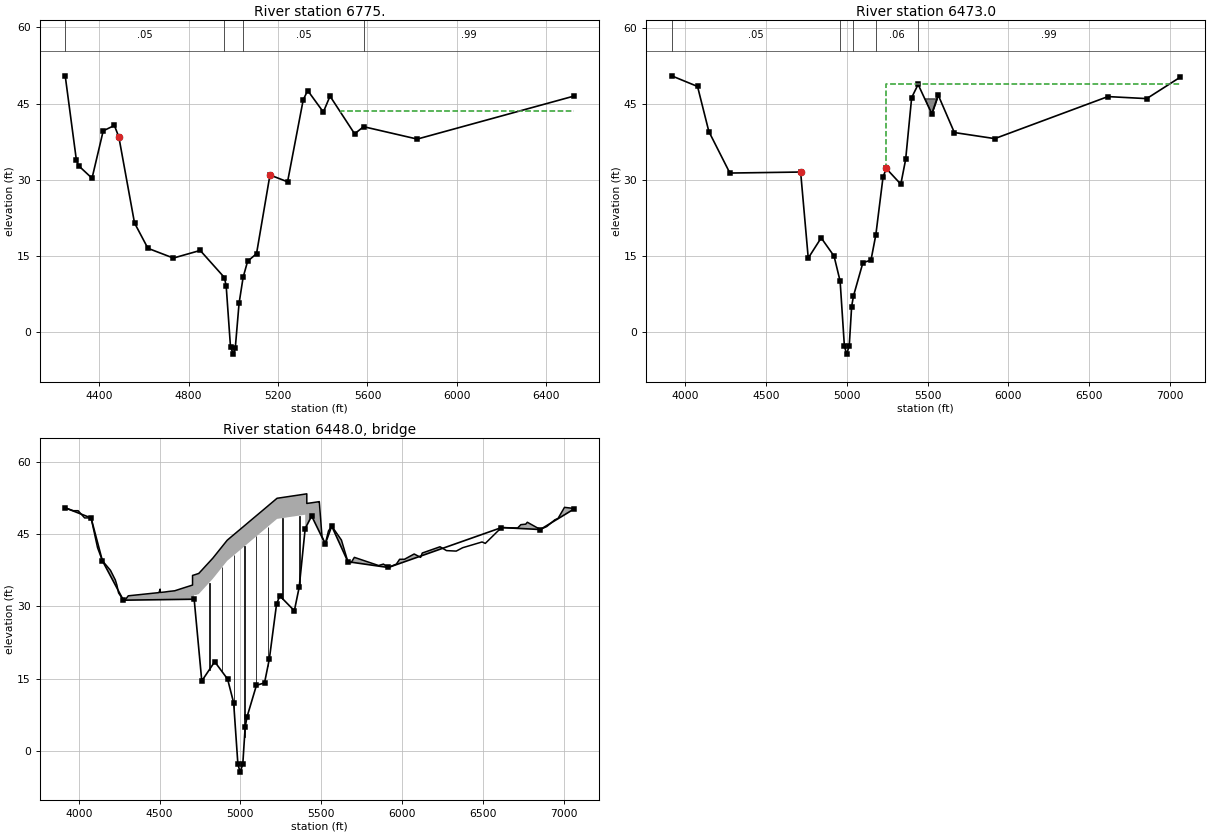
Type RM Length L Ch R = 1 ,6775.   ,303,302,169.2
BEGIN DESCRIPTION:
I-45 N Ramp - U/S - XS 4
END DESCRIPTION:
XS GIS Cut Line= 5
      3120212.92     13848971.36      3120070.33     13848593.48
      3119899.22     13848422.37      3119756.62     13848137.18
      3118901.05     13847146.14
#Sta/Elev= 30
  4247.7   50.48  4297.7   33.89  4307.7   32.78  4367.7   30.32  4417.7   39.65
  4467.7   40.71  4487.7   38.43  4557.7   21.52  4617.7   16.53  4731.6   14.61
  4851.6   16.11 4960.01   10.77 4967.88    9.07 4987.24   -2.94    5000    -4.3
  5008.5   -3.11 5025.43    5.69  5043.6   10.81  5063.6   13.97  5103.6   15.48
  5163.6   30.96  5242.4   29.62  5312.4   45.74  5332.4   47.59  5402.4   43.35
  5432.4   46.48  5542.4   39.06  5582.4   40.47  5822.4   38.03  6521.7   46.47
#Mann= 4 ,-1 , 0
  4247.7     .05       0 4960.01    .015       0  5043.6     .05       0
  5582.4     .99       0
#XS Ineff= 2 , 0
                          5482.5           43.58
Permanent Ineff=
       F       F
Bank Sta=4487.7,5163.6
XS Rating Curve= 0 ,0
Exp/Cntr=0.5,0.3

Type RM Length L Ch R = 1 ,6473.0  ,47.9,50,53.2
BEGIN DESCRIPTION:
Upstream Section of Bridge/Culvert/Weir
N-values raised to account for the pier of the main lanes not included in the model.
END DESCRIPTION:
XS GIS Cut Line= 6
      3120643.32     13849175.94      3120298.04     13848427.84
      3120218.91     13848312.75      3120075.05     13848176.07
      3119718.98     13848028.61 3118705.5260161 13846854.335072
#Sta/Elev= 30
  3916.6    50.5  4076.6    48.4  4146.6    39.5  4276.6    31.3  4714.3    31.5
  4761.4    14.5  4841.4    18.5    4921    14.9  4958.6    9.95  4984.9   -2.85
  4998.9   -4.46  5015.1    -2.8  5029.8    4.93    5041       7  5099.5    13.6
  5149.5    14.1  5179.5    19.1    5224    30.5    5244    32.2    5334    29.1
    5364      34  5401.1    46.2  5441.1    48.8  5525.2      43  5565.2    46.7
  5665.2    39.3  5915.2    38.1  6615.2    46.4  6855.2      46    7061    50.2
#Mann= 5 ,-1 , 0
  3916.6     .05       0  4958.6    .015       0    5041     .05       0
  5179.5     .06       0  5441.1     .99       0
#XS Ineff= 2 , 0
       0                    5245       0   48.88
Permanent Ineff=
       F       F
#Block Obstruct= 1 ,-1
5459.831 5564.63   46.04
Bank Sta=4714.3,5244
XS Rating Curve= 0 ,0
Exp/Cntr=0.5,0.3

Type RM Length L Ch R = 3 ,6448.0  ,,,
BEGIN DESCRIPTION:
I 45 NORTH ON RAMP   E100-00-00-09a
Structure ID: E100-00-00-09a
N-values raised to account for the pier of the main lanes not included in the model.  Bridge is skewed by 20 degrees to the channel.
END DESCRIPTION:
Bridge Culvert--1,0,-1,-1, 0
Deck Dist Width WeirC Skew NumUp NumDn MinLoCord MaxHiCord MaxSubmerge Is_Ogee
16,30,2.6,0, 114, 114, , , 0.95, 0, ,,,
3916.601  3966.63996.601  4036.6  4076.6  4116.64146.6014196.601  4226.6  4236.6
  4246.64276.601  4286.6  4306.64497.109  4497.24503.601    4505  4534.3  4554.3
  4594.3  4604.3  4664.3  4684.3 4704.29  4704.3  4714.3  4724.34741.399  4742.7
  4751.4  4761.4  4771.44791.399  4807.8  4827.24829.201  4886.2    48894918.599
  4933.7    4946  4958.6    4962  4981.2  4984.94992.6014998.899  4999.6    5007
  5015.15018.799  5038.85052.801  5097.15121.899  5162.6  5168.2  5182.5    5184
    5214    52245227.201    5244    5334    5344    5354    53645381.101  5401.1
  5411.1 5411.11  5421.1  5441.1  5465.2 5467.09  5467.25485.2015488.299  5505.2
  5525.2  5545.25565.2015625.201  5665.2  5685.2  5705.25855.201  5885.25915.201
  5965.25985.2016015.2016075.201  6115.26125.201  6235.2  6275.2  6335.2  6375.2
  6495.2  6515.2  6615.26715.201  6735.26765.1996775.201  6855.26895.201  6945.2
6965.201  7005.27055.201    7061
   50.51   49.91   49.91   48.41   48.41   42.21   39.51   37.51   35.51   34.41
   32.81   31.31   31.31   32.21   32.88   32.88    33.6   32.91   33.01   33.11
   33.26   33.37   34.02   34.23   34.45   36.45   36.55   36.66   36.85   36.86
   37.18   37.54   37.91   38.64   39.24   39.95   40.02   42.41   42.53   43.77
    44.2   44.55    44.9      45   45.54   45.65   45.86   46.04   46.06   46.27
    46.5    46.6   47.17   47.57   48.82   49.52   50.67   50.83   51.24   51.28
   52.13   52.41    52.5   52.58   53.03   53.08   53.13   53.18   53.27   53.37
   53.42   51.42   51.47   51.56   51.68   51.69   51.69   51.78    51.8   44.51
   43.01   45.71   46.71   43.81   39.31   39.11   40.21   38.51   38.81   38.11
   38.81   39.81   39.81   40.91   40.21   41.11   42.41   41.61   41.51   42.21
   43.41   43.11   46.41   46.31   47.01   47.11   47.51   46.01   46.61   48.01
   48.31   50.61   50.41   50.21
                                                                                
                                                                                
                                                   32.42   32.37   32.56   32.57
   32.89   33.25   33.62   34.35   34.95   35.66   35.73   38.12   38.24   39.48
   39.91   40.26   40.61   40.71   41.25   41.36   41.57   41.75   41.77   41.98
   42.21   42.31   42.88   43.28   44.53   45.23   46.38   46.54   46.95   46.99
   47.84   48.12   48.21   48.29   48.74   48.79   48.84   48.89   48.98   49.08
                                                                                
                                                                                
                                                                                
                                                                                
                                
3916.601  3966.63996.601  4036.6  4076.6  4116.64146.6014196.601  4226.6  4236.6
  4246.64276.601  4286.6  4306.64497.109  4497.24503.601    4505  4534.3  4554.3
  4594.3  4604.3  4664.3  4684.3 4704.29  4704.3  4714.3  4724.34741.399  4742.7
  4751.4  4761.4  4771.44791.399  4807.8  4827.24829.201  4886.2    48894918.599
  4933.7    4946  4958.6    4962  4981.2  4984.94992.6014998.899  4999.6    5007
  5015.15018.799  5038.85052.801  5097.15121.899  5162.6  5168.2  5182.5    5184
    5214    52245227.201    5244    5334    5344    5354    53645381.101  5401.1
  5411.1 5411.11  5421.1  5441.1  5465.2 5467.09  5467.25485.2015488.299  5505.2
  5525.2  5545.25565.2015625.201  5665.2  5685.2  5705.25855.201  5885.25915.201
  5965.25985.2016015.2016075.201  6115.26125.201  6235.2  6275.2  6335.2  6375.2
  6495.2  6515.2  6615.26715.201  6735.26765.1996775.201  6855.26895.201  6945.2
6965.201  7005.27055.201    7061
   50.51   49.91   49.91   48.41   48.41   42.21   39.51   37.51   35.51   34.41
   32.81   31.31   31.31   32.21   32.88   32.88    33.6   32.91   33.01   33.11
   33.26   33.37   34.02   34.23   34.45   36.45   36.55   36.66   36.85   36.86
   37.18   37.54   37.91   38.64   39.24   39.95   40.02   42.41   42.53   43.77
    44.2   44.55    44.9      45   45.54   45.65   45.86   46.04   46.06   46.27
    46.5    46.6   47.17   47.57   48.82   49.52   50.67   50.83   51.24   51.28
   52.13   52.41    52.5   52.58   53.03   53.08   53.13   53.18   53.27   53.37
   53.42   51.42   51.47   51.56   51.68   51.69   51.69   51.78    51.8   44.51
   43.01   45.71   46.71   43.81   39.31   39.11   40.21   38.51   38.81   38.11
   38.81   39.81   39.81   40.91   40.21   41.11   42.41   41.61   41.51   42.21
   43.41   43.11   46.41   46.31   47.01   47.11   47.51   46.01   46.61   48.01
   48.31   50.61   50.41   50.21
                                                                                
                                                                                
                                                   32.42   32.37   32.56   32.57
   32.89   33.25   33.62   34.35   34.95   35.66   35.73   38.12   38.24   39.48
   39.91   40.26   40.61   40.71   41.25   41.36   41.57   41.75   41.77   41.98
   42.21   42.31   42.88   43.28   44.53   45.23   46.38   46.54   46.95   46.99
   47.84   48.12   48.21   48.29   48.74   48.79   48.84   48.89   48.98   49.08
                                                                                
                                                                                
                                                                                
                                                                                
                                
Pier Skew, UpSta & Num, DnSta & Num=  ,4807.8, 2 ,4807.8, 2 , 0 , 0 , 0 ,,
       3       3
    14.4      80
       3       3
   14.56      80
Pier Skew, UpSta & Num, DnSta & Num=  ,4886.2, 2 ,4886.2, 2 , 0 , 0 , 0 ,,
       3       3
   14.31   39.18
       3       3
   14.47   39.34
Pier Skew, UpSta & Num, DnSta & Num=  ,4962, 2 ,4962, 2 , 0 , 0 , 0 ,,
       3       3
    7.27   41.75
       3       3
    7.43   41.91
Pier Skew, UpSta & Num, DnSta & Num=  ,5026, 2 ,5026, 2 , 0 , 0 , 0 ,,
       3       3
    7.27   43.75
       3       3
    7.43   43.91
Pier Skew, UpSta & Num, DnSta & Num=  ,5098, 2 ,5098, 2 , 0 , 0 , 0 ,,
       3       3
       0      60
       3       3
       0      60
Pier Skew, UpSta & Num, DnSta & Num=  ,5170, 2 ,5170, 2 , 0 , 0 , 0 ,,
       3       3
    9.64      60
       3       3
     9.8      60
Pier Skew, UpSta & Num, DnSta & Num=  ,5260, 2 ,5260, 2 , 0 , 0 , 0 ,,
     2.5     2.5
   14.77      80
     2.5     2.5
   14.93      80
Pier Skew, UpSta & Num, DnSta & Num=  ,5365, 2 ,5365, 2 , 0 , 0 , 0 ,,
     2.5     2.5
    9.64      60
     2.5     2.5
     9.8      60
BR Coef= 1 , 1 , 0 ,1.25, 0 ,,,0.8,0,1.2,0,
WSPro=,,,, 1 ,,,, 0 ,,,, 0 ,,,,-1 ,-1 ,-1 , 0 , 0 , 0 , 0 , 0
BC Design=,, 0 ,, 0 ,,,,,,
BC HTab HWMax=50.62
BC Use User HTab Curves=0
BC User HTab FreeFlow(D)= 0