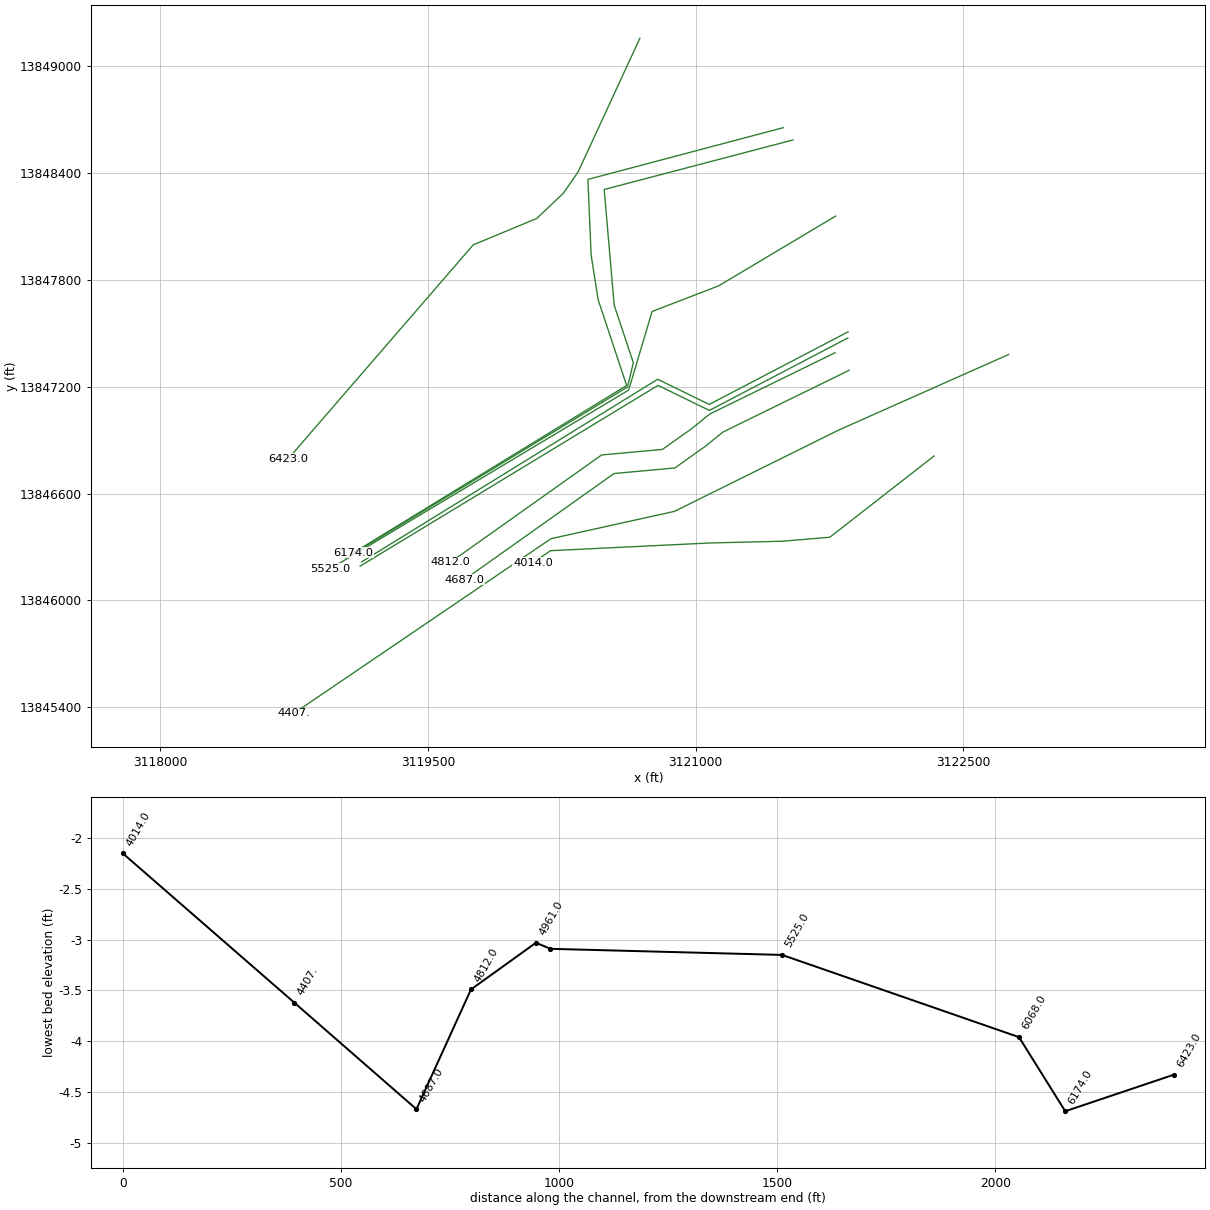
HEC-RAS study E100-00-00.prj: E100-00-00

--- E100-00-00.g02 (geometry) --- (continued)

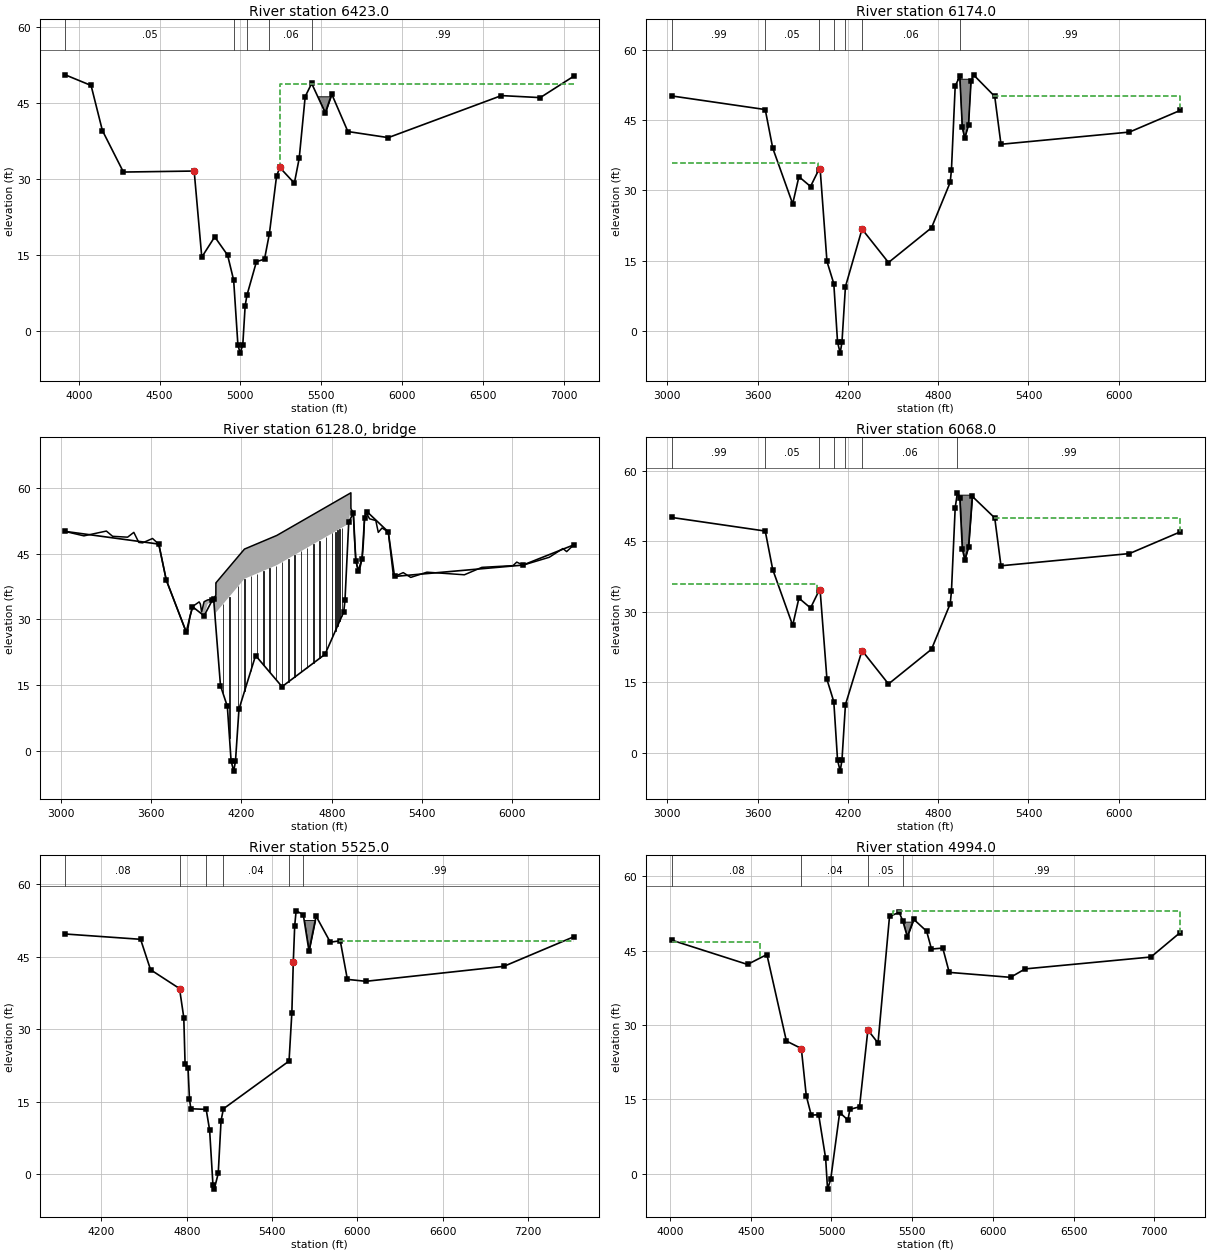
Type RM Length L Ch R = 1 ,6423.0  ,126.9,249,577.4
BEGIN DESCRIPTION:
Downstream Section of Bridge/Culvert/Weir
N-values raised to account for the pier of the main lanes not included in the model.
END DESCRIPTION:
XS GIS Cut Line= 6
      3120686.99     13849156.43      3120341.64     13848407.69
      3120258.62     13848286.93      3120109.23     13848145.01
      3119753.35     13847996.86      3118715.89     13846794.76
#Sta/Elev= 30
  3916.6   50.63  4076.6   48.53  4146.6   39.63  4276.6   31.43  4714.3   31.63
  4761.4   14.63  4841.4   18.63    4921   15.03  4958.6   10.08  4984.9   -2.72
  4998.9   -4.33  5015.1   -2.67  5029.8    5.06    5041    7.13  5099.5   13.73
  5149.5   14.23  5179.5   19.23    5224   30.63    5244   32.33    5334   29.23
    5364   34.13  5401.1   46.33  5441.1   48.93  5525.2   43.13  5565.2   46.83
  5665.2   39.43  5915.2   38.23  6615.2   46.53  6855.2   46.13    7061   50.33
#Mann= 5 ,-1 , 0
  3916.6     .05       0  4958.6    .015       0    5041     .05       0
  5179.5     .06       0  5441.1     .99       0
#XS Ineff= 2 , 0
       0                    5245       0   48.79
Permanent Ineff=
       F       F
#Block Obstruct= 1 ,-1
 5480.79 5561.14   46.39
Bank Sta=4714.3,5244
XS Rating Curve= 0 ,0
Exp/Cntr=0.5,0.3

Type RM Length L Ch R = 1 ,6174.0  ,105,106,160.9
BEGIN DESCRIPTION:
Upstream Section of Bridge/Culvert/Weir
N-value adjusted to account for pier outside of sta. 5178
END DESCRIPTION:
XS GIS Cut Line= 6
  3121490.81550813848654.8579968      3120395.97     13848364.34
      3120413.96     13847939.93      3120453.52     13847688.17
      3120613.03      13847207.1 3119082.033854513846267.7883413
#Sta/Elev= 30
3028.972   50.123650.751   47.223700.492   39.023833.138   27.12 3874.59   32.92
3951.856   30.824006.324   34.384015.443   34.654060.958   14.854106.472   10.11
4131.343   -2.34 4148.67   -4.694160.525   -2.414183.738    9.474294.083   21.74
4469.839   14.624755.691   22.024880.046   31.724888.337   34.424913.208   52.22
4943.799   54.324960.378   43.424976.961   41.125001.832   43.925018.413   53.22
5034.994   54.62 5175.93   50.025217.382   39.826071.291   42.426407.134   47.02
#Mann= 7 ,-1 , 0
3028.972     .99       03650.751     .05       04006.324     .04       0
4106.472    .015       04183.738     .04       04294.083     .06       0
4943.799     .99       0
#XS Ineff= 2 , 0
       0 4000.38   35.91 5163.84       0   50.06
Permanent Ineff=
       F       F
#Block Obstruct= 1 ,-1
4930.7865028.527   53.68
Bank Sta=4015.443,4294.083
XS Rating Curve= 0 ,0
Skew Angle= 34
Exp/Cntr=0.5,0.3

Type RM Length L Ch R = 3 ,6128.0  ,,,
BEGIN DESCRIPTION:
I-45 NORTH
Structure ID: E100-00-00-09
Bridge has 34 degree skew to the channel.
END DESCRIPTION:
Bridge Culvert--1,0,-1,-1, 0
Deck Dist Width WeirC Skew NumUp NumDn MinLoCord MaxHiCord MaxSubmerge Is_Ogee
10,72,2.6,34, 60, 60, , , 0.95, 0, ,,,
 3028.973153.331 3302.55 3344.01 3443.49 3484.943518.101 3542.98  3609.33650.751
 3700.493833.141 3841.43 3858.01 3877.66 3919.113927.3993935.281 3951.86 3975.07
 4015.44 4030.19 4030.28 4030.37 4220.22 4435.27 4904.924913.209 4927.14 4927.55
 4927.64 4927.884943.799 4952.094960.379 4976.96 4985.25 5001.83 5010.12 5018.41
  5026.75051.569 5093.03 5109.615134.479 5175.93 5209.095217.379 5275.42 5325.16
 5432.93 5681.64 5797.71 6004.976029.839 6071.29 6245.39 6336.58 6361.45 6407.13
    50.1    49.1    50.2      49    48.8    49.9    47.6    47.5    48.5    47.2
      39    27.1    27.2    30.7      33      34    33.5    31.7   34.04   34.45
   34.64   35.55   38.35   38.35   46.08    49.2    58.5   58.66   58.94   58.94
   56.14   55.35    54.3      48    43.4    41.1    41.3    43.9    47.1    53.2
    54.6      53    52.6    49.9    50.9      50    40.2    39.8    40.7    39.6
    40.8    40.2    41.9    42.3    43.1    42.4    44.2    46.2    45.5      47
    50.1    49.1    50.2      49    48.8    49.9    47.6    47.5    48.5    47.2
      39    27.1    27.2    30.7      33      34    33.5    31.7    30.8   33.45
   34.63   29.13    29.1   31.55   39.28    42.4    51.7    52.2    55.4   55.37
   55.37   55.35    54.3      48    43.4    41.1    41.3    43.9    47.1    53.2
    54.6      53    52.6    49.9    50.9      50    40.2    39.8    40.7    39.6
    40.8    40.2    41.9    42.3    43.1    42.4    44.2    46.2    45.5      47
 3028.973153.331 3302.55 3344.01 3443.49 3484.943518.101 3542.98  3609.33650.751
 3700.493833.141 3841.43 3858.01 3877.66 3919.113927.3993935.281 3951.86 3975.07
 4015.44 4030.19 4030.28 4030.37 4220.22 4435.27 4904.924913.209 4927.14 4927.55
 4927.64 4927.884943.799 4952.094960.379 4976.96 4985.25 5001.83 5010.12 5018.41
  5026.75051.569 5093.03 5109.615134.479 5175.93 5209.095217.379 5275.42 5325.16
 5432.93 5681.64 5797.71 6004.976029.839 6071.29 6245.39 6336.58 6361.45 6407.13
    50.1    49.1    50.2      49    48.8    49.9    47.6    47.5    48.5    47.2
      39    27.1    27.2    30.7      33      34    33.5    31.7   34.04   34.45
   34.64   35.55   38.35   38.35   46.08    49.2    58.5   58.66   58.94   58.94
   56.14   55.35    54.3      48    43.4    41.1    41.3    43.9    47.1    53.2
    54.6      53    52.6    49.9    50.9      50    40.2    39.8    40.7    39.6
    40.8    40.2    41.9    42.3    43.1    42.4    44.2    46.2    45.5      47
    50.1    49.1    50.2      49    48.8    49.9    47.6    47.5    48.5    47.2
      39    27.1    27.2    30.7      33      34    33.5    31.7    30.8   33.45
   34.63   29.13    29.1   31.55   39.28    42.4    51.7    52.2    55.4   55.37
   55.37   55.35    54.3      48    43.4    41.1    41.3    43.9    47.1    53.2
    54.6      53    52.6    49.9    50.9      50    40.2    39.8    40.7    39.6
    40.8    40.2    41.9    42.3    43.1    42.4    44.2    46.2    45.5      47
Pier Skew, UpSta & Num, DnSta & Num=  ,4076.129, 2 ,4076.129, 2 , 0 , 0 , 0 ,,
       3       3
   12.12   34.38
       3       3
   12.86   35.12
Pier Skew, UpSta & Num, DnSta & Num=  ,4120.731, 2 ,4120.731, 2 , 0 , 0 , 0 ,,
       3       3
    1.33    36.1
       3       3
    2.07   36.84
Pier Skew, UpSta & Num, DnSta & Num=  ,4178.931, 2 ,4178.931, 2 , 0 , 0 , 0 ,,
       3       3
    5.41    38.6
       3       3
    6.15   39.34
Pier Skew, UpSta & Num, DnSta & Num=  ,4220.547, 2 ,4220.547, 2 , 0 , 0 , 0 ,,
       3       3
   10.95   40.62
       3       3
   11.69   41.36
Pier Skew, UpSta & Num, DnSta & Num=  ,4262.165, 2 ,4262.165, 2 , 0 , 0 , 0 ,,
       3       3
   16.77   42.32
       3       3
   17.51   43.06
Pier Skew, UpSta & Num, DnSta & Num=  ,4303.782, 2 ,4303.782, 2 , 0 , 0 , 0 ,,
       3       3
   23.91    51.7
       3       3
   24.65    51.7
Pier Skew, UpSta & Num, DnSta & Num=  ,4345.4, 2 ,4345.4, 2 , 0 , 0 , 0 ,,
       3       3
   23.91    51.7
       3       3
   24.65    51.7
Pier Skew, UpSta & Num, DnSta & Num=  ,4387.018, 2 ,4387.018, 2 , 0 , 0 , 0 ,,
       3       3
   23.91    51.7
       3       3
   24.65    51.7
Pier Skew, UpSta & Num, DnSta & Num=  ,4428.636, 2 ,4428.636, 2 , 0 , 0 , 0 ,,
       3       3
   23.91    51.7
       3       3
   24.65    51.7
Pier Skew, UpSta & Num, DnSta & Num=  ,4470.253, 2 ,4470.253, 2 , 0 , 0 , 0 ,,
       3       3
   23.91    51.7
       3       3
   24.65    51.7
Pier Skew, UpSta & Num, DnSta & Num=  ,4511.871, 2 ,4511.871, 2 , 0 , 0 , 0 ,,
       3       3
   23.91    51.7
       3       3
   24.65    51.7
Pier Skew, UpSta & Num, DnSta & Num=  ,4553.489, 2 ,4553.489, 2 , 0 , 0 , 0 ,,
       3       3
   23.91    51.7
       3       3
   24.65    51.7
Pier Skew, UpSta & Num, DnSta & Num=  ,4595.106, 2 ,4595.106, 2 , 0 , 0 , 0 ,,
       3       3
   23.91    51.7
       3       3
   24.65    51.7
Pier Skew, UpSta & Num, DnSta & Num=  ,4636.724, 2 ,4636.724, 2 , 0 , 0 , 0 ,,
       3       3
   23.91    51.7
       3       3
   24.65    51.7
Pier Skew, UpSta & Num, DnSta & Num=  ,4678.342, 2 ,4678.342, 2 , 0 , 0 , 0 ,,
       3       3
   23.91    51.7
       3       3
   24.65    51.7
Pier Skew, UpSta & Num, DnSta & Num=  ,4719.959, 2 ,4719.959, 2 , 0 , 0 , 0 ,,
       3       3
   23.91    51.7
       3       3
   24.65    51.7
Pier Skew, UpSta & Num, DnSta & Num=  ,4761.577, 2 ,4761.577, 2 , 0 , 0 , 0 ,,
       3       3
   23.91    51.7
       3       3
   24.65    51.7
Pier Skew, UpSta & Num, DnSta & Num=  ,4803.195, 2 ,4803.195, 2 , 0 , 0 , 0 ,,
       3       3
   23.91    51.7
       3       3
   24.65    51.7
Pier Skew, UpSta & Num, DnSta & Num=  ,4823.921, 2 ,4823.921, 2 , 0 , 0 , 0 ,,
       3       3
   23.91    51.7
       3       3
   24.65    51.7
Pier Skew, UpSta & Num, DnSta & Num=  ,4838.429, 2 ,4838.429, 2 , 0 , 0 , 0 ,,
       3       3
   23.91    51.7
       3       3
   24.65    51.7
Pier Skew, UpSta & Num, DnSta & Num=  ,4852.937, 2 ,4852.937, 2 , 0 , 0 , 0 ,,
       3       3
   23.91    51.7
       3       3
   24.65    51.7
Pier Skew, UpSta & Num, DnSta & Num=  ,4867.445, 2 ,4867.445, 2 , 0 , 0 , 0 ,,
       3       3
   23.91    51.7
       3       3
   24.65    51.7
BR Coef= 1 , 1 , 0 ,1.25, 0 ,,,0.8,0,1.2,0,
WSPro=,,,, 1 ,,,, 0 ,,,, 0 ,,,,-1 ,-1 ,-1 , 0 , 0 , 0 , 0 , 0
BC Design=,, 0 ,, 0 ,,,,,,
BC HTab HWMax=55.42
BC Use User HTab Curves=0
BC User HTab FreeFlow(D)= 0

Type RM Length L Ch R = 1 ,6068.0  ,688.8,543,236.7
BEGIN DESCRIPTION:
Downstream Section of Bridge/Culvert/Weir
N-value adjusted to account for pier outside of sta. 5178
END DESCRIPTION:
XS GIS Cut Line= 6
  3121545.10810713848585.8355938      3120487.22     13848307.68
      3120543.13     13847658.79      3120650.37     13847335.37
      3120618.01     13847198.89 3119040.1049535 13846238.143111
#Sta/Elev= 30
3028.972   50.123650.751   47.223700.492   39.023833.138   27.12 3874.59   32.92
3951.856   30.824006.324   34.384015.443   34.654060.958   15.584106.472   10.84
4131.343   -1.61 4148.67   -3.964160.525   -1.684183.738    10.24294.083   21.74
4469.839   14.624755.691   22.024880.046   31.724888.337   34.424913.208   52.22
4927.882   55.374943.799   54.324960.378   43.424976.961   41.125001.832   43.92
5026.703   54.62 5175.93   50.025217.382   39.826071.291   42.426407.134   47.02
#Mann= 7 ,-1 , 0
3028.972     .99       03650.751     .05       04006.324     .04       0
4106.472    .015       04183.738     .04       04294.083     .06       0
4927.882     .99       0
#XS Ineff= 2 , 0
       03996.757   35.91 5171.26       0   49.92
Permanent Ineff=
       F       F
#Block Obstruct= 1 ,-1
4930.786 5032.15   54.98
Bank Sta=4015.443,4294.083
XS Rating Curve= 0 ,0
Skew Angle= 34
Exp/Cntr=0.5,0.3

Type RM Length L Ch R = 1 ,5525.0  ,612.5,531,234.8
BEGIN DESCRIPTION:
Cross Section E100-00-00-X04
END DESCRIPTION:
XS GIS Cut Line= 5
 3121783.974420713848158.3750509      3121128.45     13847766.67
      3120755.57     13847622.58       3120624.3     13847181.36
 3118952.196520913846178.0275659
#Sta/Elev= 30
  3945.2    49.7  4475.2    48.6  4545.2    42.3  4748.8    38.4  4778.8    32.4
    4788   22.69  4808.8   21.92  4818.8   15.45  4828.8    13.5  4936.3   13.37
  4960.5    9.08    4984   -2.35  4993.3   -3.15    5021     .12  5040.9   11.05
  5057.4   13.49  5518.9   23.38  5538.6    33.4  5548.6    43.8  5558.6    51.4
  5568.6    54.5  5618.9    53.7  5658.9    46.2  5708.9    53.4  5808.9      48
  5878.9    48.3  5928.9    40.3  6058.9    39.9  7028.9      43  7518.9    49.1
#Mann= 6 ,-1 , 0
  3945.2     .08       0  4748.8     .04       0  4936.3    .015       0
  5057.4     .04       0  5518.9     .05       0  5618.9     .99       0
#XS Ineff= 2 , 0
                         5871.69           48.33
Permanent Ineff=
       F       F
#Block Obstruct= 1 ,-1
 5599.13 5703.93   52.59
Bank Sta=4748.8,5548.6
XS Rating Curve= 0 ,0
Exp/Cntr=0.5,0.3

Type RM Length L Ch R = 1 ,4994.0  ,32.7,33,33.1
BEGIN DESCRIPTION:
Upstream Section of Bridge/Culvert/Weir
END DESCRIPTION:
XS GIS Cut Line= 4
 3121854.074174813847508.5825233      3121075.91     13847100.84
      3120786.91     13847242.23  3119128.58044713846217.0074748
#Sta/Elev= 30
  4009.7   47.11  4479.7   42.21  4599.7   44.21  4720.6   26.77  4813.1   25.26
  4843.8   15.72  4874.5   11.83  4920.5   11.91  4963.9    3.11  4975.5   -3.09
  4995.1   -1.12  5050.8   12.35  5101.6   10.85  5114.3   12.99  5173.7   13.51
  5225.5   28.99  5288.3   26.37  5359.6   51.91  5419.6   52.71  5441.7      51
  5469.6   47.81  5509.6   51.31  5589.6   48.91  5619.6   45.31  5689.6   45.51
  5729.6   40.61  6109.6   39.61  6199.6   41.31  6979.6   43.71  7159.6   48.61
#Mann= 4 ,-1 , 0
  4009.7     .08       0  4813.1     .04       0  5225.5     .05       0
  5441.7     .99       0
#XS Ineff= 2 , 0
       0 4557.21    46.7 5379.91       0   53.02
Permanent Ineff=
       F       F
#Block Obstruct= 1 ,-1
 5411.35 5510.92   50.84
Bank Sta=4813.1,5225.5
XS Rating Curve= 0 ,0
Exp/Cntr=0.5,0.3

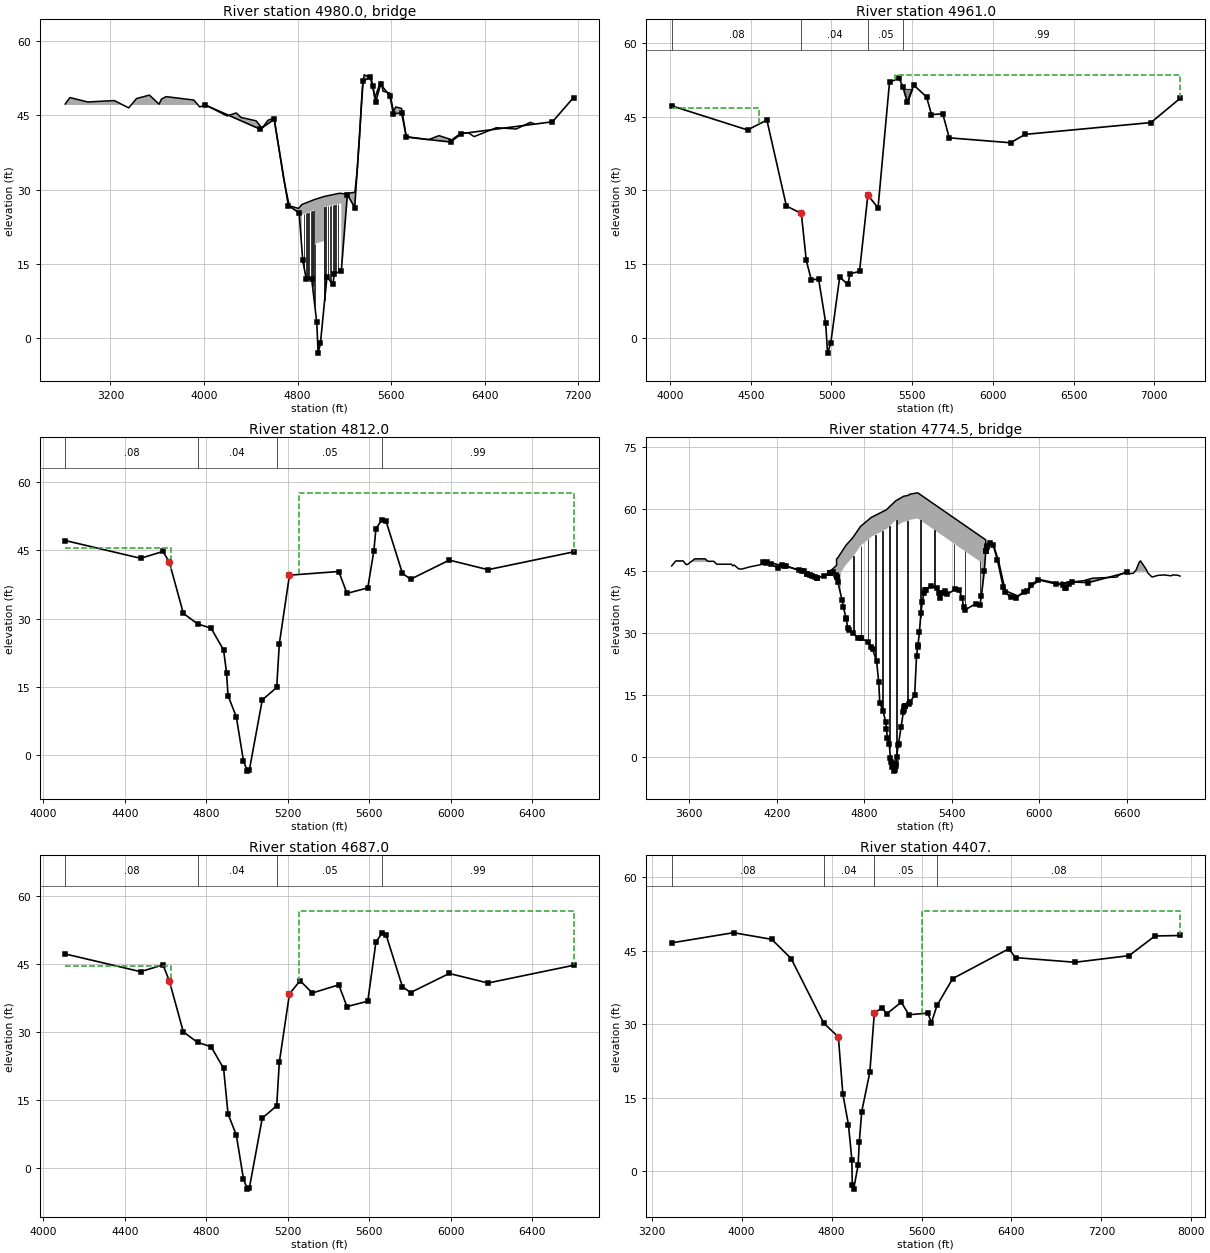
Type RM Length L Ch R = 3 ,4980.0  ,,,
BEGIN DESCRIPTION:
RAILROAD OVERPASS  E100-00-00-8
Structure ID: E100-00-00-8
END DESCRIPTION:
Bridge Culvert--1,0,-1,-1, 0
Deck Dist Width WeirC Skew NumUp NumDn MinLoCord MaxHiCord MaxSubmerge Is_Ogee
10,8,2.6,0, 60, 60, , , 0.95, 0, ,,,
  2812.7  2852.7  3005.6  3232.7  3355.6  3422.7  3532.7  3615.6  3635.6  3675.6
  3912.7  3962.7  4012.7  4195.6  4275.6  4315.6  4445.6  4495.6  4545.6  4592.7
  4602.7  4682.7  4720.6  4732.3  4808.7 4836.81  4836.9  4947.1  4947.2  5030.9
    5031  5157.5  5173.7 5199.39  5289.5  5309.5  5329.5  5349.5  5359.5  5369.5
  5429.5  5459.4  5509.5  5519.5  5529.5  5589.5  5619.5  5639.5  5689.5  5729.5
  5919.5  6009.5  6119.5  6189.4  6259.4  6309.4  6499.5  6669.5  6789.4  6823.8
47.30025   48.61   47.72   48.01   46.52   48.41   49.11   47.28    48.3    48.8
   48.11   46.71   47.11    44.9    45.5    44.6    43.9    42.4      44   44.41
   43.91   31.91   27.65   26.68   26.19   26.98   26.98   28.01   28.01   28.62
   28.62   29.25   29.21   29.15   29.44   33.81   40.51   49.11   52.01   53.21
   52.61    48.5   51.81   51.41   49.91   49.51   45.81   46.71   46.41   40.71
    40.1   40.91   40.06    41.3    41.5   40.71   42.51   42.25    43.6    43.3
                                                                                
                                                                                
                                                   24.89   25.92   19.01   19.62
   26.53   27.16   27.12
                                                                                
                                                                                
  2812.7  2852.7  3005.6  3232.7  3355.6  3422.7  3532.7  3615.6  3635.6  3675.6
  3912.7  3962.7  4012.7  4195.6  4275.6  4315.6  4445.6  4495.6  4545.6  4592.7
  4602.7  4682.7  4720.6  4732.3  4808.7 4836.81  4836.9  4947.1  4947.2  5030.9
    5031  5157.5  5173.7 5199.39  5289.5  5309.5  5329.5  5349.5  5359.5  5369.5
  5429.5  5459.4  5509.5  5519.5  5529.5  5589.5  5619.5  5639.5  5689.5  5729.5
  5919.5  6009.5  6119.5  6189.4  6259.4  6309.4  6499.5  6669.5  6789.4  6823.8
47.36025   48.61   47.72   48.01   46.52   48.41   49.11   47.28    48.3    48.8
   48.11   46.71   47.11    44.9    45.5    44.6    43.9    42.4      44   44.41
   43.91   31.91   27.65   26.68   26.19   26.98   26.98   28.01   28.01   28.62
   28.62   29.25   29.21   29.15   29.44   33.81   40.51   49.11   52.01   53.21
   52.61    48.5   51.81   51.41   49.91   49.51   45.81   46.71   46.41   40.71
    40.1   40.91   40.06    41.3    41.5   40.71   42.51   42.25    43.6    43.3
                                                                                
                                                                                
                                                   24.89   25.92   19.01   19.62
   26.53   27.16   27.12
                                                                                
                                                                                
Pier Skew, UpSta & Num, DnSta & Num=  ,4858, 2 ,4858, 2 , 0 , 0 , 0 ,,
       1       1
   12.86   26.34
       1       1
   12.95   26.43
Pier Skew, UpSta & Num, DnSta & Num=  ,4871.1, 2 ,4871.1, 2 , 0 , 0 , 0 ,,
       1       1
    11.2   26.53
       1       1
   11.29   26.62
Pier Skew, UpSta & Num, DnSta & Num=  ,4885.1, 2 ,4885.1, 2 , 0 , 0 , 0 ,,
       1       1
   10.85   26.73
       1       1
   10.94   26.82
Pier Skew, UpSta & Num, DnSta & Num=  ,4899.5, 2 ,4899.5, 2 , 0 , 0 , 0 ,,
       1       1
   10.87   26.76
       1       1
   10.96   26.85
Pier Skew, UpSta & Num, DnSta & Num=  ,4913.1, 2 ,4913.1, 2 , 0 , 0 , 0 ,,
       1       1
    10.9   26.79
       1       1
   10.99   26.88
Pier Skew, UpSta & Num, DnSta & Num=  ,4927.6, 2 ,4927.6, 2 , 0 , 0 , 0 ,,
       1       1
    9.11   26.81
       1       1
     9.2    26.9
Pier Skew, UpSta & Num, DnSta & Num=  ,4941.1, 2 ,4941.1, 2 , 0 , 0 , 0 ,,
       1       1
     6.2   26.86
       1       1
    6.29   26.95
Pier Skew, UpSta & Num, DnSta & Num=  ,4947.2, 2 ,4947.2, 2 , 0 , 0 , 0 ,,
       3       3
    4.94   26.94
       3       3
    5.03   27.03
Pier Skew, UpSta & Num, DnSta & Num=  ,5031, 2 ,5031, 2 , 0 , 0 , 0 ,,
       3       3
    5.62   27.55
       3       3
    5.71   27.64
Pier Skew, UpSta & Num, DnSta & Num=  ,5045.1, 2 ,5045.1, 2 , 0 , 0 , 0 ,,
       1       1
    9.02   27.59
       1       1
    9.11   27.68
Pier Skew, UpSta & Num, DnSta & Num=  ,5059.7, 2 ,5059.7, 2 , 0 , 0 , 0 ,,
       1       1
   11.07   27.64
       1       1
   11.16   27.73
Pier Skew, UpSta & Num, DnSta & Num=  ,5073.3, 2 ,5073.3, 2 , 0 , 0 , 0 ,,
       1       1
   10.67    27.7
       1       1
   10.76   27.79
Pier Skew, UpSta & Num, DnSta & Num=  ,5087.6, 2 ,5087.6, 2 , 0 , 0 , 0 ,,
       1       1
   10.25   27.78
       1       1
   10.34   27.87
Pier Skew, UpSta & Num, DnSta & Num=  ,5101.6, 2 ,5101.6, 2 , 0 , 0 , 0 ,,
       1       1
    9.86   27.86
       1       1
    9.95   27.95
Pier Skew, UpSta & Num, DnSta & Num=  ,5115.7, 2 ,5115.7, 2 , 0 , 0 , 0 ,,
       1       1
      12   27.94
       1       1
   12.09   28.03
Pier Skew, UpSta & Num, DnSta & Num=  ,5130, 2 ,5130, 2 , 0 , 0 , 0 ,,
       1       1
   12.12   28.02
       1       1
   12.21   28.11
Pier Skew, UpSta & Num, DnSta & Num=  ,5143.5, 2 ,5143.5, 2 , 0 , 0 , 0 ,,
       1       1
   12.24   28.09
       1       1
   12.33   28.18
Abutment Skew #Up #Dn= , 2 , 2
  4836.9    4857
   24.85   13.84
  4836.9    4857
   24.85   13.84
Abutment Skew #Up #Dn= , 2 , 2
  5145.5  5173.7
      13   27.25
  5145.5  5173.7
      13   27.25
BR Coef= 1 , 1 , 0 ,1.25, 0 ,,,0.8,0,1.2,0,
WSPro=,,,, 1 ,,,, 0 ,,,, 0 ,,,,-1 ,-1 ,-1 , 0 , 0 , 0 , 0 , 0
BC Design=,, 0 ,, 0 ,,,,,,
BC HTab HWMax=52.91
BC Use User HTab Curves=0
BC User HTab FreeFlow(D)= 0

Type RM Length L Ch R = 1 ,4961.0  ,21.3,149,321.3
BEGIN DESCRIPTION:
Downstream Section of Bridge/Culvert/Weir
END DESCRIPTION:
XS GIS Cut Line= 4
 3121852.502525513847473.8916324      3121076.38     13847067.22
      3120788.99     13847207.81 3119119.559371713846192.7482309
#Sta/Elev= 30
  4009.7   47.17  4479.7   42.27  4599.7   44.27  4720.6   26.83  4813.1   25.32
  4843.8   15.78  4874.5   11.89  4920.5   11.97  4963.9    3.17  4975.5   -3.03
  4995.1   -1.06  5050.8   12.41  5101.6   10.91  5114.3   13.05  5173.7   13.57
  5225.5   29.05  5288.3   26.43  5359.6   51.97  5419.6   52.77  5441.7   51.06
  5469.6   47.87  5509.6   51.37  5589.6   48.97  5619.6   45.37  5689.6   45.57
  5729.6   40.67  6109.6   39.67  6199.6   41.37  6979.6   43.77  7159.6   48.67
#Mann= 4 ,-1 , 0
  4009.7     .08       0  4813.1     .04       0  5225.5     .05       0
  5441.7     .99       0
#XS Ineff= 2 , 0
       0 4551.96    46.7 5395.63       0   53.46
Permanent Ineff=
       F       F
#Block Obstruct= 1 ,-1
 5411.35 5510.92   50.62
Bank Sta=4813.1,5225.5
XS Rating Curve= 0 ,0
Exp/Cntr=0.5,0.3

Type RM Length L Ch R = 1 ,4812.0  ,124,125,127.8
BEGIN DESCRIPTION:
Upstream Section of Bridge/Culvert/Weir
END DESCRIPTION:
XS GIS Cut Line= 6
 3121780.452630113847390.9147629      3121078.06     13847046.65
      3120978.26     13846965.56      3120813.68     13846848.28
      3120472.93     13846817.13 3119625.207814813846214.4463093
#Sta/Elev= 30
  4106.8   47.13  4476.8   43.23  4586.8   44.73  4617.7    42.4  4686.8   31.13
  4756.8   28.83  4822.9   27.89  4884.3    23.1  4898.8   18.07    4906   13.09
  4946.8    8.41  4981.9   -1.28  5000.9   -3.49  5010.8   -3.23  5074.1   12.14
    5145   14.88  5157.7   24.43  5207.7   39.53  5449.8   40.33  5489.8   35.53
    5592   36.73    5622   44.93    5632   49.73    5662   51.73    5682   51.33
    5762   39.93    5802   38.63    5992   42.83    6182   40.73    6602   44.63
#Mann= 4 ,-1 , 0
  4106.8     .08       0  4756.8     .04       0    5145     .05       0
    5662     .99       0
#XS Ineff= 2 , 0
       0 4627.48    45.5 5253.14       0    57.6
Permanent Ineff=
       F       F
Bank Sta=4617.7,5207.7
XS Rating Curve= 0 ,0
Exp/Cntr=0.5,0.3

Type RM Length L Ch R = 3 ,4774.5  ,,,
BEGIN DESCRIPTION:
CROCKETT/HOGAN
Structure ID: E100-00-00-07
Area to the right of sta. 5181 is ineffective because of upstream and downstream obstructions.  The pier information ouside of this station is not included because the flow is considered ineffective.
END DESCRIPTION:
Bridge Culvert--1,0,-1,-1, 0
Deck Dist Width WeirC Skew NumUp NumDn MinLoCord MaxHiCord MaxSubmerge Is_Ogee
61,55,2.6,0, 173, 173, , , 0.95, 0, ,,,
  3480.4  3508.9  3558.9  3578.9  3588.9  3638.9  3708.9  3728.9  3730.4  3768.9
  3788.9  3810.4  3820.4  3830.4  3860.4  3880.4  3888.9  3898.9  3908.9  3910.4
  3938.9  3960.4  3978.9  4020.4  4138.9  4160.4  4208.9  4250.4  4260.4  4350.4
  4370.4  4388.9  4410.4  4430.4  4440.4  4460.4  4468.9  4473.2  4508.9  4523.2
  4528.9 4565.99  4566.1 4566.21  4566.3  4588.9  4608.9 4609.91    4610  4617.7
  4638.9  4658.9  4675.2  4678.9  4688.9  4720.4  4728.9  4758.9  4774.5  4822.9
  4847.1  4857.4  4884.3  4898.8    4906  4928.3  4946.8    4952  4958.1  4970.6
  4979.2  4981.9  4987.9  5000.9  5010.8  5014.4  5016.9  5020.8  5021.8  5031.9
  5034.5  5051.9  5067.7  5069.8  5104.6  5110.6    5145  5157.7  5166.1  5167.7
  5177.7  5187.7  5197.7  5207.7  5217.7  5219.8  5259.8  5299.8  5309.2  5319.8
  5329.8  5349.8  5369.8  5419.8  5449.8  5469.8  5479.8  5489.8    5562    5592
    5602    5622    5632 5632.09  5632.2    5640    5641    5642    5651    5661
    5662    5692    5701    5721    5722    5741    5752    5762    5772    5841
    5852    5902    5911    5931    5941    5981    5992    6012    6071    6141
    6151    6171    6222    6252    6272    6292    6302    6362    6531    6541
    6542    6552    6591    6612    6642    6661    6662    6681    6682    6691
    6692    6711    6732    6742    6771    6772    6811    6852    6901    6902
    6912  6946.5  6962.6
    46.2   47.41   47.41   46.52   46.55   47.91   47.91   47.31   47.31   47.31
   46.61   46.61   46.61   46.61   46.61   46.61   46.61   46.21   46.41   46.35
   45.49   45.43   45.61      46   46.85      47   46.51    46.1    46.3    45.1
    45.3   45.02    44.7    44.2    44.4    43.9   43.57   43.41    43.6    43.7
   43.84   44.85   44.85   44.85   44.85   45.63   46.33   46.36   47.86   48.13
   49.27   50.34   51.22   51.37   51.76      53   53.44   54.97   55.77    57.2
   57.92   58.11   58.59   58.85   58.98   59.38   59.72   59.81   60.02   60.44
   60.73   60.83   61.03   61.47   61.81   61.93   61.98   62.06   62.08   62.29
   62.34   62.69   63.02   63.06    63.3   63.56   63.76   63.84   63.89   63.85
   63.61   63.36   63.12   62.87   62.63   62.58    61.6   60.62   60.39   60.13
   59.89    59.4   58.91   57.69   56.95   56.46   56.22   55.97   54.21   53.47
   53.23   52.74    52.5   50.99   50.99    50.8   50.86   51.01   51.24   51.49
   51.51   50.51   49.49   47.22   47.11   44.07   42.31   40.91   40.11   39.08
   38.94   40.01    40.2   40.51    41.3   42.23   42.61   42.81   42.39   41.89
    42.3    42.1    42.3   42.42   42.49   42.57   42.61   43.21    43.5    43.9
   43.92   44.08    44.7   44.31   44.41   45.17   45.21   46.92   47.01   47.37
   47.41   46.41   45.31   44.51    43.5   43.51    43.9   44.01    43.8    43.8
   44.01   43.94   43.73
                                                                                
                                                                                
                                                                                
                                                                                
                                                                                
   44.57   45.64   46.52   46.67   47.06    48.3   48.74   50.27   51.07    52.5
   53.22   53.41   53.89   54.15   54.28   54.68   55.02   55.11   55.32   55.74
   56.03   56.13   56.33   56.77   57.11   57.23   57.28   57.36   57.38   56.09
   56.14   56.49   56.82   56.86    57.1   57.36   57.56   57.64   57.69   57.65
   57.41   57.16   56.92   56.67   56.43   56.38    55.4   54.42   54.19   53.93
   53.69    53.2   52.71   51.49   50.75   50.26   50.02   49.77   48.01   47.27
   47.03
                                                                                
                                                                                
                                                                                
                                                                                
                                                                                
                        
  3480.4  3508.9  3558.9  3578.9  3588.9  3638.9  3708.9  3728.9  3730.4  3768.9
  3788.9  3810.4  3820.4  3830.4  3860.4  3880.4  3888.9  3898.9  3908.9  3910.4
  3938.9  3960.4  3978.9  4020.4  4138.9  4160.4  4208.9  4250.4  4260.4  4350.4
  4370.4  4388.9  4410.4  4430.4  4440.4  4460.4  4468.9  4473.2  4508.9  4523.2
  4528.9 4565.99  4566.1 4566.21  4566.3  4588.9  4608.9 4609.91    4610  4617.7
  4638.9  4658.9  4675.2  4678.9  4688.9  4720.4  4728.9  4758.9  4774.5  4822.9
  4847.1  4857.4  4884.3  4898.8    4906  4928.3  4946.8    4952  4958.1  4970.6
  4979.2  4981.9  4987.9  5000.9  5010.8  5014.4  5016.9  5020.8  5021.8  5031.9
  5034.5  5051.9  5067.7  5069.8  5104.6  5110.6    5145  5157.7  5166.1  5167.7
  5177.7  5187.7  5197.7  5207.7  5217.7  5219.8  5259.8  5299.8  5309.2  5319.8
  5329.8  5349.8  5369.8  5419.8  5449.8  5469.8  5479.8  5489.8    5562    5592
    5602    5622    5632 5632.09  5632.2    5640    5641    5642    5651    5661
    5662    5692    5701    5721    5722    5741    5752    5762    5772    5841
    5852    5902    5911    5931    5941    5981    5992    6012    6071    6141
    6151    6171    6222    6252    6272    6292    6302    6362    6531    6541
    6542    6552    6591    6612    6642    6661    6662    6681    6682    6691
    6692    6711    6732    6742    6771    6772    6811    6852    6901    6902
    6912  6946.5  6962.6
    46.2   47.41   47.41   46.52   46.55   47.91   47.91   47.31   47.31   47.31
   46.61   46.61   46.61   46.61   46.61   46.61   46.61   46.21   46.41   46.35
   45.49   45.43   45.61      46   46.85      47   46.51    46.1    46.3    45.1
    45.3   45.02    44.7    44.2    44.4    43.9   43.57   43.41    43.6    43.7
   43.84   44.85   44.85   44.85   44.85   45.63   46.33   46.36   47.86   48.13
   49.27   50.34   51.22   51.37   51.76      53   53.44   54.97   55.77    57.2
   57.92   58.11   58.59   58.85   58.98   59.38   59.72   59.81   60.02   60.44
   60.73   60.83   61.03   61.47   61.81   61.93   61.98   62.06   62.08   62.29
   62.34   62.69   63.02   63.06    63.3   63.56   63.76   63.84   63.89   63.85
   63.61   63.36   63.12   62.87   62.63   62.58    61.6   60.62   60.39   60.13
   59.89    59.4   58.91   57.69   56.95   56.46   56.22   55.97   54.21   53.47
   53.23   52.74    52.5   50.99   50.99    50.8   50.86   51.01   51.24   51.49
   51.51   50.51   49.49   47.22   47.11   44.07   42.31   40.91   40.11   39.08
   38.94   40.01    40.2   40.51    41.3   42.23   42.61   42.81   42.39   41.89
    42.3    42.1    42.3   42.42   42.49   42.57   42.61   43.21    43.5    43.9
   43.92   44.08    44.7   44.31   44.41   45.17   45.21   46.92   47.01   47.37
   47.41   46.41   45.31   44.51    43.5   43.51    43.9   44.01    43.8    43.8
   44.01   43.94   43.73
                                                                                
                                                                                
                                                                                
                                                                                
                                                                                
   44.57   45.64   46.52   46.67   47.06    48.3   48.74   50.27   51.07    52.5
   53.22   53.41   53.89   54.15   54.28   54.68   55.02   55.11   55.32   55.74
   56.03   56.13   56.33   56.77   57.11   57.23   57.28   57.36   57.38   56.09
   56.14   56.49   56.82   56.86    57.1   57.36   57.56   57.64   57.69   57.65
   57.41   57.16   56.92   56.67   56.43   56.38    55.4   54.42   54.19   53.93
   53.69    53.2   52.71   51.49   50.75   50.26   50.02   49.77   48.01   47.27
   47.03
                                                                                
                                                                                
                                                                                
                                                                                
                                                                                
                        
Pier Skew, UpSta & Num, DnSta & Num=  ,4726.7, 2 ,4726.7, 2 , 0 , 0 , 0 ,,
       3       3
   26.57   53.66
       3       3
    25.4   52.49
Pier Skew, UpSta & Num, DnSta & Num=  ,4776.7, 2 ,4776.7, 2 , 0 , 0 , 0 ,,
       3       3
   26.57   53.66
       3       3
    25.4   52.49
Pier Skew, UpSta & Num, DnSta & Num=  ,4826.7, 2 ,4826.7, 2 , 0 , 0 , 0 ,,
       3       3
   26.57   53.66
       3       3
    25.4   52.49
Pier Skew, UpSta & Num, DnSta & Num=  ,4876.7, 2 ,4876.7, 2 , 0 , 0 , 0 ,,
       3       3
   22.73   54.78
       3       3
   21.56   53.61
Pier Skew, UpSta & Num, DnSta & Num=  ,4923.7, 2 ,4923.7, 2 , 0 , 0 , 0 ,,
       3       3
   10.33   55.62
       3       3
    9.16   54.45
Pier Skew, UpSta & Num, DnSta & Num=  ,4972.7, 2 ,4972.7, 2 , 0 , 0 , 0 ,,
       4       4
     .43   56.88
       4       4
    -.74   55.71
Pier Skew, UpSta & Num, DnSta & Num=  ,5021.9, 2 ,5021.9, 2 , 0 , 0 , 0 ,,
       4       4
   -1.49   58.42
       4       4
   -2.66   57.25
Pier Skew, UpSta & Num, DnSta & Num=  ,5095.9, 2 ,5095.9, 2 , 0 , 0 , 0 ,,
       3       3
   11.57   59.28
       3       3
    10.4   58.11
Pier Skew, UpSta & Num, DnSta & Num=  ,5185.9, 2 ,5185.9, 2 , 0 , 0 , 0 ,,
       3       3
       0      60
       3       3
       0      60
Pier Skew, UpSta & Num, DnSta & Num=  ,5280.9, 2 ,5280.9, 2 , 0 , 0 , 0 ,,
       3       3
       0      60
       3       3
       0      60
Pier Skew, UpSta & Num, DnSta & Num=  ,5415.9, 2 ,5415.9, 2 , 0 , 0 , 0 ,,
       3       3
       0      60
       3       3
       0      60
Pier Skew, UpSta & Num, DnSta & Num=  ,5490.9, 2 ,5490.9, 2 , 0 , 0 , 0 ,,
       3       3
       0      60
       3       3
       0      60
Pier Skew, UpSta & Num, DnSta & Num=  ,5590.9, 2 ,5590.9, 2 , 0 , 0 , 0 ,,
       3       3
       0      60
       3       3
       0      60
BR Coef= 1 , 1 , 0 ,1.25, 0 ,,,0.8,0,1.2,1,
WSPro=,,,, 1 ,,,, 0 ,,,, 0 ,,,,-1 ,-1 ,-1 , 0 , 0 , 0 , 0 , 0
BR U #Sta/Elev= 118
  4106.8   47.13  4126.8   46.83  4136.8   47.03  4160.4   46.59  4206.8   45.73
  4236.8   46.33  4250.4    46.2  4260.4   46.11  4350.4   45.27  4370.4   45.08
  4386.8   44.93  4406.8   44.23  4410.4   44.18  4430.4   43.89  4440.4   43.75
  4460.4   43.46  4473.2   43.28  4476.8   43.23  4523.2   43.86 4565.99   44.45
  4566.1   44.45 4566.21   44.45  4566.3   44.45  4586.8   44.73  4606.8   44.03
 4609.91   43.56    4610   43.55  4617.7    42.4  4646.8   38.03  4656.8   36.23
  4675.2   33.47  4676.8   33.23  4686.8   31.13  4696.8   30.63  4720.4   29.92
  4756.8   28.83  4774.5   28.65  4776.8   28.63  4822.9   27.89  4847.1   26.56
  4857.4      26  4884.3    23.1  4898.8   18.07    4906   13.09  4928.3   11.08
  4946.8    8.41    4952    6.61  4958.1     4.5  4970.6    3.02  4979.2    -.25
  4981.9   -1.28  4987.9   -2.51  5000.9   -3.49  5010.8   -3.23  5014.4   -2.24
  5016.9   -1.55  5020.8    -.13  5031.9    2.77  5034.5     3.1  5051.9    7.22
  5067.6   10.83  5069.8   11.27  5074.1   12.14 5078.79   12.25  5078.9   12.25
 5079.01   12.25  5104.6   12.84  5110.6   13.14    5145   14.88  5157.7   24.43
  5166.1   26.61  5167.7   27.03  5177.7   30.23  5187.7   34.73  5197.7   37.53
  5207.7   39.53  5217.7   40.33  5219.8   40.43  5259.8   41.23  5299.8   40.83
  5309.2   39.75  5319.8   38.53  5329.8   39.63  5349.8   40.23  5369.8   39.33
  5419.8   40.53  5449.8   40.33  5469.8   38.43  5479.8   36.33  5489.8   35.53
    5562   37.03    5592   36.73    5602   38.83    5622   44.93    5632   49.73
 5632.09   49.74  5632.2   49.76    5640   50.85    5642   51.13    5662   51.73
    5682   51.33    5712   47.63    5752   41.03    5762   39.93    5802   38.63
    5842   38.53    5892   39.83    5912   40.03    5942   41.63    5992   42.83
    6112   41.83    6162   41.63    6172   40.93    6182   40.73    6202   41.93
    6222   42.33    6332   42.13    6602   44.63
BR U #Mann= 4
  4106.8     .08  4756.8     .04    5145     .05    5662     .99
BR D #Sta/Elev= 118
  4106.8   47.13  4126.8   46.83  4136.8   47.03  4160.4   46.59  4206.8   45.73
  4236.8   46.33  4250.4    46.2  4260.4   46.11  4350.4   45.27  4370.4   45.08
  4386.8   44.93  4406.8   44.23  4410.4   44.18  4430.4   43.89  4440.4   43.75
  4460.4   43.46  4473.2   43.28  4476.8   43.23  4523.2   43.86 4565.99   44.45
  4566.1   44.45 4566.21   44.45  4566.3   44.45  4586.8   44.73  4606.8   44.03
 4609.91   43.56    4610   43.55  4617.7   41.22  4646.8   36.85  4656.8   35.05
  4675.2   32.29  4676.8   32.05  4686.8   29.95  4696.8   29.45  4720.4   28.74
  4756.8   27.65  4774.5   27.47  4776.8   27.45  4822.9   26.71  4847.1   25.38
  4857.4   24.82  4884.3   21.92  4898.8   16.89    4906   11.91  4928.3     9.9
  4946.8    7.23    4952    5.43  4958.1    3.32  4970.6    1.84  4979.2   -1.43
  4981.9   -2.46  4987.9   -3.69  5000.9   -4.67  5010.8   -4.41  5014.4   -3.42
  5016.9   -2.73  5020.8   -1.31  5031.9    1.59  5034.5    1.92  5051.9    6.04
  5067.6    9.65  5069.8   10.09  5074.1   10.96 5078.79   11.07  5078.9   11.07
 5079.01   11.07  5104.6   11.66  5110.6   11.96    5145    13.7  5157.7   23.25
  5166.1   25.43  5167.7   25.85  5177.7   29.05  5187.7   33.55  5197.7   36.35
  5207.7   38.35  5217.7   40.33  5219.8   40.43  5259.8   41.23  5299.8   40.83
  5309.2   39.75  5319.8   38.53  5329.8   39.63  5349.8   40.23  5369.8   39.33
  5419.8   40.53  5449.8   40.33  5469.8   38.43  5479.8   36.33  5489.8   35.53
    5562   37.03    5592   36.73    5602   38.83    5622   44.93    5632   49.73
 5632.09   49.74  5632.2   49.76    5640   50.85    5642   51.13    5662   51.73
    5682   51.33    5712   47.63    5752   41.03    5762   39.93    5802   38.63
    5842   38.53    5892   39.83    5912   40.03    5942   41.63    5992   42.83
    6112   41.83    6162   41.63    6172   40.93    6182   40.73    6202   41.93
    6222   42.33    6332   42.13    6602   44.63
BR D #Mann= 4
  4106.8     .08  4756.8     .04    5145     .05    5662     .99
BC Design=,, 0 ,, 0 ,,,,,,
BC HTab HWMax=51.73
BC Use User HTab Curves=0
BC User HTab FreeFlow(D)= 0

Type RM Length L Ch R = 1 ,4687.0  ,299.5,280,229
BEGIN DESCRIPTION:
Downstream Section of Bridge/Culvert/Weir
END DESCRIPTION:
XS GIS Cut Line= 6
 3121859.276701613847292.2636954      3121153.03     13846946.11
      3121055.15     13846866.58      3120883.19     13846744.04
      3120542.43     13846712.89 3119703.581354813846116.5171396
#Sta/Elev= 30
  4106.8   47.13  4476.8   43.23  4586.8   44.73  4617.7   41.22  4686.8   29.95
  4756.8   27.65  4822.9   26.71  4884.3   21.92    4906   11.91  4946.8    7.23
  4981.9   -2.46  5000.9   -4.67  5010.8   -4.41  5074.1   10.96    5145    13.7
  5157.7   23.25  5207.7   38.35  5259.8   41.23  5319.8   38.53  5449.8   40.33
  5489.8   35.53    5592   36.73    5632   49.73    5662   51.73    5682   51.33
    5762   39.93    5802   38.63    5992   42.83    6182   40.73    6602   44.63
#Mann= 4 ,-1 , 0
  4106.8     .08       0  4756.8     .04       0    5145     .05       0
    5662     .99       0
#XS Ineff= 2 , 0
       0 4627.48   44.51 5253.14       0   56.63
Permanent Ineff=
       F       F
Bank Sta=4617.7,5207.7
XS Rating Curve= 0 ,0
Exp/Cntr=0.5,0.3

Type RM Length L Ch R = 1 ,4407.   ,455.7,393,280.4
BEGIN DESCRIPTION:
Union Pacific RR4 - U/S - XS 4
END DESCRIPTION:
XS GIS Cut Line= 5
      3122753.42     13847381.31      3121801.12     13846956.87
      3120880.93     13846500.34        3120189.     13846346.98
      3118748.07     13845366.15
#Sta/Elev= 30
  3377.4    46.6  3927.4   48.67  4267.4   47.32    4440    43.4    4730   30.23
    4860   27.42    4900   15.78    4950    9.49    4980    2.41  4983.7   -2.77
 4996.16   -3.62 5035.61    1.25 5046.29       6 5068.12    12.2    5140   20.21
    5180   32.31    5250   33.35    5290   32.12    5420    34.5  5487.2   31.94
  5657.2   32.27  5687.2   30.26  5737.2   33.83  5877.2   39.31  6375.9   45.38
  6435.9   43.59  6965.9   42.64  7445.9   43.99  7675.9      48    7899    48.1
#Mann= 4 ,-1 , 0
  3377.4     .08       0    4730     .04       0    5180     .05       0
  5737.2     .08       0
#XS Ineff= 2 , 0
       0                    5605       053.13104
Permanent Ineff=
       F       F
Bank Sta=4860,5180
XS Rating Curve= 0 ,0
Exp/Cntr=0.5,0.3

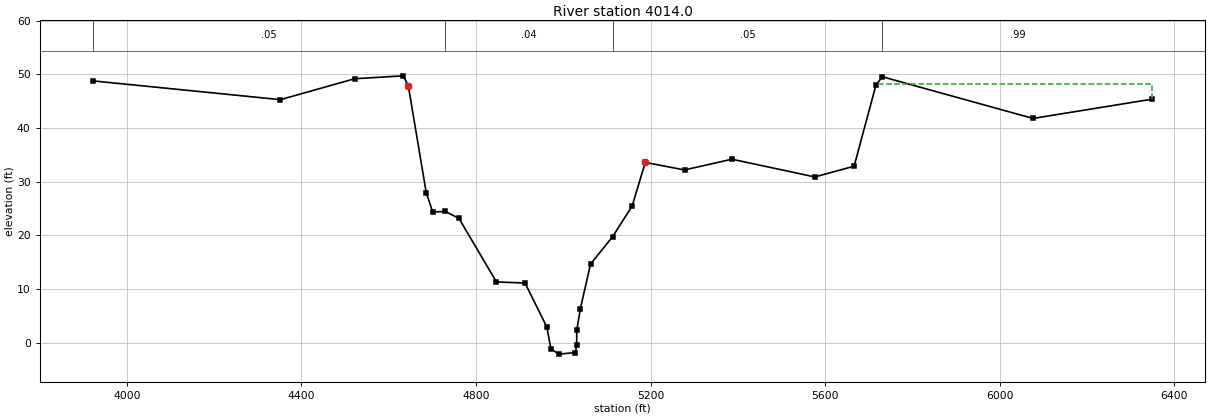
Type RM Length L Ch R = 1 ,4014.0  ,37.6,38,38.9
BEGIN DESCRIPTION:
Upstream Section of Bridge/Culvert/Weir
END DESCRIPTION:
XS GIS Cut Line= 6
 3122335.371404813846811.2484682      3121751.59     13846355.21
      3121487.46     13846332.77      3121079.05     13846322.93
      3120186.61     13846279.65 3120087.585478713846211.9022624
#Sta/Elev= 30
    3922   48.77    4352   45.27    4522   49.17  4633.5   49.71    4645   47.83
    4686   27.96  4700.9   24.34    4730   24.43  4761.1   23.13  4846.9    11.3
  4912.4    11.1  4962.1    2.94  4971.8   -1.14  4989.5   -2.15    5028   -1.86
  5030.7    -.38  5030.9    2.26  5039.1    6.28  5062.4   14.62    5113   19.72
  5157.9   25.47  5187.9   33.57  5277.9   32.17  5386.4   34.17  5576.4   30.87
  5666.4   32.87  5716.4   47.97  5730.9   49.54  6076.4   41.77  6349.9   45.37
#Mann= 4 ,-1 , 0
    3922     .05       0    4730     .04       0    5113     .05       0
  5730.9     .99       0
#XS Ineff= 2 , 0
       0 4628.82   48.68 5722.02       0   48.22
Permanent Ineff=
       F       F
Bank Sta=4645,5187.9
XS Rating Curve= 0 ,0
Exp/Cntr=0.5,0.3