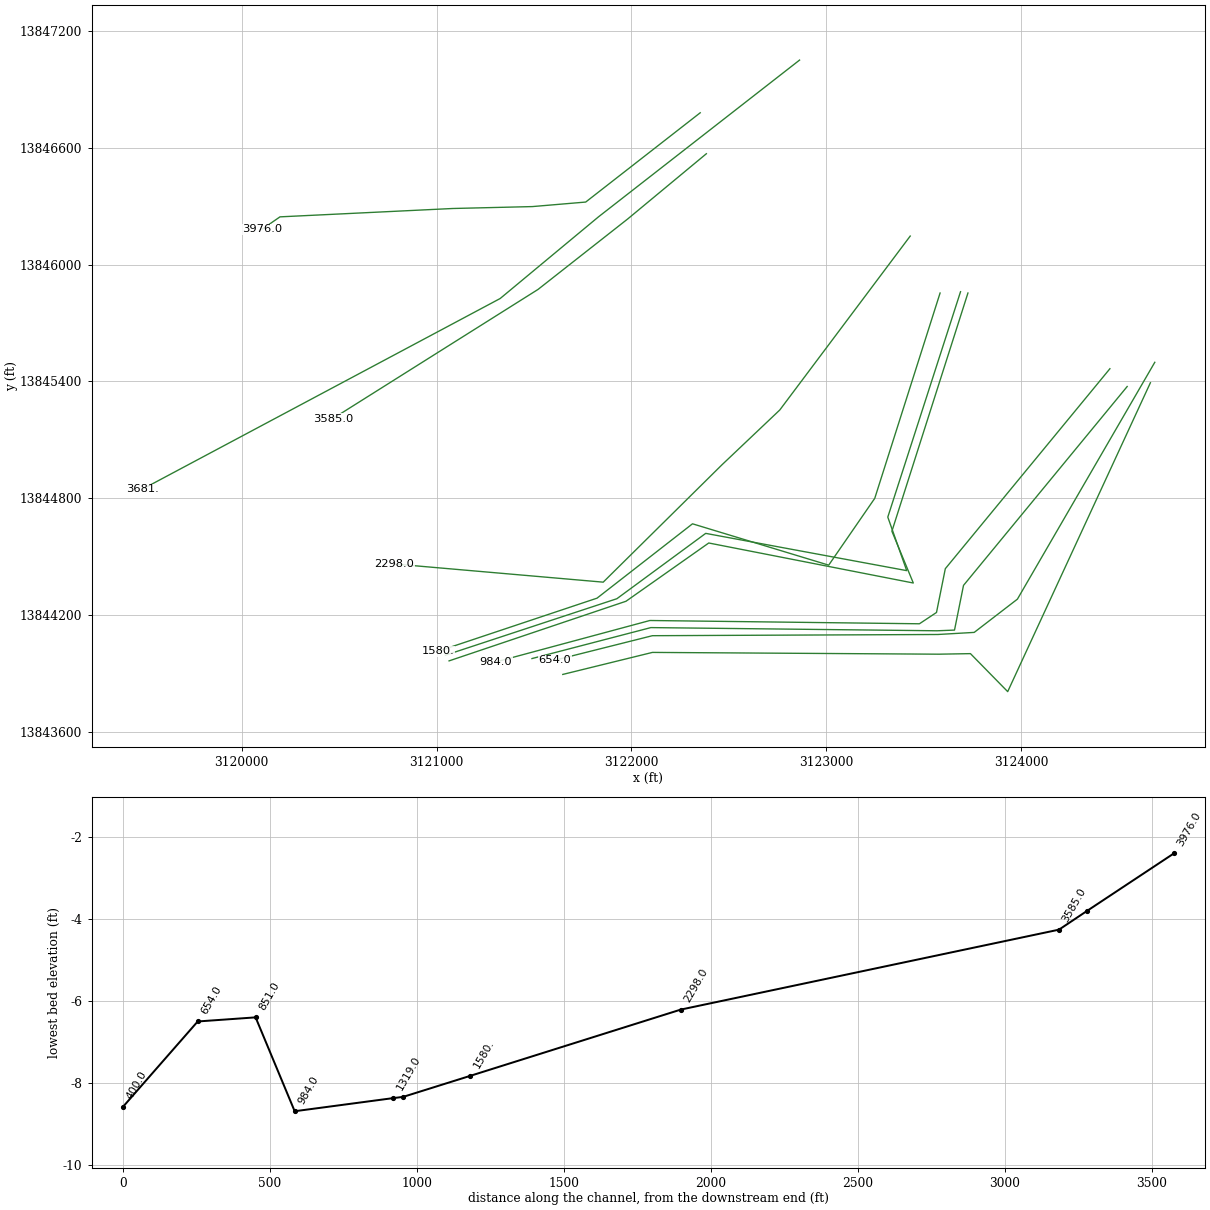
HEC-RAS study E100-00-00.prj: E100-00-00

--- E100-00-00.g02 (geometry) --- (continued)

Type RM Length L Ch R = 3 ,3997.0  ,,,
BEGIN DESCRIPTION:
UNION PACIFIC RAILROAD
Structure ID: E100-00-00-06
END DESCRIPTION:
Bridge Culvert--1,0,-1,-1, 0
Deck Dist Width WeirC Skew NumUp NumDn MinLoCord MaxHiCord MaxSubmerge Is_Ogee
10,14,2.6,0, 156, 156, , , 0.95, 0, ,,,
    3278    3358    3362    3388    3392    3418    3432    3478    3622    3662
    3698    3738    3798    3868    3882  3919.1    3922    3962    4008    4042
    4078    4148    4168    4212    4238    4242    4288    4292    4308    4348
    4352    4362    4378    4392    4462    4478    4522    4548    4578    4598
    4612  4615.6    4628  4633.5  4637.5    4645 4651.31  4651.4  4657.5    4658
  4658.4  4673.4    4686  4700.9  4709.8    4730  4761.1  4762.6  4775.5  4813.7
  4816.4  4846.9  4873.3  4877.6  4912.4  4925.8  4930.8  4942.8  4962.1  4969.3
  4971.8  4983.6  4989.5    5028  5030.7  5030.9  5037.1  5039.1  5049.6  5062.4
  5084.3  5088.1  5098.5    5113  5117.9  5142.2  5157.9  5167.9  5177.9  5187.9
  5277.9  5336.4  5366.4  5386.4  5403.6  5406.4  5476.4  5556.4  5576.4  5596.4
  5606.4  5626.4  5666.4  5676.4  5686.4  5696.4 5706.89    5707    5714  5716.4
  5720.1  5720.9  5726.4  5730.9  5746.4  5766.4  5770.9  5786.4  5796.4  5810.9
  5830.9  5890.9  5906.4  5910.9  5966.4  6036.4  6060.9  6076.4  6080.9  6110.9
  6160.9  6176.4  6196.4  6210.9  6219.1  6226.4  6229.9  6249.1  6259.1  6279.1
  6309.1  6309.9  6329.1  6339.9  6349.9  6379.9  6429.9  6509.1  6559.1  6569.9
  6659.1  6679.9  6689.1  6708.8  6719.9  6723.1
    47.4   46.84   46.84   47.16   47.21   47.21   47.21    48.1   48.43   48.61
    48.6    48.8   48.36    48.4   48.45   48.77   48.81   48.74    48.9   48.71
    48.3   47.21   46.93   46.46   46.92   47.01    47.1   47.02    46.7   45.42
   45.61   46.15      47   47.39   49.35    49.8   49.55    49.4   48.65   48.45
   49.01   49.49    50.4   50.28    50.2    50.2    50.2    50.2    50.2   51.26
   52.11   52.24   52.35   52.48   52.56   52.67   52.83   52.84    52.9   53.06
   53.07   53.17   53.26   53.27   53.39   53.44   53.46   53.49   53.55   53.58
   53.58   53.62   53.63   53.69   53.69   53.69    53.7    53.7    53.7    53.7
   53.69   53.69   53.68   53.67   53.66   53.64   53.62   53.61    53.6   53.59
   53.49   53.42   53.39   53.37   53.35   53.34   53.27   53.18   53.15   53.13
   53.12    53.1   53.05   53.04   53.03   53.02   53.01   53.01      53   51.78
    49.9    49.9   50.23    50.5   50.35   50.14    50.1    50.1    50.1    50.1
    49.5    49.3   48.84    48.7   48.03   47.19    46.9   45.89    45.6    45.1
    45.1   45.41   45.81    46.1    45.9   45.83   45.79    45.6    44.9    44.6
    44.2   44.21   44.91   45.31   45.11   43.95   44.81    44.6    44.1    44.1
   44.15   44.21   44.03    43.7    43.4    43.5
                                                                                
                                                                                
                                                                                
                                                                                
                                                                           44.26
   45.11   45.24   45.35   45.48   45.56   45.67   45.83   45.84    45.9   46.06
   46.07   46.17   46.26   46.27   46.39   46.44   46.46   46.49   46.55   46.58
   46.58   46.62   46.63   46.69   46.69   46.69    46.7    46.7    46.7    46.7
   46.69   46.69   46.68   46.67   46.66   46.64   46.62   46.61    46.6   46.59
   46.49   46.42   46.39   46.37   46.35   46.34   46.27   46.18   46.15   46.13
   46.12    46.1   46.05   46.04   46.03   46.02   46.01
                                                                                
                                                                                
                                                                                
                                                                                
                                                
    3278    3358    3362    3388    3392    3418    3432    3478    3622    3662
    3698    3738    3798    3868    3882  3919.1    3922    3962    4008    4042
    4078    4148    4168    4212    4238    4242    4288    4292    4308    4348
    4352    4362    4378    4392    4462    4478    4522    4548    4578    4598
    4612  4615.6    4628  4633.5  4637.5    4645 4651.31  4651.4  4657.5    4658
  4658.4  4673.4    4686  4700.9  4709.8    4730  4761.1  4762.6  4775.5  4813.7
  4816.4  4846.9  4873.3  4877.6  4912.4  4925.8  4930.8  4942.8  4962.1  4969.3
  4971.8  4983.6  4989.5    5028  5030.7  5030.9  5037.1  5039.1  5049.6  5062.4
  5084.3  5088.1  5098.5    5113  5117.9  5142.2  5157.9  5167.9  5177.9  5187.9
  5277.9  5336.4  5366.4  5386.4  5403.6  5406.4  5476.4  5556.4  5576.4  5596.4
  5606.4  5626.4  5666.4  5676.4  5686.4  5696.4 5706.89    5707    5714  5716.4
  5720.1  5720.9  5726.4  5730.9  5746.4  5766.4  5770.9  5786.4  5796.4  5810.9
  5830.9  5890.9  5906.4  5910.9  5966.4  6036.4  6060.9  6076.4  6080.9  6110.9
  6160.9  6176.4  6196.4  6210.9  6219.1  6226.4  6229.9  6249.1  6259.1  6279.1
  6309.1  6309.9  6329.1  6339.9  6349.9  6379.9  6429.9  6509.1  6559.1  6569.9
  6659.1  6679.9  6689.1  6708.8  6719.9  6723.1
    47.4   46.84   46.84   47.16   47.21   47.21   47.21    48.1   48.43   48.61
    48.6    48.8   48.36    48.4   48.45   48.77   48.81   48.74    48.9   48.71
    48.3   47.21   46.93   46.46   46.92   47.01    47.1   47.02    46.7   45.42
   45.61   46.15      47   47.39   49.35    49.8   49.55    49.4   48.65   48.45
   49.01   49.49    50.4   50.28    50.2    50.2    50.2    50.2    50.2   51.26
   52.11   52.24   52.35   52.48   52.56   52.67   52.83   52.84    52.9   53.06
   53.07   53.17   53.26   53.27   53.39   53.44   53.46   53.49   53.55   53.58
   53.58   53.62   53.63   53.69   53.69   53.69    53.7    53.7    53.7    53.7
   53.69   53.69   53.68   53.67   53.66   53.64   53.62   53.61    53.6   53.59
   53.49   53.42   53.39   53.37   53.35   53.34   53.27   53.18   53.15   53.13
   53.12    53.1   53.05   53.04   53.03   53.02   53.01   53.01      53   51.78
    49.9    49.9   50.23    50.5   50.35   50.14    50.1    50.1    50.1    50.1
    49.5    49.3   48.84    48.7   48.03   47.19    46.9   45.89    45.6    45.1
    45.1   45.41   45.81    46.1    45.9   45.83   45.79    45.6    44.9    44.6
    44.2   44.21   44.91   45.31   45.11   43.95   44.81    44.6    44.1    44.1
   44.15   44.21   44.03    43.7    43.4    43.5
                                                                                
                                                                                
                                                                                
                                                                                
                                                                           44.26
   45.11   45.24   45.35   45.48   45.56   45.67   45.83   45.84    45.9   46.06
   46.07   46.17   46.26   46.27   46.39   46.44   46.46   46.49   46.55   46.58
   46.58   46.62   46.63   46.69   46.69   46.69    46.7    46.7    46.7    46.7
   46.69   46.69   46.68   46.67   46.66   46.64   46.62   46.61    46.6   46.59
   46.49   46.42   46.39   46.37   46.35   46.34   46.27   46.18   46.15   46.13
   46.12    46.1   46.05   46.04   46.03   46.02   46.01
                                                                                
                                                                                
                                                                                
                                                                                
                                                
Pier Skew, UpSta & Num, DnSta & Num=  ,4686.3, 2 ,4686.3, 2 , 0 , 0 , 0 ,,
     3.5     3.5
   26.49   46.37
     3.5     3.5
   26.26   46.14
Pier Skew, UpSta & Num, DnSta & Num=  ,4746.4, 2 ,4746.4, 2 , 0 , 0 , 0 ,,
     3.5     3.5
    22.7   46.76
     3.5     3.5
   22.47   46.53
Pier Skew, UpSta & Num, DnSta & Num=  ,4801.2, 2 ,4801.2, 2 , 0 , 0 , 0 ,,
       4       4
   15.42   47.02
       4       4
   15.19   46.79
Pier Skew, UpSta & Num, DnSta & Num=  ,4856.2, 2 ,4856.2, 2 , 0 , 0 , 0 ,,
       4       4
   10.23   47.21
       4       4
      10   46.98
Pier Skew, UpSta & Num, DnSta & Num=  ,4911.2, 2 ,4911.2, 2 , 0 , 0 , 0 ,,
       4       4
   10.01   47.39
       4       4
    9.78   47.16
Pier Skew, UpSta & Num, DnSta & Num=  ,4966, 2 ,4966, 2 , 0 , 0 , 0 ,,
       5       5
    -.95   47.58
       5       5
   -1.18   47.35
Pier Skew, UpSta & Num, DnSta & Num=  ,5025.7, 2 ,5025.7, 2 , 0 , 0 , 0 ,,
       5       5
   -2.87   47.69
       5       5
    -3.1   47.46
Pier Skew, UpSta & Num, DnSta & Num=  ,5086.2, 2 ,5086.2, 2 , 0 , 0 , 0 ,,
     3.5     3.5
   16.07   47.69
     3.5     3.5
   15.84   47.46
Pier Skew, UpSta & Num, DnSta & Num=  ,5146.2, 2 ,5146.2, 2 , 0 , 0 , 0 ,,
     3.5     3.5
   22.58   47.64
     3.5     3.5
   22.35   47.41
Pier Skew, UpSta & Num, DnSta & Num=  ,5241.2, 2 ,5241.2, 2 , 0 , 0 , 0 ,,
     3.5     3.5
       0      50
     3.5     3.5
       0      50
Pier Skew, UpSta & Num, DnSta & Num=  ,5291.2, 2 ,5291.2, 2 , 0 , 0 , 0 ,,
     3.5     3.5
       0      50
     3.5     3.5
       0      50
Pier Skew, UpSta & Num, DnSta & Num=  ,5346.2, 2 ,5346.2, 2 , 0 , 0 , 0 ,,
     3.5     3.5
       0      50
     3.5     3.5
       0      50
Pier Skew, UpSta & Num, DnSta & Num=  ,5406.2, 2 ,5406.2, 2 , 0 , 0 , 0 ,,
     3.5     3.5
       0      50
     3.5     3.5
       0      50
Pier Skew, UpSta & Num, DnSta & Num=  ,5451.2, 2 ,5451.2, 2 , 0 , 0 , 0 ,,
     3.5     3.5
       0      50
     3.5     3.5
       0      50
Pier Skew, UpSta & Num, DnSta & Num=  ,5551.2, 2 ,5551.2, 2 , 0 , 0 , 0 ,,
     3.5     3.5
       0      50
     3.5     3.5
       0      50
Pier Skew, UpSta & Num, DnSta & Num=  ,5591.2, 2 ,5591.2, 2 , 0 , 0 , 0 ,,
     3.5     3.5
       0      50
     3.5     3.5
       0      50
Pier Skew, UpSta & Num, DnSta & Num=  ,5651.2, 2 ,5651.2, 2 , 0 , 0 , 0 ,,
     3.5     3.5
       0      50
     3.5     3.5
       0      50
BR Coef= 1 , 1 , 0 ,1.25, 0 ,,,0.8,0,1.2,0,
WSPro=,,,, 1 ,,,, 0 ,,,, 0 ,,,,-1 ,-1 ,-1 , 0 , 0 , 0 , 0 , 0
BC Design=,, 0 ,, 0 ,,,,,,
BC HTab HWMax=49.77
BC Use User HTab Curves=0
BC User HTab FreeFlow(D)= 0

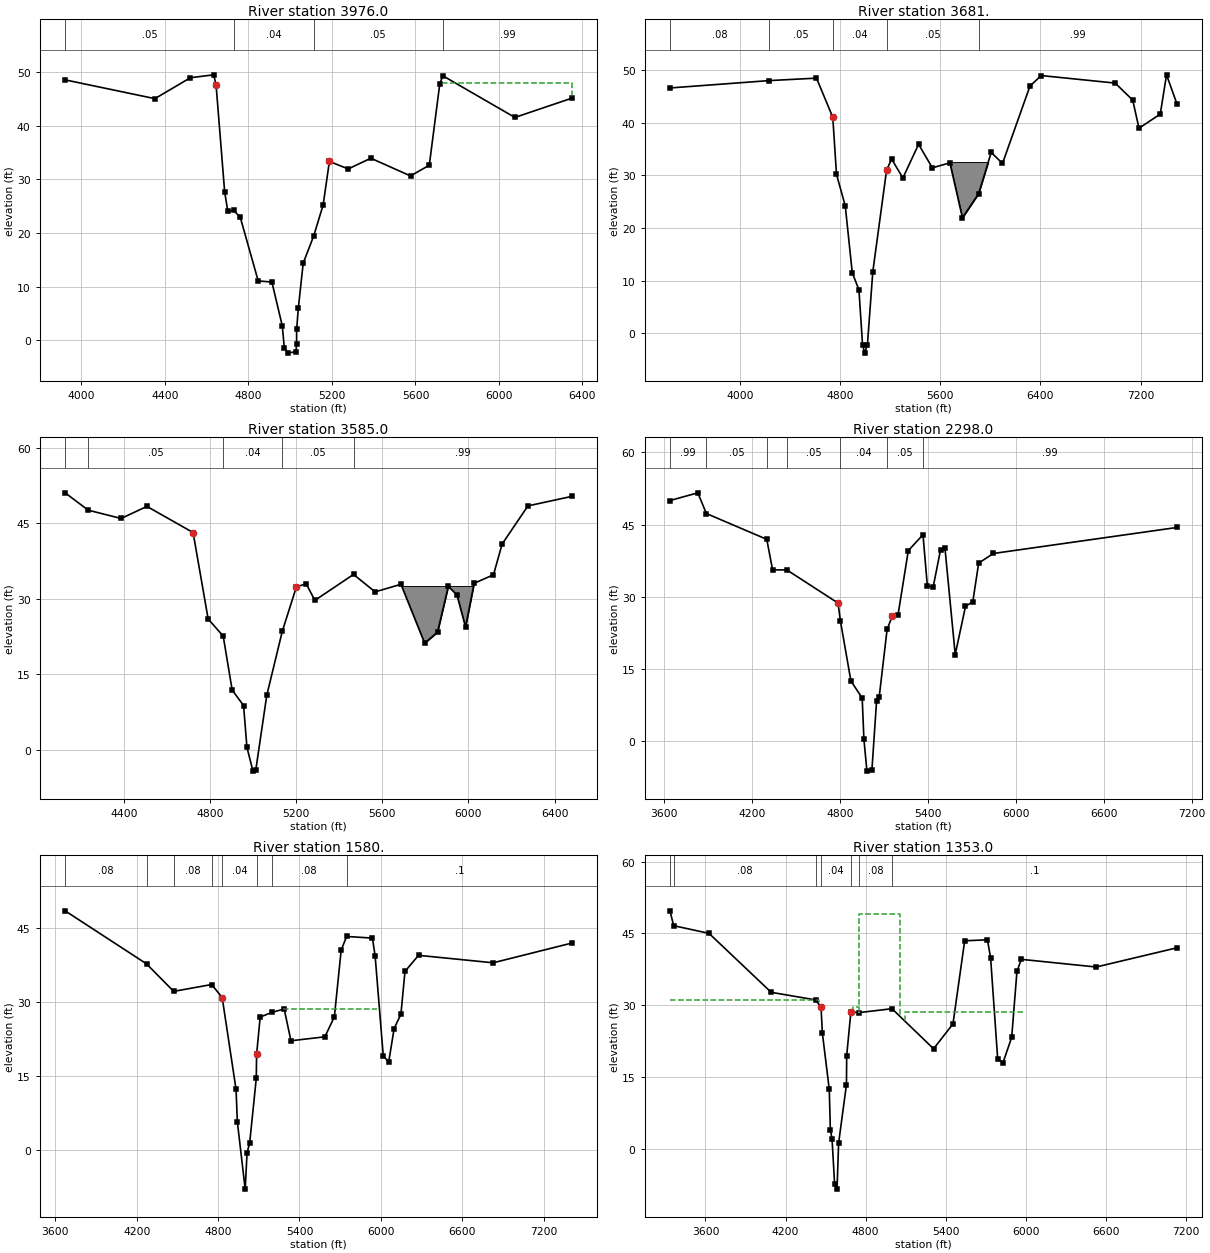
Type RM Length L Ch R = 1 ,3976.0  ,221.6,295,459.4
BEGIN DESCRIPTION:
Downstream Section of Bridge/Culvert/Weir
END DESCRIPTION:
XS GIS Cut Line= 6
 3122352.961274213846780.9633906      3121765.46     13846322.02
      3121491.53     13846298.74      3121082.57     13846288.89
      3120196.96     13846245.94 3120105.0819472 13846182.308669
#Sta/Elev= 30
    3922   48.52    4352   45.02    4522   48.92  4633.5   49.46    4645   47.58
    4686   27.71  4700.9   24.09    4730   24.18  4761.1   22.88  4846.9   11.05
  4912.4   10.85  4962.1    2.69  4971.8   -1.39  4989.5    -2.4    5028   -2.11
  5030.7    -.63  5030.9    2.01  5039.1    6.03  5062.4   14.37    5113   19.47
  5157.9   25.22  5187.9   33.32  5277.9   31.92  5386.4   33.92  5576.4   30.62
  5666.4   32.62  5716.4   47.72  5730.9   49.29  6076.4   41.52  6349.9   45.12
#Mann= 4 ,-1 , 0
    3922     .05       0    4730     .04       0    5113     .05       0
  5730.9     .99       0
#XS Ineff= 2 , 0
       0 4628.82   47.44 5727.35       0   47.98
Permanent Ineff=
       F       F
Bank Sta=4645,5187.9
XS Rating Curve= 0 ,0
Exp/Cntr=0.5,0.3

Type RM Length L Ch R = 1 ,3681.   ,97.4,96,78.1
BEGIN DESCRIPTION:
Union Pacific RR4 - D/S - XS 1
END DESCRIPTION:
XS GIS Cut Line= 4
      3122862.67     13847051.89      3121830.55     13846245.61
      3121326.76     13845826.25      3119489.93     13844845.42
#Sta/Elev= 30
  3441.5   46.65  4231.5   48.05  4611.5   48.52  4741.5   41.08  4771.2   30.22
  4841.2    24.2 4897.14   11.49 4950.39    8.24 4979.18   -2.19 4996.44    -3.8
 5018.25   -2.17  5061.2    11.7  5171.2      31  5211.2   33.13  5301.2   29.52
  5426.7   35.93  5536.7   31.45  5676.7   32.41  5776.7   21.95  5906.7   26.57
  6006.7    34.4  6096.7   32.28  6316.7   47.04  6406.7   49.01  6996.7   47.58
  7136.7   44.34  7186.7   38.99  7356.7   41.68  7406.7   49.15    7489   43.68
#Mann= 5 ,-1 , 0
  3441.5     .08       0  4231.5     .05       0  4741.5     .04       0
  5171.2     .05       0  5906.7     .99       0
#Block Obstruct= 1 ,-1
    5670    6000   32.57
Bank Sta=4741.5,5171.2
XS Rating Curve= 0 ,0
Exp/Cntr=0.3,0.1

Type RM Length L Ch R = 1 ,3585.0  ,1285.5,1287,1324.4
BEGIN DESCRIPTION:
Cross Section E100-00-00-X03
Located At: 2600FT US I-10
Blocked out portions represent supressed I-10.
END DESCRIPTION:
XS GIS Cut Line= 4
 3122384.536045513846570.4714402      3121981.12     13846235.26
      3121520.95     13845872.88      3120468.17     13845208.87
#Sta/Elev= 30
  4126.1    51.1  4233.2   47.65  4386.1      46  4506.1    48.4  4720.6    43.2
  4790.6      26  4860.5    22.6  4902.1   11.88  4955.2    8.78  4970.7     .49
  4998.7   -4.26  5011.9   -4.03    5063   10.84  5135.2   23.58  5200.6    32.4
  5246.3      33  5286.3    29.7    5466   34.87  5566.3    31.4  5686.3    32.9
  5796.3    21.2  5856.3    23.4  5906.3    32.5  5946.3    30.8  5986.3    24.4
  6026.3    33.1  6116.3    34.8  6156.3    40.9  6276.3    48.5    6481    50.4
#Mann= 5 ,-1 , 0
  4126.1     .08       0  4233.2     .05       0  4860.5     .04       0
  5135.2     .05       0    5466     .99       0
#Block Obstruct= 1 ,-1
  5686.9 6072.05   32.57
Bank Sta=4720.6,5200.6
XS Rating Curve= 0 ,0
Exp/Cntr=0.3,0.1

Type RM Length L Ch R = 1 ,2298.0  ,719,718,497.6
BEGIN DESCRIPTION:
Cross Section E100-00-00-X02
Blocked out portions represent supressed I-10.
END DESCRIPTION:
XS GIS Cut Line= 5
      3123430.34     13846147.16      3122761.19     13845253.09
      3122464.36     13844971.11      3121855.29     13844367.98
      3120784.41     13844461.41
#Sta/Elev= 30
  3640.4      50  3830.4    51.6  3888.5    47.3  4300.8   41.94  4340.4    35.6
  4438.1   35.58  4787.1    28.7    4803   25.04  4874.8   12.53  4951.9    8.96
  4963.6     .37  4984.3   -6.21  5018.4    -5.9  5049.8    8.26  5068.1    9.26
  5121.8   23.23  5157.1      26  5196.6    26.3  5266.6    39.6  5366.6    42.9
  5396.6    32.2  5436.6    32.1  5486.6    39.8  5516.6    40.1  5586.6      18
  5656.6      28  5706.6      29  5746.6      37  5846.6      39  7098.7    44.4
#Mann= 7 ,-1 , 0
  3640.4     .99       0  3888.5     .05       0  4300.8      .1       0
  4438.1     .05       0    4803     .04       0  5121.8     .05       0
  5366.6     .99       0
#XS Ineff= 2 , 0
                         5300.88              30
Permanent Ineff=
       F       F
Bank Sta=4787.1,5157.1
XS Rating Curve= 0 ,0
Exp/Cntr=0.3,0.1

Type RM Length L Ch R = 1 ,1580.   ,97.9,227,228
BEGIN DESCRIPTION:
Union Pacific RR3 - U/S - XS 4
END DESCRIPTION:
XS GIS Cut Line= 6
       3123583.6     13845854.39      3123248.44     13844798.87
      3123012.13     13844455.45      3122313.39     13844667.96
      3121823.53     13844285.67       3121008.3      13844012.8
#Sta/Elev= 30
    3673   48.52    4273   37.78    4473   32.21    4753    33.6  4830.5   30.96
 4932.71   12.35  4942.2    5.81    5000   -7.83 5013.88    -.47 5033.28    1.59
 5081.73   14.59 5084.07   19.43  5110.5   27.01  5197.3   27.96  5287.3   28.65
  5337.3   22.21  5587.3   23.01  5657.3   27.05  5707.3   40.53  5747.3   43.33
  5937.7      43  5957.7   39.41  6017.7   19.16  6057.7   17.91  6097.7   24.69
  6147.7   27.58  6177.7   36.25  6277.7   39.51  6827.9      38  7408.6      42
#Mann= 8 ,-1 , 0
    3673     .08       0    4273     .05       0    4473     .08       0
    4753     .05       0  4830.5     .04       0 5084.07     .05       0
  5197.3     .08       0  5747.3      .1       0
#XS Ineff= 2 ,-1
    5970    6549      30 5277.84 5968.19   28.64
Permanent Ineff=
       F       F
Bank Sta=4830.5,5084.07
XS Rating Curve= 0 ,0
Exp/Cntr=0.5,0.3

Type RM Length L Ch R = 1 ,1353.0  ,33,34,209
BEGIN DESCRIPTION:
Upstream Section of Bridge/Culvert/Weir NOTES
N-value on the right overbank was raised to account for the piers under I-10
Blocked out portions represent buildings.
The n-value in the low areas in the ROB is set to balance the flow in the ROB between cross sections.
END DESCRIPTION:
XS GIS Cut Line= 6
 3123688.5365167  13845861.08027      3123315.35     13844702.49
       3123412.4     13844427.24      3122381.14     13844618.78
      3121925.41     13844282.84      3121045.85      13843992.5
#Sta/Elev= 30
3334.258   49.723361.666   46.623626.594   45.024092.501   32.724425.762   31.13
4465.684   29.624476.101   24.14 4527.44    12.54535.662    4.09 4548.36    2.11
4567.542   -7.294585.724   -8.344597.689    1.294656.158   13.454658.168   19.53
 4689.32   28.634751.714   28.494997.276    29.35308.978   20.94 5454.23   26.13
5541.932   43.475712.399   43.675736.152   39.935789.137   18.84 5828.42   17.99
5894.195   23.335933.478   37.095966.365    39.66526.883      387131.283      42
#Mann= 7 ,-1 , 0
3334.258     .99       03361.666     .08       04425.762     .05       0
4465.684     .04       0 4689.32    .055       04751.714     .08       0
4997.276      .1       0
#XS Ineff= 4 ,-1
 4751.86 5059.92   49.013334.2584448.109    31.2  4707.9 4751.86    29.6
 5093.32  5987.8   28.52
Permanent Ineff=
       F       F       F       F
Bank Sta=4465.684,4689.32
XS Rating Curve= 0 ,0
Skew Angle= 24
Exp/Cntr=0.5,0.3

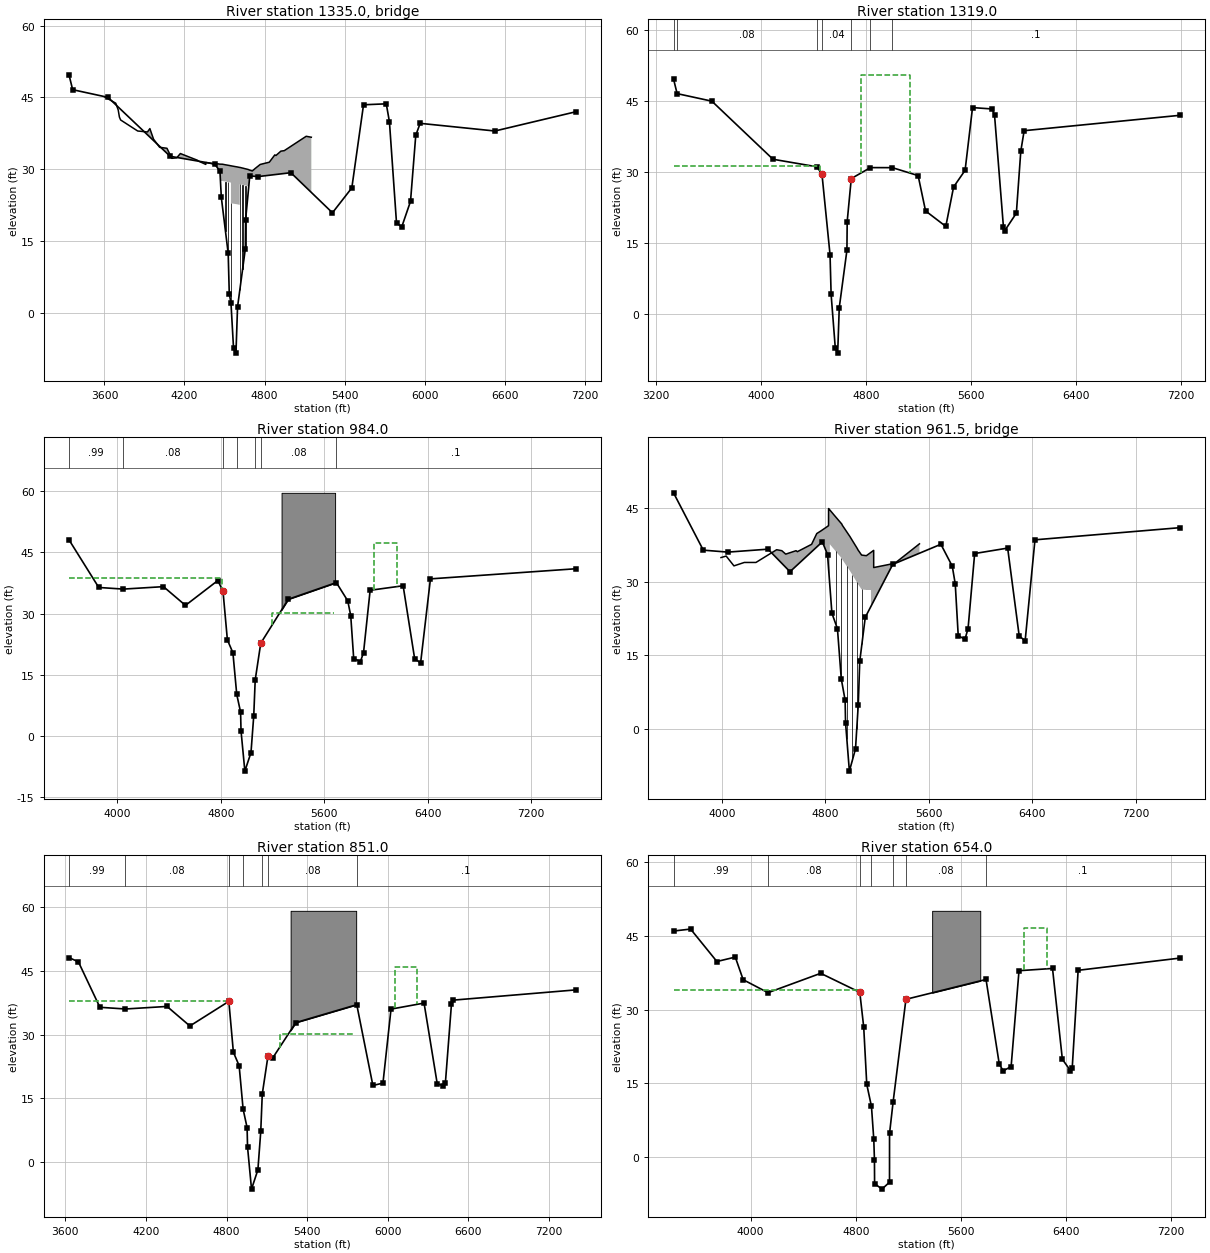
Type RM Length L Ch R = 3 ,1335.0  ,,,
BEGIN DESCRIPTION:
UNION PACIFIC RR
Structure ID: E100-00-00-05
Bridge skew angle is 24 degrees.
END DESCRIPTION:
Bridge Culvert--1,0,-1,-1, 0
Deck Dist Width WeirC Skew NumUp NumDn MinLoCord MaxHiCord MaxSubmerge Is_Ogee
10,16,2.6,24, 73, 73, , , 0.95, 0, ,,,
3602.5663684.7853703.0563712.1923721.3273849.2243922.3073940.5783967.9854013.662
4068.4754105.0174141.5584168.9644296.8614306.362 4359.534360.9934392.7834415.998
4416.0794425.7624430.6954432.7054448.6924465.6844470.4354474.081 4474.184474.281
  4476.14486.056 4486.33 4507.25 4527.444535.662 4548.27 4548.364567.5434585.724
4594.768 4597.694614.3184614.4094617.3334636.1524639.8064656.1584658.1684675.069
4675.618 4676.534687.3014687.4014687.502 4689.324708.4134729.1514753.8164767.246
4797.3014818.8534818.9524825.073 4835.674848.0944876.778 4878.794885.9154922.457
4947.762  5112.25150.662
    45.1    43.8    42.4    40.9    40.3      38    37.8    38.5    36.3    34.6
    34.4    32.3    32.4    33.3    31.9   31.71   31.03   31.42   31.27   31.17
   31.16   31.12   31.12   31.13   31.16   31.09   31.08   31.08   31.08   31.08
   31.08   31.07   31.06   30.95   30.85   30.81   30.74   30.74   30.64   30.55
   30.51   30.49    30.4    30.4   30.39   30.26   30.24   30.12   30.11   29.99
   29.99   29.99   29.85   29.85   29.85   29.83   29.66   30.17   30.72   31.02
   31.23   31.37   31.38   31.42   31.49   31.95   33.01   32.99    32.9    33.8
    33.9    36.9    36.7
                                                                                
                                                                                
                                                   27.58   27.58   27.58   27.58
   27.58   27.57   27.56   27.45   27.35   27.31   27.24   22.94   22.84   22.75
   22.71   22.69    22.6    26.9   26.89   26.76   26.74   26.62   26.61   26.49
   26.49   26.49
                                                                                
                        
3602.5663684.7853703.0563712.1923721.3273849.2243922.3073940.5783967.9854013.662
4068.4754105.0174141.5584168.9644296.8614306.362 4359.534360.9934392.7834415.998
4416.0794425.7624430.6954432.7054448.6924465.6844470.4354474.081 4474.184474.281
  4476.14486.056 4486.33 4507.25 4527.444535.662 4548.27 4548.364567.5434585.724
4594.768 4597.694614.3184614.4094617.3334636.1524639.8064656.1584658.1684675.069
4675.618 4676.534687.3014687.4014687.502 4689.324708.4134729.1514753.8164767.246
4797.3014818.8534818.9524825.073 4835.674848.0944876.778 4878.794885.9154922.457
4947.762  5112.25150.662
    45.1    43.8    42.4    40.9    40.3      38    37.8    38.5    36.3    34.6
    34.4    32.3    32.4    33.3    31.9   31.71   31.03   31.42   31.27   31.17
   31.16   31.12   31.12   31.13   31.16   31.09   31.08   31.08   31.08   31.08
   31.08   31.07   31.06   30.95   30.85   30.81   30.74   30.74   30.64   30.55
   30.51   30.49    30.4    30.4   30.39   30.26   30.24   30.12   30.11   29.99
   29.99   29.99   29.85   29.85   29.85   29.83   29.66   30.17   30.72   31.02
   31.23   31.37   31.38   31.42   31.49   31.95   33.01   32.99    32.9    33.8
    33.9    36.9    36.7
                                                                                
                                                                                
                                                   27.58   27.58   27.58   27.58
   27.58   27.57   27.56   27.45   27.35   27.31   27.24   22.94   22.84   22.75
   22.71   22.69    22.6    26.9   26.89   26.76   26.74   26.62   26.61   26.49
   26.49   26.49
                                                                                
                        
Pier Skew, UpSta & Num, DnSta & Num=  ,4507.25, 2 ,4507.25, 2 , 0 , 0 , 0 ,,
       4       4
   14.53   29.75
       4       4
   14.53   29.75
Pier Skew, UpSta & Num, DnSta & Num=  ,4527.44, 2 ,4527.44, 2 , 0 , 0 , 0 ,,
       4       4
    9.61   29.75
       4       4
    9.61   29.75
Pier Skew, UpSta & Num, DnSta & Num=  ,4548.36, 2 ,4548.36, 2 , 0 , 0 , 0 ,,
       4       4
     .19   29.75
       4       4
     .19   29.75
Pier Skew, UpSta & Num, DnSta & Num=  ,4614.409, 2 ,4614.409, 2 , 0 , 0 , 0 ,,
       4       4
    1.35   29.75
       4       4
    1.35   29.75
Pier Skew, UpSta & Num, DnSta & Num=  ,4636.152, 2 ,4636.152, 2 , 0 , 0 , 0 ,,
       4       4
    7.18   29.75
       4       4
    7.18   29.75
Pier Skew, UpSta & Num, DnSta & Num=  ,4656.158, 2 ,4656.158, 2 , 0 , 0 , 0 ,,
       4       4
      12   29.75
       4       4
      12   29.75
Abutment Skew #Up #Dn= , 2 , 2
4415.8964432.705
    31.1   31.12
4415.8964432.705
    31.1   31.12
Abutment Skew #Up #Dn= , 2 , 2
4639.8064819.034
    9.56   31.36
4639.8064819.034
    9.56   31.36
BR Coef= 1 , 1 , 0 ,1.25, 0 ,,,0.8,0,1.2,0,
WSPro=,,,, 1 ,,,, 0 ,,,, 0 ,,,,-1 ,-1 ,-1 , 0 , 0 , 0 , 0 , 0
BR U #Sta/Elev= 30
3334.258   49.723361.666   46.623626.594   45.024092.501   32.724425.762   31.13
4465.684   29.624476.101   24.14 4527.44    12.54535.662    4.09 4548.36    2.11
4567.542   -7.294585.724   -8.344597.689    1.294656.158   13.454658.168   19.53
 4689.32   28.634751.714   28.494997.276    29.35308.978   20.94 5454.23   26.13
5541.932   43.475712.399   43.675736.152   39.935789.137   18.84 5828.42   17.99
5894.195   23.335933.478   37.095966.365    39.66526.883      387131.283      42
BR U #Mann= 7
3334.258     .993361.666     .084425.762     .054465.684     .04 4689.32    .055
4751.714     .084997.276      .1
BR D #Sta/Elev= 30
3334.258   49.693361.666   46.593626.594   44.994092.501   32.694425.762    31.1
4465.684   29.59 4527.44   12.474535.662    4.064567.542   -7.324585.724   -8.37
4597.689    1.264656.158   13.424658.168    19.5 4689.32    28.64835.487   30.92
5002.666   30.915198.896   29.235255.536   21.755409.925   18.475469.305   26.82
5557.004   30.355613.645   43.635763.284   43.345781.555      425849.158   18.39
 5860.12    17.6 5947.82   21.285981.623    34.46007.202   38.747195.971      42
BR D #Mann= 7
3334.258     .993361.666     .084425.762     .054465.684     .04 4689.32    .055
4835.487     .085002.666      .1
BC Design=,, 0 ,, 0 ,,,,,,
BC HTab HWMax=49.72
BC Use User HTab Curves=0
BC User HTab FreeFlow(D)= 0

Type RM Length L Ch R = 1 ,1319.0  ,334,335,499.8
BEGIN DESCRIPTION:
Downstream Section of Bridge/Culvert/Weir  NOTES
N-value on the right overbank was raised to account for the piers under I-10
Blocked out portions represent buildings.
The n-value in the low areas in the ROB is set to balance the flow in the ROB between cross sections.
END DESCRIPTION:
XS GIS Cut Line= 6
 3123726.496540513845854.3902624      3123336.44     13844629.81
      3123446.24     13844363.57      3122396.76      13844569.3
      3121972.28     13844269.82      3121064.52      13843963.3
#Sta/Elev= 30
3334.258   49.693361.666   46.593626.594   44.994092.501   32.694425.762    31.1
4465.684   29.59 4527.44   12.474535.662    4.064567.542   -7.324585.724   -8.37
4597.689    1.264656.158   13.424658.168    19.5 4689.32    28.64835.487   30.92
5002.666   30.915198.896   29.235255.536   21.755409.925   18.475469.305   26.82
5557.004   30.355613.645   43.635763.284   43.345781.555      425849.158   18.39
 5860.12    17.6 5947.82   21.285981.623    34.46007.202   38.747195.971      42
#Mann= 7 ,-1 , 0
3334.258     .99       03361.666     .08       04425.762     .05       0
4465.684     .04       0 4689.32    .055       04835.487     .08       0
5002.666      .1       0
#XS Ineff= 3 ,-1
  4766.7 5134.15   50.573334.2584448.109    31.2 5156.42 6054.61    28.6
Permanent Ineff=
       F       F       F
Bank Sta=4465.684,4689.32
XS Rating Curve= 0 ,0
Skew Angle= 24
Exp/Cntr=0.5,0.3

Type RM Length L Ch R = 1 ,984.0   ,134,133,83.2
BEGIN DESCRIPTION:
Upstream Section of Bridge/Culvert/Weir  NOTES
N-value was adjusted from 0.02 to 0.038 in the internal bridge data to take into account the pipe that is under the Main St. Access rd.
Blocked out portions represent buildings.
The n-value in the low areas in the ROB is set to balance the flow in the ROB between cross sections.
END DESCRIPTION:
XS GIS Cut Line= 6
      3124454.88     13845465.24      3123610.46     13844437.19
      3123565.23     13844212.17      3123477.62     13844153.99
      3122094.68     13844170.86      3121304.06      13843957.7
#Sta/Elev= 30
  3627.3   48.11  3857.3   36.41  4047.3   36.014357.299   36.61  4527.3   32.01
  4777.3   38.114817.299   35.51  4851.2   23.54    4894   20.37  4923.6   10.13
  4953.3    5.79  4956.6     1.2  4986.2   -8.69  5033.6   -4.14  5054.9    4.88
  5066.2   13.69    5109   22.71  5321.7   33.51  5693.3   37.61  5781.3   33.13
  5804.3   29.52  5827.3   18.96  5879.3   18.22  5903.3   20.41  5954.3   35.72
  6209.3   36.83  6298.3   18.93  6344.3   17.87  6420.3   38.52  7541.7      41
#Mann= 7 ,-1 , 0
  3627.3     .99       0  4047.3     .08       04817.299    .045       0
  4923.6    .015       0  5066.2    .045       0    5109     .08       0
  5693.3      .1       0
#XS Ineff= 5 ,-1
  3627.3 4807.86   38.85 5195.03 5678.69   30.14 5771.47 5986.74   29.75
 5986.74 6161.19   47.33 6161.19 6446.98   29.75
Permanent Ineff=
       F       F       F       F       F
#Block Obstruct= 1 ,-1
 5269.86 5683.62   59.65
Bank Sta=4817.299,5109
XS Rating Curve= 0 ,0
Exp/Cntr=0.5,0.3

Type RM Length L Ch R = 3 ,961.5   ,,,
BEGIN DESCRIPTION:
MAIN STREET ACCESS RD
Structure ID: E100-00-00-03
N-value was adjusted from 0.02 to 0.038 in the internal bridge data to take into account the pipe that is under the Main St. Access rd.
Bridge is skewed 23.9 degrees.
END DESCRIPTION:
Bridge Culvert--1,0,-1,-1, 0
Deck Dist Width WeirC Skew NumUp NumDn MinLoCord MaxHiCord MaxSubmerge Is_Ogee
81,25,2.6,0, 61, 61, , , 0.95, 0, ,,,
  3994.2  4034.24094.199  4174.24264.2014424.2014464.201  4494.2  4574.2  4584.2
  4694.2  4734.24735.911    4736    47644764.2014784.201  4804.24824.101 4825.19
4825.299 4825.414825.601    4835  4835.14843.401    48674889.201  4896.64918.101
  4926.3  4928.6  4929.64930.6014940.299  4959.2  4981.9  4990.25006.601  5016.3
  5027.85027.899  5033.45039.2015049.7995050.2995053.1015079.701    5081    5082
5117.301  5152.9    5153 5173.39  5173.55173.891    5174 5174.115294.701  5345.4
  5527.8
    34.9    35.2    33.2    33.9    33.9    36.5    36.3    35.6    36.3    36.1
    37.6    39.8   39.83   39.83    40.3    40.3   40.66   41.02   41.38    41.4
    44.9    44.9    44.9   44.62   44.62   44.35   43.61   42.92   42.69   42.03
   41.77    41.7   41.62   41.53   41.15   40.41   39.52    39.2   38.49   38.07
   37.58   37.57   37.34   37.09   36.63   36.56   36.45   35.44    35.4    35.4
   35.28   35.96   35.96   36.35   36.35   36.36   36.36   32.86    33.5    33.9
    37.7
                                                                                
                                                                                
                                   37.62   37.35   36.61   35.92   35.69   35.03
   34.77    34.7   34.62   34.53   34.15   33.41   32.52    32.2   31.49   31.07
   30.58   30.57   30.34   30.09   29.63   29.56   29.45   28.44    28.4    28.4
   28.28   28.28
        
  3994.2  4034.24094.199  4174.24264.2014424.2014464.201  4494.2  4574.2  4584.2
  4694.2  4734.24735.911    4736    47644764.2014784.201  4804.24824.101 4825.19
4825.299 4825.414825.601    4835  4835.14843.401    48674889.201  4896.64918.101
  4926.3  4928.6  4929.64930.6014940.299  4959.2  4981.9  4990.25006.601  5016.3
  5027.85027.899  5033.45039.2015049.7995050.2995053.1015079.701    5081    5082
5117.301  5152.9    5153 5173.39  5173.55173.891    5174 5174.115294.701  5345.4
  5527.8
    34.9    35.2    33.2    33.9    33.9    36.5    36.3    35.6    36.3    36.1
    37.6    39.8   39.83   39.83    40.3    40.3   40.66   41.02   41.38    41.4
    44.9    44.9    44.9   44.62   44.62   44.35   43.61   42.92   42.69   42.03
   41.77    41.7   41.62   41.53   41.15   40.41   39.52    39.2   38.49   38.07
   37.58   37.57   37.34   37.09   36.63   36.56   36.45   35.44    35.4    35.4
   35.28   35.96   35.96   36.35   36.35   36.36   36.36   32.86    33.5    33.9
    37.7
                                                                                
                                                                                
                                   37.62   37.35   36.61   35.92   35.69   35.03
   34.77    34.7   34.62   34.53   34.15   33.41   32.52    32.2   31.49   31.07
   30.58   30.57   30.34   30.09   29.63   29.56   29.45   28.44    28.4    28.4
   28.28   28.28
        
Pier Skew, UpSta & Num, DnSta & Num=  ,4881.7, 2 ,4881.7, 2 , 0 , 0 , 0 ,,
     2.5     2.5
       0   41.22
     2.5     2.5
       0   43.47
Pier Skew, UpSta & Num, DnSta & Num=  ,4921.9, 2 ,4921.9, 2 , 0 , 0 , 0 ,,
     2.5     2.5
       0   38.08
     2.5     2.5
       0   40.33
Pier Skew, UpSta & Num, DnSta & Num=  ,4966.3, 2 ,4966.3, 2 , 0 , 0 , 0 ,,
     2.5     2.5
       0   36.62
     2.5     2.5
       0   38.87
Pier Skew, UpSta & Num, DnSta & Num=  ,5008, 2 ,5008, 2 , 0 , 0 , 0 ,,
       3       3
   10.35   35.35
       3       3
    12.6    37.6
Pier Skew, UpSta & Num, DnSta & Num=  ,5043.4, 2 ,5043.4, 2 , 0 , 0 , 0 ,,
     2.5     2.5
    3.74   34.33
     2.5     2.5
    5.99   36.58
Pier Skew, UpSta & Num, DnSta & Num=  ,5083.1, 2 ,5083.1, 2 , 0 , 0 , 0 ,,
     2.5     2.5
    -2.4   30.78
     2.5     2.5
    -.15   33.03
BR Coef= 1 , 1 , 0 ,1.25, 0 ,,,0.8,0,2,0,
WSPro=,,,, 1 ,,,, 0 ,,,, 0 ,,,,-1 ,-1 ,-1 , 0 , 0 , 0 , 0 , 0
BR U #Sta/Elev= 30
  3627.3   48.11  3857.3   36.41  4047.3   36.014357.299   36.61  4527.3   32.01
  4777.3   38.114817.299   35.51  4851.2   23.54    4894   20.37  4923.6   10.13
  4953.3    5.79  4956.6     1.2  4986.2   -8.69  5033.6   -4.14  5054.9    4.88
  5066.2   13.69    5109   22.71  5321.7   33.51  5693.3   37.61  5781.3   33.13
  5804.3   29.52  5827.3   18.96  5879.3   18.22  5903.3   20.41  5954.3   35.72
  6209.3   36.83  6298.3   18.93  6344.3   17.87  6420.3   38.52  7541.7      41
BR U #Mann= 7
  3627.3     .99  4047.3     .084817.299    .045  4923.6    .015  5066.2    .045
    5109     .08  5693.3      .1
BR U Banks=4817.299,
BR D #Sta/Elev= 30
  3627.3   48.11  3697.3   47.11  3857.3   36.41  4047.3   36.014357.299   36.61
  4527.3   32.014817.299    37.8  4851.2   25.83    4894   22.66  4923.6   12.42
  4953.3    8.08  4956.6    3.49  4986.2    -6.4  5033.6   -1.85  5054.9    7.17
  5066.2   15.98    5109      255144.299    24.5  5315.7    32.8  5769.7   37.02
  5889.7      18  5964.7   18.56  6024.7   35.98  6270.7    37.4  6368.7   18.42
  6414.7   17.91  6429.7   18.69  6474.7   37.16  6489.7    38.1  7398.6    40.5
BR D #Mann= 7
  3627.3     .99  4047.3     .084817.299    .045  4923.6    .015  5066.2    .045
    5109     .08  5769.7      .1
BR D Banks=4817.299,
BC Design=,, 0 ,, 0 ,,,,,,
BC HTab HWMax=48.11
BC Use User HTab Curves=0
BC User HTab FreeFlow(D)= 0

Type RM Length L Ch R = 1 ,851.0   ,281.2,197,30.4
BEGIN DESCRIPTION:
Downstream Section of Bridge/Culvert/Weir  NOTES
N-value was adjusted from 0.02 to 0.038 in the internal bridge data to take into account the pipe that is under the Main St. Access rd.
Blocked out portions represent buildings.
The n-value in the low areas in the ROB is set to balance the flow in the ROB between cross sections.
END DESCRIPTION:
XS GIS Cut Line= 6
      3124543.48     13845373.69      3123703.82     13844351.43
      3123657.62     13844121.56      3123568.16       13844118.
      3122099.89      13844134.4      3121489.87      13843975.2
#Sta/Elev= 30
  3627.3   48.11  3697.3   47.11  3857.3   36.41  4047.3   36.014357.299   36.61
  4527.3   32.014817.299    37.8  4851.2   25.83    4894   22.66  4923.6   12.42
  4953.3    8.08  4956.6    3.49  4986.2    -6.4  5033.6   -1.85  5054.9    7.17
  5066.2   15.98    5109      255144.299    24.5  5315.7    32.8  5769.7   37.02
  5889.7      18  5964.7   18.56  6024.7   35.98  6270.7    37.4  6368.7   18.42
  6414.7   17.91  6429.7   18.69  6474.7   37.16  6489.7    38.1  7398.6    40.5
#Mann= 7 ,-1 , 0
  3627.3     .99       0  4047.3     .08       04817.299    .045       0
  4923.6    .015       0  5066.2    .045       0    5109     .08       0
  5769.7      .1       0
#XS Ineff= 5 ,-1
  3627.3    4811   37.78 5194.62  5749.2   30.14 5797.46 6057.26   29.47
 6057.26 6220.57   45.88 6220.57 6539.77   29.47
Permanent Ineff=
       F       F       F       F       F
#Block Obstruct= 1 ,-1
 5277.29 5765.28   59.12
Bank Sta=4817.299,5109
XS Rating Curve= 0 ,0
Exp/Cntr=0.5,0.3

Type RM Length L Ch R = 1 ,654.0   ,390.5,254,113.3
BEGIN DESCRIPTION:
Cross Section E100-00-00-X01  NOTES
Located At: DS I-10 FWY
Blocked out portions represent buildings.
The n-value in the low areas in the ROB is set to balance the flow in the ROB between cross sections.
END DESCRIPTION:
XS GIS Cut Line= 6
      3124685.14     13845498.22      3123980.34     13844280.64
      3123758.65     13844109.69      3123572.48     13844098.95
       3122107.7     13844092.74      3121606.19      13843966.5
#Sta/Elev= 30
  3413.4      46  3543.4    46.4  3743.4    39.8  3883.4    40.7  3943.4    36.1
  4132.5   33.46  4533.4    37.4  4830.9   33.54  4860.8   26.48  4884.1    14.8
  4919.8   10.33  4937.5    3.62  4942.5    -.53  4943.6   -5.37  4999.5    -6.5
  5057.2   -5.09  5057.4    4.82  5084.5   11.22  5182.2   32.11  5791.7   36.15
  5892.7    18.9  5922.7   17.56  5982.7   18.44  6042.7   37.93  6297.7   38.39
  6372.7   19.91  6433.7   17.62  6447.7   18.14  6492.7   38.01  7268.6    40.5
#Mann= 7 ,-1 , 0
  3413.4     .99       0  4132.5     .08       0  4830.9     .04       0
  4919.8    .015       0  5084.5     .04       0  5182.2     .08       0
  5791.7      .1       0
#XS Ineff= 4 ,-1
  3413.4 4817.18   34.01 5791.09 6079.53   28.02 6079.53 6257.69    46.6
 6257.69 6592.79   28.02
Permanent Ineff=
       F       F       F       F
#Block Obstruct= 1 ,-1
 5381.66  5747.7   50.11
Bank Sta=4830.9,5182.2
XS Rating Curve= 0 ,0
Exp/Cntr=0.5,0.3

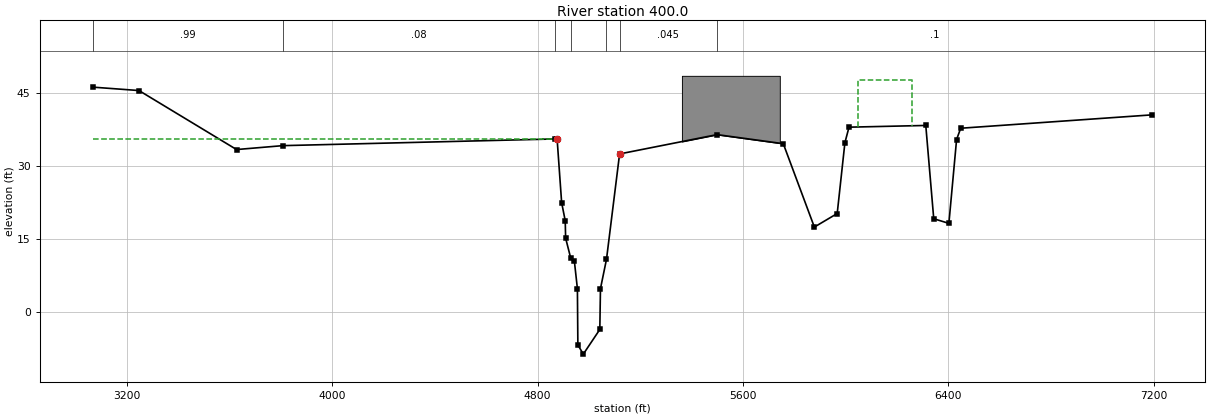
Type RM Length L Ch R = 1 ,400.0   ,36.3,35,33.9
BEGIN DESCRIPTION:
Upstream Section of Bridge/Culvert/Weir  NOTES
Blocked out portions represent buildings.
The n-value in the low areas in the ROB is set to balance the flow in the ROB between cross sections.
END DESCRIPTION:
XS GIS Cut Line= 6
 3124662.668372113845393.2403405      3123930.49      13843805.2
      3123739.42     13844000.52      3123576.89     13843997.68
       3122107.7      13844006.8      3121647.85      13843893.6
#Sta/Elev= 30
  3067.8   46.18  3247.8   45.48  3627.8   33.38  3807.8   34.18  4866.4   35.55
  4876.4   35.52    4894   22.49    4908   18.77  4909.5   15.22  4929.6   11.06
  4943.6   10.48  4955.4    4.84  4957.2   -6.69  4978.4   -8.58  5042.7   -3.52
  5045.2    4.85  5068.7   10.87  5119.7   32.48  5499.3   36.44  5757.3   34.58
  5878.3   17.48  5967.3   20.26  5997.3   34.79  6013.3   37.97  6312.3   38.32
  6343.3   19.19  6402.3   18.24  6432.3   35.44  6448.3   37.75  7195.1    40.5
#Mann= 7 ,-1 , 0
  3067.8     .99       0  3807.8     .08       0  4866.4     .04       0
  4929.6    .015       0  5068.7     .04       0  5119.7    .045       0
  5499.3      .1       0
#XS Ineff= 4 ,-1
  3067.8 4876.37   35.54 5735.95 6049.84   28.15 6049.84 6257.69   47.65
 6257.69 6516.44   28.15
Permanent Ineff=
       F       F       F       F
#Block Obstruct= 1 ,-1
 5362.45 5743.71    48.5
Bank Sta=4876.4,5119.7
XS Rating Curve= 0 ,0
Exp/Cntr=0.5,0.3