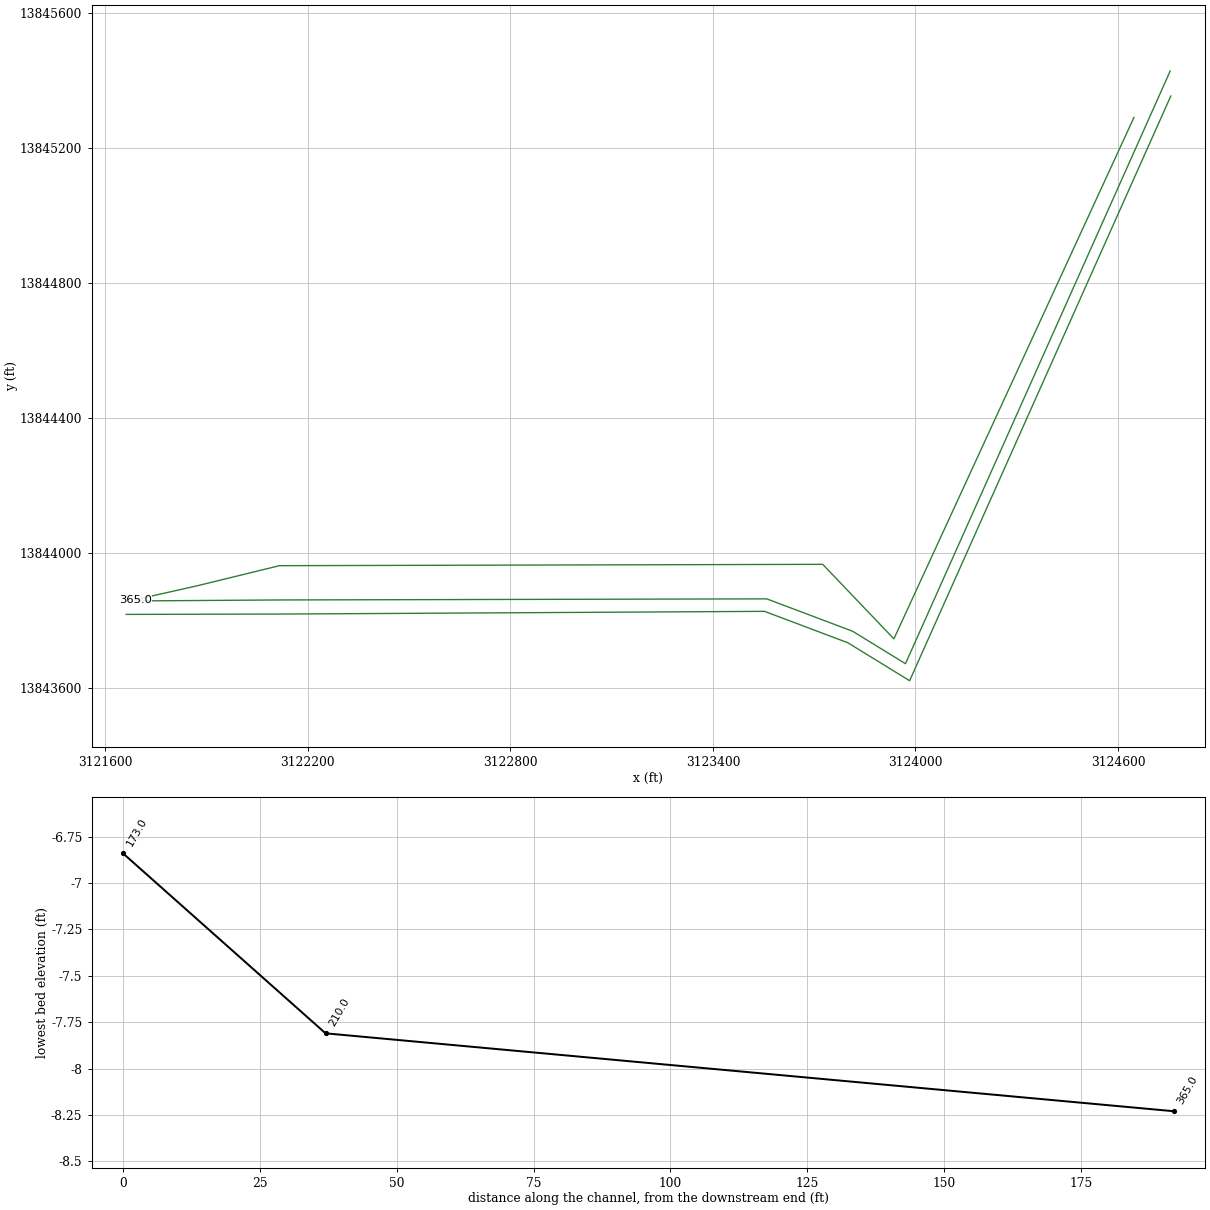
HEC-RAS study E100-00-00.prj: E100-00-00

--- E100-00-00.g02 (geometry) --- (continued)

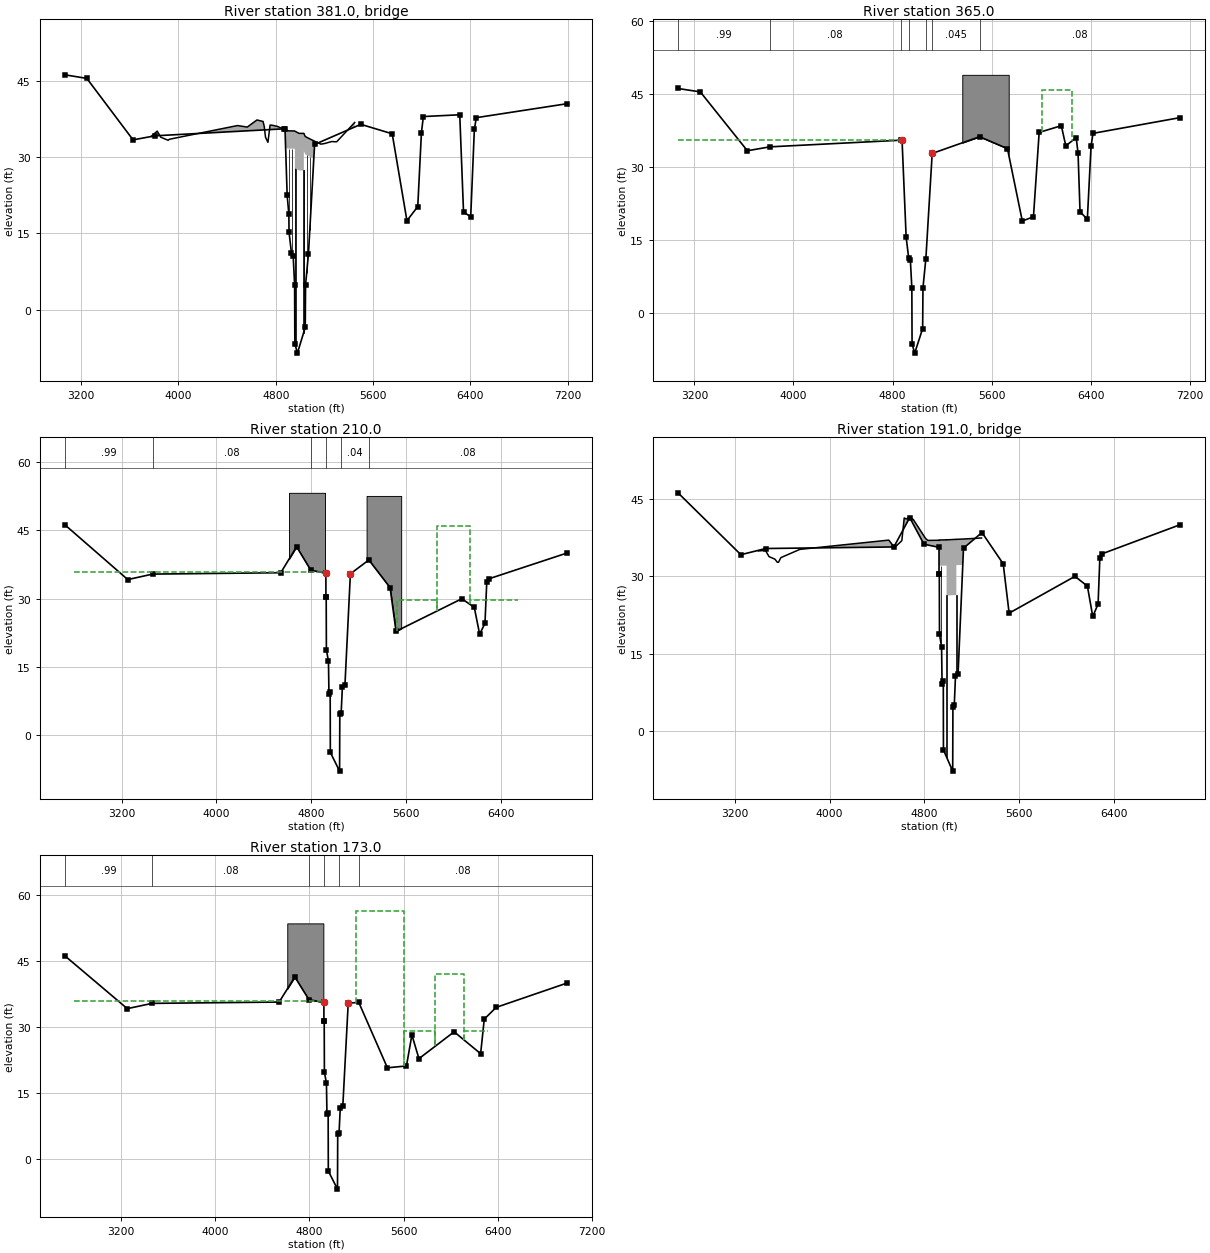
Type RM Length L Ch R = 3 ,381.0   ,,,
BEGIN DESCRIPTION:
UNION PACIFIC RR
Structure ID: E100-00-00-02
Bridge 18 degree skew to the channel flowline.  Did not model skew because the skew angle is less than 20 degrees.
END DESCRIPTION:
Bridge Culvert--1,0,-1,-1, 0
Deck Dist Width WeirC Skew NumUp NumDn MinLoCord MaxHiCord MaxSubmerge Is_Ogee
10,18,2.6,0, 77, 77, , , 0.95, 0, ,,,
  3776.1  3826.1  3856.1  3916.1  3926.1  4486.1  4566.1  4646.1  4696.1  4706.1
  4716.1  4736.1  4753.7  4756.1  4774.2  4802.4    4812  4839.8  4859.8  4866.4
  4876.4  4882.2 4882.31  4882.4 4883.39  4883.5 4883.71  4883.9  4884.9    4886
  4886.1  4892.7    4894  4897.8    4908  4909.5  4929.6  4943.6  4954.1  4955.4
  4955.7  4957.2    4958  4958.1  4978.4  4991.6  4992.5  5031.4  5031.5  5042.7
  5044.3  5045.2  5049.7 5049.81  5059.1  5068.7  5075.1  5080.1  5087.5    5090
  5095.3 5104.39  5104.5  5104.6 5105.49  5105.6 5105.71  5106.5  5119.7  5129.9
  5162.4  5170.9  5202.1  5232.5  5258.8  5300.7    5449
34.03911    35.1    33.9    33.3    33.5    36.2    35.9    37.3      37      36
    33.9    32.9    36.3   36.29   36.25   36.09   36.05   35.76   35.55   35.53
   35.51   35.49   35.49   35.49   35.47   35.47   35.47   35.47   35.44   35.44
   35.44   35.28   35.25   35.17   35.16   35.16   35.15   35.14   35.13   35.11
   35.11   35.09   35.09   35.09   34.83   34.67   34.66   34.66   34.66   34.04
   34.02   34.01   33.96   33.95   33.84   33.72   33.64   33.58   33.49   33.46
   33.39   33.28   33.28   33.28   33.29   33.29   33.29   33.28   33.12      33
   32.64   32.54   32.66   32.87   33.05      33    36.8
                                                                                
                                                                                
                                                                                
   31.94   31.78   31.75   31.67   31.66   31.66   31.65   31.64   31.63   31.61
   31.61   31.59   31.59   27.79   27.53   27.37   27.36   27.36   31.16   30.54
   30.52   30.51   30.46   30.45   30.34   30.22   30.14   30.08   29.99   29.96
   29.89   29.78   29.78
                                                        
  3776.1  3826.1  3856.1  3916.1  3926.1  4486.1  4566.1  4646.1  4696.1  4706.1
  4716.1  4736.1  4753.7  4756.1  4774.2  4802.4    4812  4839.8  4859.8  4866.4
  4876.4  4882.2 4882.31  4882.4 4883.39  4883.5 4883.71  4883.9  4884.9    4886
  4886.1  4892.7    4894  4897.8    4908  4909.5  4929.6  4943.6  4954.1  4955.4
  4955.7  4957.2    4958  4958.1  4978.4  4991.6  4992.5  5031.4  5031.5  5042.7
  5044.3  5045.2  5049.7 5049.81  5059.1  5068.7  5075.1  5080.1  5087.5    5090
  5095.3 5104.39  5104.5  5104.6 5105.49  5105.6 5105.71  5106.5  5119.7  5129.9
  5162.4  5170.9  5202.1  5232.5  5258.8  5300.7    5449
34.03911    35.1    33.9    33.3    33.5    36.2    35.9    37.3      37      36
    33.9    32.9    36.3   36.29   36.25   36.09   36.05   35.76   35.55   35.53
   35.51   35.49   35.49   35.49   35.47   35.47   35.47   35.47   35.44   35.44
   35.44   35.28   35.25   35.17   35.16   35.16   35.15   35.14   35.13   35.11
   35.11   35.09   35.09   35.09   34.83   34.67   34.66   34.66   34.66   34.04
   34.02   34.01   33.96   33.95   33.84   33.72   33.64   33.58   33.49   33.46
   33.39   33.28   33.28   33.28   33.29   33.29   33.29   33.28   33.12      33
   32.64   32.54   32.66   32.87   33.05      33    36.8
                                                                                
                                                                                
                                                                                
   31.94   31.78   31.75   31.67   31.66   31.66   31.65   31.64   31.63   31.61
   31.61   31.59   31.59   27.79   27.53   27.37   27.36   27.36   31.16   30.54
   30.52   30.51   30.46   30.45   30.34   30.22   30.14   30.08   29.99   29.96
   29.89   29.78   29.78
                                                        
Pier Skew, UpSta & Num, DnSta & Num=  ,4907.3, 2 ,4907.3, 2 , 0 , 0 , 0 ,,
       2       2
   16.98    32.5
       2       2
   17.38    32.5
Pier Skew, UpSta & Num, DnSta & Num=  ,4932.8, 2 ,4932.8, 2 , 0 , 0 , 0 ,,
       2       2
    9.81    32.5
       2       2
   10.21    32.5
Pier Skew, UpSta & Num, DnSta & Num=  ,4958.1, 2 ,4958.1, 2 , 0 , 0 , 0 ,,
       2       2
   -7.94    32.5
       2       2
   -7.54    32.5
Pier Skew, UpSta & Num, DnSta & Num=  ,4961.8, 2 ,4961.8, 2 , 0 , 0 , 0 ,,
       2       2
   -8.27    32.5
       2       2
   -7.87    32.5
Pier Skew, UpSta & Num, DnSta & Num=  ,5028.4, 2 ,5028.4, 2 , 0 , 0 , 0 ,,
       2       2
   -5.97    32.5
       2       2
   -5.57    32.5
Pier Skew, UpSta & Num, DnSta & Num=  ,5031.4, 2 ,5031.4, 2 , 0 , 0 , 0 ,,
       2       2
    -5.7    32.5
       2       2
    -5.3    32.5
Pier Skew, UpSta & Num, DnSta & Num=  ,5054.5, 2 ,5054.5, 2 , 0 , 0 , 0 ,,
       2       2
    6.96    32.5
       2       2
    7.36    32.5
Pier Skew, UpSta & Num, DnSta & Num=  ,5080.1, 2 ,5080.1, 2 , 0 , 0 , 0 ,,
       2       2
   11.89    32.5
       2       2
   12.29    32.5
BR Coef= 1 , 1 , 0 ,1.25, 0 ,,,0.8,0,2,0,
WSPro=,,,, 1 ,,,, 0 ,,,, 0 ,,,,-1 ,-1 ,-1 , 0 , 0 , 0 , 0 , 0
BR U #Sta/Elev= 30
  3067.8   46.18  3247.8   45.48  3627.8   33.38  3807.8   34.18  4866.4   35.55
  4876.4   35.52    4894   22.49    4908   18.77  4909.5   15.22  4929.6   11.06
  4943.6   10.48  4955.4    4.84  4957.2   -6.69  4978.4   -8.58  5042.7   -3.52
  5045.2    4.85  5068.7   10.87  5119.7   32.48  5499.3   36.44  5757.3   34.58
  5878.3   17.48  5967.3   20.26  5997.3   34.79  6013.3   37.97  6312.3   38.32
  6343.3   19.19  6402.3   18.24  6432.3   35.44  6448.3   37.75  7195.1    40.5
BR U #Mann= 7
  3067.8     .99  3807.8     .08  4866.4     .04  4929.6    .015  5068.7     .04
  5119.7    .045  5499.3      .1
BR D #Sta/Elev= 30
  3067.8   46.18  3247.8   45.48  3627.8   33.38  3807.8   34.18  4866.4   35.55
  4882.2   33.52  4884.9   28.49  4909.5   15.57  4929.6   11.41  4955.4    5.19
  4957.2   -6.34  4978.4   -8.23  5042.7   -3.17  5045.2     5.2  5068.7   11.22
  5119.7   32.83  5502.2   36.26  5727.2   33.82  5847.2   18.93  5937.2   19.81
  5983.2   37.15  6162.2   38.53  6198.2   34.39  6282.2   36.07  6297.2   32.88
  6313.2   20.84  6372.2   19.29  6402.2   34.38  6418.2   36.96  7122.6    40.2
BR D #Mann= 7
  3067.8     .99  3807.8     .08  4866.4     .04  4929.6    .015  5068.7     .04
  5119.7    .045  5502.2     .08
BC Design=,, 0 ,, 0 ,,,,,,
BC HTab HWMax=46.18
BC Use User HTab Curves=0
BC User HTab FreeFlow(D)= 0

Type RM Length L Ch R = 1 ,365.0   ,114.5,155,156
BEGIN DESCRIPTION:
Downstream Section of Bridge/Culvert/Weir  NOTES
Blocked out portions represent buildings.
The n-value in the low areas in the ROB is set to balance the flow in the ROB between cross sections.
END DESCRIPTION:
XS GIS Cut Line= 6
 3124647.383999213845290.5456123      3123936.15     13843745.76
      3123725.27     13843966.55      3122115.51     13843962.53
      3121870.38      13843902.6      3121688.12      13843861.7
#Sta/Elev= 30
  3067.8   46.18  3247.8   45.48  3627.8   33.38  3807.8   34.18  4866.4   35.55
  4876.4   35.52  4909.5   15.57  4929.6   11.41  4943.6   10.83  4955.4    5.19
  4957.2   -6.34  4978.4   -8.23  5042.7   -3.17  5045.2     5.2  5068.7   11.22
  5119.7   32.83  5502.2   36.26  5727.2   33.82  5847.2   18.93  5937.2   19.81
  5983.2   37.15  6162.2   38.53  6198.2   34.39  6282.2   36.07  6297.2   32.88
  6313.2   20.84  6372.2   19.29  6402.2   34.38  6418.2   36.96  7122.6    40.2
#Mann= 7 ,-1 , 0
  3067.8     .99       0  3807.8     .08       0  4866.4     .04       0
  4929.6    .015       0  5068.7     .04       0  5119.7    .045       0
  5502.2     .08       0
#XS Ineff= 4 ,-1
  3067.8 4866.67   35.57 5723.22 6003.18   29.14 6003.18 6244.96   45.93
 6244.96 6440.08   29.14
Permanent Ineff=
       F       F       F       F
#Block Obstruct= 1 ,-1
 5362.45 5737.39   48.99
Bank Sta=4876.4,5119.7
XS Rating Curve= 0 ,0
Exp/Cntr=0.5,0.3

Type RM Length L Ch R = 1 ,210.0   ,37.7,37,36
BEGIN DESCRIPTION:
Upstream Section of Bridge/Culvert/Weir  NOTES
Blocked out portions represent buildings.
The n-value in the low areas in the ROB is set to balance the flow in the ROB between cross sections.
END DESCRIPTION:
XS GIS Cut Line= 6
      3124754.86     13845428.29      3123970.46     13843672.15
      3123814.11      13843768.2      3123559.47     13843864.24
       3122110.3     13843860.97      3121703.34      13843858.2
#Sta/Elev= 30
  2722.6   46.17  3252.6   34.17  3462.6   35.37  4542.6   35.67    4676   41.37
  4796.1    36.2    4923    35.6  4923.2   30.42  4925.6   30.41  4927.2   18.77
  4944.7   16.27  4948.9    9.16  4959.2     9.6  4960.5    -3.7  5038.5   -7.81
  5040.4    4.72  5051.9    5.01  5062.1   10.65  5083.8   11.11  5129.6   35.43
  5285.3   38.47  5464.3    32.4  5514.3   22.83  6069.3   29.97  6174.3   28.07
  6219.3    22.2  6264.3   24.58  6279.3    33.6  6294.3   34.31  6957.5      40
#Mann= 6 ,-1 , 0
  2722.6     .99       0  3462.6     .08       0  4796.1     .04       0
    4923    .015       0  5051.9     .04       0  5285.3     .08       0
#XS Ineff= 5 ,-1
    2801 4910.65   35.83 5137.43    5197      30 5520.68 5860.02   29.75
 5860.02 6135.74   45.88 6135.74 6538.71   29.75
Permanent Ineff=
       F       F       F       F       F
#Block Obstruct= 2 ,-1
 4611.79 4915.72   53.18 5266.17 5557.79    52.5
Bank Sta=4923,5129.6
XS Rating Curve= 0 ,0
Exp/Cntr=0.5,0.3

Type RM Length L Ch R = 3 ,191.0   ,,,
BEGIN DESCRIPTION:
UNION PACIFIC RR
Structure ID: E100-00-00-01
END DESCRIPTION:
Bridge Culvert--1,0,-1,-1, 0
Deck Dist Width WeirC Skew NumUp NumDn MinLoCord MaxHiCord MaxSubmerge Is_Ogee
10,18,2.6,0, 75, 75, , , 0.95, 0, ,,,
  3399.8  3459.8  3489.8  3539.8  3559.8  3569.8  3589.8  3749.8  4499.8  4539.8
  4559.8  4609.8  4629.8    4646    4676  4700.4    4706  4810.4  4829.7    4848
    4900  4918.4    4923  4923.2 4923.89    4924 4924.11  4925.6  4925.7 4925.81
  4925.9  4926.5  4927.2  4939.4  4944.7  4948.9  4956.1  4957.3  4959.2  4960.2
  4960.5  4976.3  4984.2  4986.7  4986.8  5005.6  5027.7  5038.5  5039.7  5040.4
  5051.9  5062.1    5069  5069.1  5083.8  5085.1  5091.2  5098.7  5111.3  5112.9
  5115.9  5116.1 5118.89    5119  5119.1 5120.69  5120.8 5120.91  5129.6    5143
  5174.8  5202.8    5222  5281.3  5281.4
    34.9      35    33.8    33.3    32.7    32.7    33.6    35.2      37    35.8
    35.8    36.9    41.3    41.1    41.4   41.08   41.01    37.3   36.94   36.95
   36.96   36.97   36.94   36.94   36.94   36.94   36.94   36.97   36.97   36.98
   36.98   37.02   37.02   37.03   37.03   37.03   37.04   37.04   37.04   37.04
   37.04   37.05   37.05   37.05   37.07   37.07    37.1   37.11   37.11   37.11
   37.13   37.14   37.14   37.15   37.16   37.16   37.17   37.18   37.19    37.2
    37.2    37.2    37.2    37.2    37.2    37.2    37.2    37.2   37.21   37.23
   37.27    37.3   37.33   37.41   37.41
                                                                                
                                                                                
                                                           31.97   31.97   31.98
   31.98   32.02   32.02   32.03   32.03   32.03   32.04   32.04   32.04   32.04
   32.04   32.05   32.05   32.05   26.27   26.27    26.3   26.31   26.31   26.31
   26.33   26.34   26.34   32.15   32.16   32.16   32.17   32.18   32.19    32.2
    32.2    32.2    32.2
                                        
  3399.8  3459.8  3489.8  3539.8  3559.8  3569.8  3589.8  3749.8  4499.8  4539.8
  4559.8  4609.8  4629.8    4646    4676  4700.4    4706  4810.4  4829.7    4848
    4900  4918.4    4923  4923.2 4923.89    4924 4924.11  4925.6  4925.7 4925.81
  4925.9  4926.5  4927.2  4939.4  4944.7  4948.9  4956.1  4957.3  4959.2  4960.2
  4960.5  4976.3  4984.2  4986.7  4986.8  5005.6  5027.7  5038.5  5039.7  5040.4
  5051.9  5062.1    5069  5069.1  5083.8  5085.1  5091.2  5098.7  5111.3  5112.9
  5115.9  5116.1 5118.89    5119  5119.1 5120.69  5120.8 5120.91  5129.6    5143
  5174.8  5202.8    5222  5281.3  5281.4
    34.9      35    33.8    33.3    32.7    32.7    33.6    35.2      37    35.8
    35.8    36.9    41.3    41.1    41.4   41.08   41.01    37.3   36.94   36.95
   36.96   36.97   36.94   36.94   36.94   36.94   36.94   36.97   36.97   36.98
   36.98   37.02   37.02   37.03   37.03   37.03   37.04   37.04   37.04   37.04
   37.04   37.05   37.05   37.05   37.07   37.07    37.1   37.11   37.11   37.11
   37.13   37.14   37.14   37.15   37.16   37.16   37.17   37.18   37.19    37.2
    37.2    37.2    37.2    37.2    37.2    37.2    37.2    37.2   37.21   37.23
   37.27    37.3   37.33   37.41   37.41
                                                                                
                                                                                
                                                           31.97   31.97   31.98
   31.98   32.02   32.02   32.03   32.03   32.03   32.04   32.04   32.04   32.04
   32.04   32.05   32.05   32.05   26.27   26.27    26.3   26.31   26.31   26.31
   26.33   26.34   26.34   32.15   32.16   32.16   32.17   32.18   32.19    32.2
    32.2    32.2    32.2
                                        
Pier Skew, UpSta & Num, DnSta & Num=  ,4939.4, 2 ,4939.4, 2 , 0 , 0 , 0 ,,
     1.5     1.5
   15.96      35
     1.5     1.5
   17.18      35
Pier Skew, UpSta & Num, DnSta & Num=  ,4986.8, 2 ,4986.8, 2 , 0 , 0 , 0 ,,
       3       3
   -8.58      35
       3       3
   -7.36      35
Pier Skew, UpSta & Num, DnSta & Num=  ,5069, 2 ,5069, 2 , 0 , 0 , 0 ,,
      10      10
    9.74      35
      10      10
   10.96      35
BR Coef= 1 , 1 , 0 ,1.25, 0 ,,,0.8,0,2,0,
WSPro=,,,, 1 ,,,, 0 ,,,, 0 ,,,,-1 ,-1 ,-1 , 0 , 0 , 0 , 0 , 0
BR U #Sta/Elev= 30
  2722.6   46.17  3252.6   34.17  3462.6   35.37  4542.6   35.67    4676   41.37
  4796.1    36.2    4923    35.6  4923.2   30.42  4925.6   30.41  4927.2   18.77
  4944.7   16.27  4948.9    9.16  4959.2     9.6  4960.5    -3.7  5038.5   -7.81
  5040.4    4.72  5051.9    5.01  5062.1   10.65  5083.8   11.11  5129.6   35.43
  5285.3   38.47  5464.3    32.4  5514.3   22.83  6069.3   29.97  6174.3   28.07
  6219.3    22.2  6264.3   24.58  6279.3    33.6  6294.3   34.31  6957.5      40
BR U #Mann= 6
  2722.6     .99  3462.6     .08  4796.1     .04    4923    .015  5051.9     .04
  5285.3     .08
BR D #Sta/Elev= 30
  2722.6   46.17  3252.6   34.17  3462.6   35.37  4542.6   35.67    4676   41.37
  4796.1    36.2    4923    35.6  4923.2   31.39  4925.6   31.38  4927.2   19.74
  4944.7   17.24  4948.9   10.13  4959.2   10.57  4960.5   -2.73  5038.5   -6.84
  5040.4    5.69  5051.9    5.98  5062.1   11.62  5083.8   12.08  5129.6   35.43
  5219.5   35.58  5462.5   20.73  5624.5   21.15  5670.5    28.2  5730.5   22.81
  6029.5   28.91  6254.5   23.94  6285.5   31.79  6386.5   34.46    6990      40
BR D #Mann= 6
  2722.6     .99  3462.6     .08  4796.1     .04    4923    .015  5051.9     .04
  5219.5     .08
BC Design=,, 0 ,, 0 ,,,,,,
BC HTab HWMax=46.17
BC Use User HTab Curves=0
BC User HTab FreeFlow(D)= 0

Type RM Length L Ch R = 1 ,173.0   ,614,615,616
BEGIN DESCRIPTION:
Downstream Section of Bridge/Culvert/Weir  NOTES
Blocked out portions represent buildings.
The n-value in the low areas in the ROB is set to balance the flow in the ROB between cross sections.
END DESCRIPTION:
XS GIS Cut Line= 6
      3124756.56     13845353.99       3123982.8     13843621.68
      3123799.74     13843734.13       3123552.9     13843827.24
      3122136.34      13843819.3      3121661.48      13843818.2
#Sta/Elev= 30
  2722.6   46.17  3252.6   34.17  3462.6   35.37  4542.6   35.67    4676   41.37
  4796.1    36.2    4923    35.6  4923.2   31.39  4925.6   31.38  4927.2   19.74
  4944.7   17.24  4948.9   10.13  4959.2   10.57  4960.5   -2.73  5038.5   -6.84
  5040.4    5.69  5051.9    5.98  5062.1   11.62  5083.8   12.08  5129.6   35.43
  5219.5   35.58  5462.5   20.73  5624.5   21.15  5670.5    28.2  5730.5   22.81
  6029.5   28.91  6254.5   23.94  6285.5   31.79  6386.5   34.46    6990      40
#Mann= 6 ,-1 , 0
  2722.6     .99       0  3462.6     .08       0  4796.1     .04       0
    4923    .015       0  5051.9     .04       0  5219.5     .08       0
#XS Ineff= 5 ,-1
    2801 4910.65   35.83 5197.24 5605.51    56.4 5605.51 5870.63   29.18
 5870.63 6109.23      42 6109.23 6316.01   29.18
Permanent Ineff=
       F       F       F       F       F
#Block Obstruct= 1 ,-1
 4611.79 4918.34   53.55
Bank Sta=4923,5129.6
XS Rating Curve= 0 ,0
Exp/Cntr=0.5,0.3

Chan Stop Cuts=-1
Use User Specified Reach Order=0

--- E100-00-00.g01 (geometry) ---

Geom Title=E100-00-00 2014(Ext for MP)
Program Version=4.00
BEGIN GEOM DESCRIPTION:
-Added XS 26225 and 26307.3 from Dodson's Worthshire LOMR model
-Added XS 33909.08 and 33962.58 from Dodson's W. 21st Street LOMR model
-Updated North Houston Rosslyn bridge deck & ineffective areas.
-Replaced 0.99 n-values in E500-04-00 with ineffective areas
-Contraction/expansion coeff. of 75698 and 75102 increase to 0.4/0.6 to reflect abrupt channel area increase for E500-04-00.
-Added new cross sections between 57918 and 62890 (Sept 2009)
-Updated geometry of 610 and RR bridge near Yale to reflect survey data (Sept 2009)
-Updated N values along WOB (Sept 2009)
END GEOM DESCRIPTION:

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
River Reach=E100-00-00      ,E100-00-00_N034

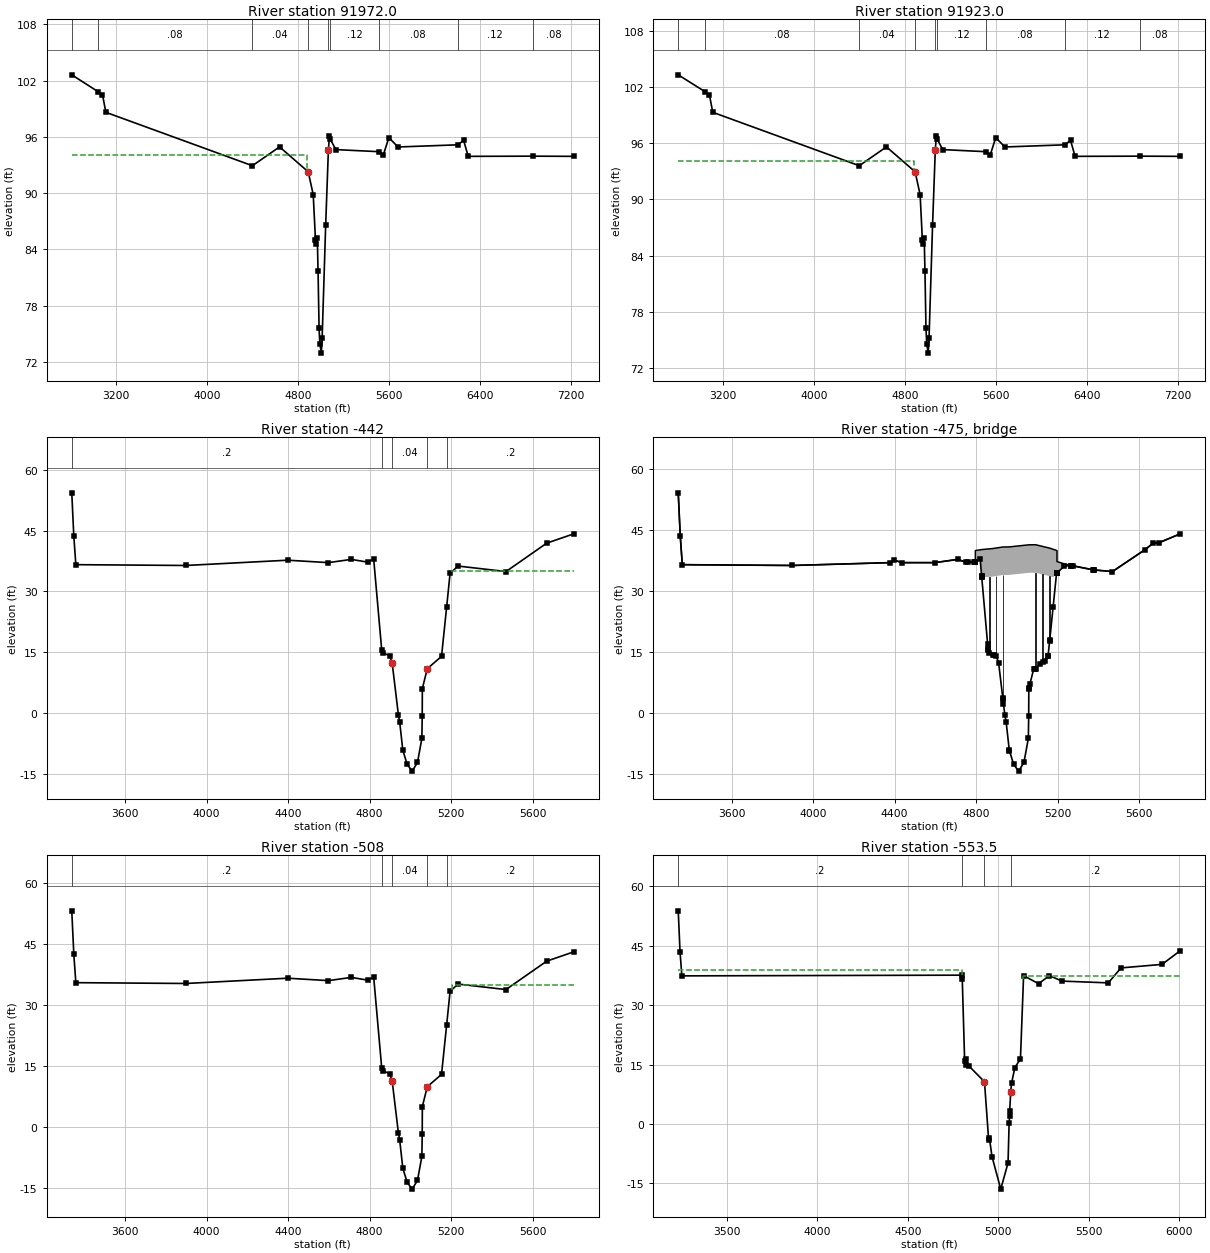
Type RM Length L Ch R = 1 ,91972.0 ,48,49,52.4
BEGIN DESCRIPTION:
Upstream Section of Bridge/Culvert/Weir
ross section spills into E117-00-00, therefore extending the right overbank to contain the floodplain is not possible.  Also levee added on the left overbank to prevent shortening the cross section (real levee not present).
END DESCRIPTION:
XS GIS Cut Line= 5
      3065574.29     13885874.99      3065643.27     13883866.71
      3065653.71     13883424.68       3065663.9     13882426.24
      3065687.86     13881456.36
#Sta/Elev= 30
  2808.2  102.62  3037.6  100.84  3078.3  100.52  3108.3   98.62  4398.3   92.92
  4637.6   94.93    4890   92.27    4934   89.83  4953.8      85  4962.1   84.52
  4969.8   85.25  4976.5   81.72  4985.5   75.55  4992.2   73.94    5005   72.92
  5012.5   74.52  5043.5   86.56  5067.5   94.59  5076.7   96.05  5084.5   95.74
  5133.3   94.64  5509.9   94.42  5549.9   94.02  5599.9   95.92  5679.9   94.92
  6206.3   95.15  6258.4   95.62  6298.4   93.92  6868.7   93.94  7228.5   93.92
#Mann= 9 ,-1 , 0
  2808.2     .12       0  3037.6     .08       0  4398.3     .04       0
    4890     .04       0  5067.5     .04       0  5084.5     .12       0
  5509.9     .08       0  6206.3     .12       0  6868.7     .08       0
Levee=-1,2803.3,102.62,0,,,,
#XS Ineff= 2 , 0
       0    4880    94.1  5077.5       0    93.7
Permanent Ineff=
       F       F
Bank Sta=4890,5067.5
XS Rating Curve= 0 ,0
Exp/Cntr=0.5,0.3

Type RM Length L Ch R = 1 ,91923.0 ,99,100,111.9
BEGIN DESCRIPTION:
Downstream Section of Bridge/Culvert/Weir
Cross section spills into E117-00-00, therefore extending the right overbank to contain the floodplain is not possible.  Also levee added on the left overbank to prevent shortening the cross section (real levee not present).
END DESCRIPTION:
XS GIS Cut Line= 5
      3065622.53     13885875.12      3065691.52     13883866.68
      3065701.97     13883424.29      3065712.16     13882426.04
      3065747.23     13881456.83
#Sta/Elev= 30
  2804.4  103.29  3037.6  101.51  3078.3  101.19  3108.3   99.29  4398.3   93.59
  4637.6    95.6    4890   92.94    4934    90.5  4953.8   85.67  4962.1   85.19
  4969.8   85.92  4976.5   82.39  4985.5   76.22  4992.2   74.61    5005   73.59
  5012.5   75.19  5043.5   87.23  5067.5   95.26  5076.7   96.72  5084.5   96.41
  5133.3   95.31  5509.9   95.09  5549.9   94.69  5599.9   96.59  5679.9   95.59
  6206.3   95.82  6258.4   96.29  6298.4   94.59  6868.7   94.61  7224.7   94.59
#Mann= 9 ,-1 , 0
  2804.4     .12       0  3037.6     .08       0  4398.3     .04       0
    4890     .04       0  5067.5     .04       0  5084.5     .12       0
  5509.9     .08       0  6206.3     .12       0  6868.7     .08       0
Levee=-1,2803.3,103.29,0,,,,
#XS Ineff= 2 , 0
       0 4883.33    94.1 5074.17       0    93.7
Permanent Ineff=
       F       F
Bank Sta=4890,5067.5
XS Rating Curve= 0 ,0
Exp/Cntr=0.5,0.3

Type RM Length L Ch R = 1 ,-442    ,66,66,66
BEGIN DESCRIPTION:
Upstream Section of Bridge/Culvert/Weir
Buffalo Bayou Section 109551.7
END DESCRIPTION:
XS GIS Cut Line= 6
      3124387.16     13844760.11      3124238.52     13844263.41
      3124124.05      13844000.2      3123957.07     13843356.86
       3123547.4     13842998.58      3123104.14     13842921.83
#Sta/Elev= 30
  3337.8   54.29  3347.8   43.59  3357.8   36.59  3897.8   36.39  4397.8   37.69
  4597.8   37.09  4710.1   37.89  4793.1   37.19    4820   38.02  4859.3   15.67
  4865.3   14.84  4898.2    14.2  4910.7   12.42  4941.5    -.47  4947.9   -2.22
  4963.1   -9.13  4984.6  -12.63    5009  -14.28  5035.1  -12.14  5056.7   -6.21
  5058.4    -.65    5059    6.06  5083.3   10.96  5153.2   13.99  5178.1   26.07
  5195.1   34.43  5233.8   36.25  5469.6   34.89  5669.6   41.89  5802.8   44.19
#Mann= 5 , 1 , 0
  3337.8      .2       0  4859.3      .1       0  4910.7     .04       0
  5083.3      .1       0  5178.1      .2       0
#XS Ineff= 2 , 0
       0    4815    36.8    5205       0      35
Permanent Ineff=
       F       F
Bank Sta=4910.7,5083.3
XS Rating Curve= 0 ,0
Exp/Cntr=0.5,0.3

Type RM Length L Ch R = 3 ,-475    ,,,
BEGIN DESCRIPTION:
FANNIN STREET (Buffalo Bayou)
Structure ID: WOO-19
END DESCRIPTION:
Bridge Culvert--1,0,-1,-1, 0
Deck Dist Width WeirC Skew NumUp NumDn MinLoCord MaxHiCord MaxSubmerge Is_Ogee
10,46,2.6,0, 34, 34, , , 0.95, 0, 1,1,,
  3337.8  3347.8  3357.8  3897.8  4377.8  4397.8  4437.8  4597.8  4710.1  4750.1
    4760  4793.1 4796.49  4796.6    4820  4827.8  4856.9  4881.5  4931.2  4963.6
    5059  5092.3  5161.6  5178.1  5197.4 5197.51  5233.8  5268.5  5377.7  5469.6
  5629.6  5669.6  5697.8  5802.8
    54.2    43.5    36.5    36.3      37    37.6      37      37    37.8    37.1
   37.23   37.25   37.28   39.98   40.15   40.22   40.36   40.47   40.85   40.88
   41.39   41.41   40.57   40.29   39.96   37.26   36.69   36.29    35.2    34.8
    40.2    41.8    41.9    44.1
    54.2    43.5    36.5    36.3      37    37.6      37      37    37.8    37.1
    37.1    37.1    37.2   37.21   37.93   33.48   33.46   33.57   33.95   33.98
   34.49   34.51   33.67   33.39   34.45   34.45   36.16   36.28    35.2    34.8
    40.2    41.8    41.9    44.1
  3337.8  3347.8  3357.8  3897.8  4377.8  4397.8  4437.8  4597.8  4710.1  4750.1
    4760  4793.1 4796.49  4796.6    4820  4827.8  4856.9  4881.5  4931.2  4963.6
    5059  5092.3  5161.6  5178.1  5197.4 5197.51  5233.8  5268.5  5377.7  5469.6
  5629.6  5669.6  5697.8  5802.8
    54.2    43.5    36.5    36.3      37    37.6      37      37    37.8    37.1
   37.23   37.25   37.28   39.98   40.15   40.22   40.36   40.47   40.85   40.88
   41.39   41.41   40.57   40.29   39.96   37.26   36.69   36.29    35.2    34.8
    40.2    41.8    41.9    44.1
   53.52   42.82   35.82   35.62   36.32   36.92   36.32   36.32   37.12   36.42
   36.42   36.42   36.52   36.53   37.25    32.8   32.78   32.89   33.27    33.3
   33.81   33.83   32.99   32.71   33.77   33.77   35.48    35.6   34.52   34.12
   39.52   41.12   41.22   43.42
Pier Skew, UpSta & Num, DnSta & Num=  ,4865.3, 2 ,4865.3, 2 , 0 , 0 , 0 ,,
     2.5     2.5
   13.72   34.51
     2.5     2.5
   13.04   33.83
Pier Skew, UpSta & Num, DnSta & Num=  ,4898.2, 2 ,4898.2, 2 , 0 , 0 , 0 ,,
     2.5     2.5
   12.93   34.69
     2.5     2.5
   12.25   34.01
Pier Skew, UpSta & Num, DnSta & Num=  ,4931.6, 2 ,4931.6, 2 , 0 , 0 , 0 ,,
     2.5     2.5
    1.96   34.95
     2.5     2.5
    1.28   34.27
Pier Skew, UpSta & Num, DnSta & Num=  ,5091.6, 2 ,5091.6, 2 , 0 , 0 , 0 ,,
     2.5     2.5
    9.83   35.51
     2.5     2.5
    9.15   34.83
Pier Skew, UpSta & Num, DnSta & Num=  ,5126.8, 2 ,5126.8, 2 , 0 , 0 , 0 ,,
     2.5     2.5
   11.37   35.11
     2.5     2.5
   10.69   34.43
Pier Skew, UpSta & Num, DnSta & Num=  ,5161.4, 2 ,5161.4, 2 , 0 , 0 , 0 ,,
     2.5     2.5
   16.17   34.69
     2.5     2.5
   15.49   34.01
Abutment Skew #Up #Dn= , 2 , 2
  4827.5  4856.9
   33.53   16.87
  4827.5  4856.9
   32.85   16.19
Abutment Skew #Up #Dn= , 2 , 2
  5153.3 5196.89
   13.95   34.41
  5153.3 5196.89
   13.27   33.73
BR Coef= 1 , 1 , 0 ,1.25, 0 ,,,0.8,0,2,0,
WSPro=,,,, 1 ,,,, 0 ,,,, 0 ,,,,-1 ,-1 ,-1 , 0 , 0 , 0 , 0 , 0
BR U #Sta/Elev= 74
  3337.8    54.2  3347.8    43.5  3357.8    36.5  3897.8    36.3  4377.8      37
  4397.8    37.6  4437.8      37  4597.8      37  4710.1    37.8  4750.1    37.1
    4760    37.1  4789.6    37.1  4793.1    37.1 4796.49    37.2  4796.6   37.21
 4796.71   37.21    4820   37.93  4827.5   33.65 4827.61   33.59  4827.7   33.53
  4827.8   33.48  4856.9   16.87  4859.1   15.61  4859.3   15.58  4865.3   14.75
  4881.5   14.34  4889.3   14.23  4898.2   14.11  4910.7   12.33  4931.2    3.68
  4931.6    3.51  4934.5    2.24  4941.5    -.56  4947.9   -2.31  4963.1   -9.22
  4963.6    -9.3  4984.6  -12.72    5009  -14.37  5035.1  -12.23  5056.7    -6.3
  5058.4    -.74    5059    5.97  5059.5    6.07    5065    7.21  5083.3   10.87
  5091.6   10.82  5092.3   10.86  5113.2   11.93  5126.8   12.42  5138.5   12.74
  5153.2    13.9  5153.3   13.95  5161.4   17.76  5161.6   17.86  5178.1   25.98
  5195.1   34.34 5196.69   34.41  5196.8   34.42  5196.9   34.42 5197.29   34.44
  5197.4   34.45 5197.51   34.45  5233.8   36.16  5268.2   36.27  5268.5   36.28
  5276.3    36.2  5376.3   35.21  5377.7    35.2  5379.6    35.2  5469.6    34.8
  5629.6    40.2  5669.6    41.8  5697.8    41.9  5802.8    44.1
BR U #Mann= 5
  3337.8      .2  4859.3      .1  4910.7     .04  5083.3      .1  5178.1      .2
BR U Banks=4910.7,5083.3
BR D #Sta/Elev= 74
  3337.8   53.52  3347.8   42.82  3357.8   35.82  3897.8   35.62  4377.8   36.32
  4397.8   36.92  4437.8   36.32  4597.8   36.32  4710.1   37.12  4750.1   36.42
    4760   36.42  4789.6   36.42  4793.1   36.42 4796.49   36.52  4796.6   36.53
 4796.71   36.53    4820   37.25  4827.5   32.97 4827.61   32.91  4827.7   32.85
  4827.8    32.8  4856.9   16.19  4859.1   14.93  4859.3    14.9  4865.3   14.07
  4881.5   13.66  4889.3   13.55  4898.2   13.43  4910.7   11.65  4931.2       3
  4931.6    2.83  4934.5    1.56  4941.5   -1.24  4947.9   -2.99  4963.1    -9.9
  4963.6   -9.98  4984.6   -13.4    5009  -15.05  5035.1  -12.91  5056.7   -6.98
  5058.4   -1.42    5059    5.29  5059.5    5.39    5065    6.53  5083.3   10.19
  5091.6   10.14  5092.3   10.18  5113.2   11.25  5126.8   11.74  5138.5   12.06
  5153.2   13.22  5153.3   13.27  5161.4   17.08  5161.6   17.18  5178.1    25.3
  5195.1   33.66 5196.69   33.73  5196.8   33.74  5196.9   33.74 5197.29   33.76
  5197.4   33.77 5197.51   33.77  5233.8   35.48  5268.2   35.59  5268.5    35.6
  5276.3   35.52  5376.3   34.53  5377.7   34.52  5379.6   34.52  5469.6   34.12
  5629.6   39.52  5669.6   41.12  5697.8   41.22  5802.8   43.42
BR D #Mann= 5
  3337.8      .2  4859.3      .1  4910.7     .04  5083.3      .1  5178.1      .2
BR D Banks=4910.7,5083.3
BC Design=,, 0 ,, 0 ,,,,,,
BC HTab HWMax=54.29
BC Use User HTab Curves=0
BC User HTab FreeFlow(D)= 0

Type RM Length L Ch R = 1 ,-508    ,45.5,45.5,45.5
BEGIN DESCRIPTION:
Downstream Section of Bridge/Culvert/Weir
Buffalo Bayou Section 109485.7
END DESCRIPTION:
XS GIS Cut Line= 6
       3124426.1     13844706.82      3124277.46     13844210.13
      3124162.99     13843946.92      3123996.01     13843303.58
      3123586.34      13842945.3      3123143.08     13842868.55
#Sta/Elev= 30
  3337.8   53.26  3347.8   42.56  3357.8   35.56  3897.8   35.36  4397.8   36.66
  4597.8   36.06  4710.1   36.86  4793.1   36.16    4820   36.99  4859.3   14.64
  4865.3   13.81  4898.2   13.17  4910.7   11.39  4941.5    -1.5  4947.9   -3.25
  4963.1  -10.16  4984.6  -13.66    5009  -15.31  5035.1  -13.17  5056.7   -7.24
  5058.4   -1.68    5059    5.03  5083.3    9.93  5153.2   12.96  5178.1   25.04
  5195.1    33.4  5233.8   35.22  5469.6   33.86  5669.6   40.86  5802.8   43.16
#Mann= 5 , 1 , 0
  3337.8      .2       0  4859.3      .1       0  4910.7     .04       0
  5083.3      .1       0  5178.1      .2       0
#XS Ineff= 2 , 0
       0    4815    36.8    5205       0      35
Permanent Ineff=
       F       F
Bank Sta=4910.7,5083.3
XS Rating Curve= 0 ,0
Exp/Cntr=0.5,0.3

Type RM Length L Ch R = 1 ,-553.5  ,90,90,90
BEGIN DESCRIPTION:
Upstream Section of Bridge/Culvert/Weir
Buffalo Bayou Section 109440.2
END DESCRIPTION:
XS GIS Cut Line= 6
      3124436.18      13844760.7      3124179.47      13844055.4
      3123930.99     13843066.86      3123841.91     13842892.27
      3123591.74     13842543.99      3123293.69     13842304.09
#Sta/Elev= 30
  3229.7   53.82  3239.7   43.45  3249.7   37.39  4799.8   37.57  4801.4   36.52
  4814.5    15.9  4822.8    14.8  4824.1   16.31  4838.6    14.6  4924.3   10.64
  4947.4   -4.08  4951.5   -3.59  4965.9   -8.25  5014.3  -16.48  5054.6   -9.86
  5060.7     .31  5063.7    1.93  5063.8    3.36  5069.6    8.16  5074.1   10.23
  5092.3   14.24  5123.3    16.4  5140.7   37.45  5223.6   35.41  5283.6   37.44
  5353.6   36.07  5609.6   35.62  5679.6    39.4  5906.7   40.29  6007.9   43.76
#Mann= 4 , 1 , 0
  3229.7      .2       0  4799.8     .08       0  4924.3     .04       0
  5069.6      .2       0
#XS Ineff= 2 , 0
       0    4800    38.9    5140       0    37.3
Permanent Ineff=
       F       F
Bank Sta=4924.3,5069.6
XS Rating Curve= 0 ,0
Exp/Cntr=0.5,0.3

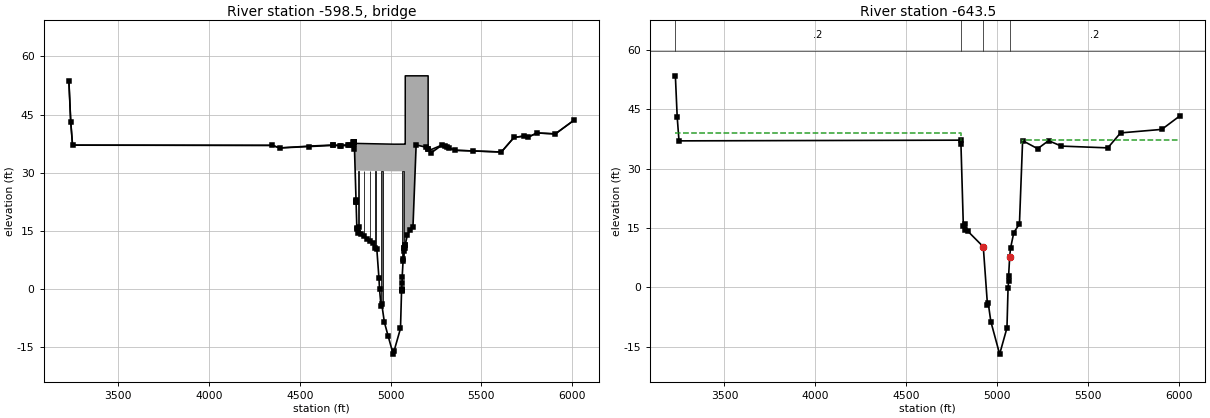
Type RM Length L Ch R = 3 ,-598.5  ,,,
BEGIN DESCRIPTION:
SAN JACINTO STREET (Buffalo Bayou)
Structure ID: WOO-18
END DESCRIPTION:
Bridge Culvert--1,0,-1,-1, 0
Deck Dist Width WeirC Skew NumUp NumDn MinLoCord MaxHiCord MaxSubmerge Is_Ogee
10,70,2.6,0, 38, 38, , , 0.95, 0, 1,1,,
  3229.7  3239.7  3249.7  4349.7  4389.7  4550.9  4680.9  4719.3  4766.6    4792
  4792.4  4798.9  4799.8  4801.4 4810.01  4810.1  5019.6 5076.59  5076.7  5080.6
  5080.8  5092.3  5108.3  5123.3  5140.7  5197.7  5206.7  5206.8  5223.6  5283.6
  5353.6  5609.6  5679.6  5736.7  5756.7  5806.7  5906.7  6007.9
   53.56   43.19   37.13   37.07   36.41    36.9   37.18   37.09   37.22   37.43
   37.83   37.91   37.49    37.5   37.57   37.58   37.38   37.39   37.39   37.39
      55      55      55      55      55      55      55    36.6      36   37.19
   35.82   35.36   39.14   39.47    39.2   40.27   40.03    43.5
   53.56   43.19   37.13   37.07   36.41   36.77   37.06   36.98   37.09   37.13
   37.82    37.9   37.31   36.26   22.71   30.58   30.38   30.39   10.54    11.4
   11.45   13.98   15.36   16.14   37.19   36.57   36.08   36.07   35.15   37.18
   35.81   35.36   39.14   39.47    39.2   40.27   40.03    43.5
  3229.7  3239.7  3249.7  4349.7  4389.7  4550.9  4680.9  4719.3  4766.6    4792
  4792.4  4798.9  4799.8  4801.4 4810.01  4810.1  5019.6 5076.59  5076.7  5080.6
  5080.8  5092.3  5108.3  5123.3  5140.7  5197.7  5206.7  5206.8  5223.6  5283.6
  5353.6  5609.6  5679.6  5736.7  5756.7  5806.7  5906.7  6007.9
   53.56   43.19   37.13   37.07   36.41    36.9   37.18   37.09   37.22   37.43
   37.83   37.91   37.49    37.5   37.57   37.58   37.38   37.39   37.39   37.39
      55      55      55      55      55      55      55    36.6      36   37.19
   35.82   35.36   39.14   39.47    39.2   40.27   40.03    43.5
   53.42   43.05   36.99   36.93   36.27   36.63   36.92   36.84   36.95   36.99
   37.68   37.76   37.17   36.12   22.57   30.44   30.24   30.25    10.4   11.26
   11.31   13.84   15.22      16   37.05   36.43   35.94   35.93   35.01   37.04
   35.67   35.22      39   39.33   39.06   40.13   39.89   43.36
Pier Skew, UpSta & Num, DnSta & Num=  ,4824.1, 2 ,4824.1, 2 , 0 , 0 , 0 ,,
       2       2
   13.89   31.57
       2       2
   13.75   31.43
Pier Skew, UpSta & Num, DnSta & Num=  ,4854.8, 2 ,4854.8, 2 , 0 , 0 , 0 ,,
       2       2
   12.65   31.54
       2       2
   12.51    31.4
Pier Skew, UpSta & Num, DnSta & Num=  ,4886.2, 2 ,4886.2, 2 , 0 , 0 , 0 ,,
       2       2
   11.48   31.51
       2       2
   11.34   31.37
Pier Skew, UpSta & Num, DnSta & Num=  ,4916.6, 2 ,4916.6, 2 , 0 , 0 , 0 ,,
       2       2
    9.65   31.48
       2       2
    9.51   31.34
Pier Skew, UpSta & Num, DnSta & Num=  ,4951.5, 2 ,4951.5, 2 , 0 , 0 , 0 ,,
    12.5    12.5
   -6.87   31.45
    12.5    12.5
   -7.01   31.31
Pier Skew, UpSta & Num, DnSta & Num=  ,5068.9, 2 ,5068.9, 2 , 0 , 0 , 0 ,,
    12.5    12.5
      .1   31.39
    12.5    12.5
    -.04   31.25
Abutment Skew #Up #Dn= , 2 , 2
  4809.9  4814.5
   30.58   15.64
  4809.9  4814.5
   30.44    15.5
BR Coef= 1 , 1 , 0 ,1.25, 0 ,,,0.8,0,2,0,
WSPro=,,,, 1 ,,,, 0 ,,,, 0 ,,,,-1 ,-1 ,-1 , 0 , 0 , 0 , 0 , 0
BR U #Sta/Elev= 79
  3229.7   53.56  3239.7   43.19  3249.7   37.13  4349.7   37.07  4389.7   36.41
  4550.9   36.77  4680.9   37.06  4685.7   37.07  4719.3   36.98  4724.9   36.96
  4766.6   37.09  4768.9    37.1    4792   37.13  4792.4   37.82 4798.09   37.89
  4798.2   37.89 4798.31   37.89  4798.9    37.9  4799.8   37.31  4801.4   36.26
  4809.9   22.88 4810.01   22.71  4810.1   22.57  4810.2   22.41  4814.4    15.8
  4814.5   15.64  4822.8   14.54  4824.1   16.05  4838.6   14.34  4854.8   13.69
  4869.8   13.02  4886.2   12.52  4901.9   11.85  4916.6   10.69  4924.3   10.38
  4936.1    2.77  4939.3    -.03  4947.4   -4.34  4951.5   -3.85  4965.9   -8.51
  4986.5  -12.06  5014.3  -16.74  5019.6  -15.87  5054.6  -10.12 5060.39    -.47
  5060.5    -.28 5060.61     -.1  5060.7     .05  5063.7    1.67  5063.8     3.1
  5068.9    7.35  5069.6     7.9  5074.1    9.97  5076.5    10.5 5076.59   10.52
  5076.7   10.54  5080.6    11.4  5080.8   11.45  5092.3   13.98  5108.3   15.36
  5123.3   16.14  5140.7   37.19  5197.7   36.57  5206.7   36.08  5206.8   36.07
  5223.6   35.15  5283.6   37.18    5299   36.88    5309   36.68    5319   36.49
  5353.6   35.81  5455.1   35.63  5609.6   35.36  5679.6   39.14  5736.7   39.47
  5756.7    39.2  5806.7   40.27  5906.7   40.03  6007.9    43.5
BR U #Mann= 4
  3229.7      .2  4799.8     .08  4924.3     .04  5069.6      .2
BR U Banks=4924.3,5069.6
BR D #Sta/Elev= 79
  3229.7   53.42  3239.7   43.05  3249.7   36.99  4349.7   36.93  4389.7   36.27
  4550.9   36.63  4680.9   36.92  4685.7   36.93  4719.3   36.84  4724.9   36.82
  4766.6   36.95  4768.9   36.96    4792   36.99  4792.4   37.68 4798.09   37.75
  4798.2   37.75 4798.31   37.75  4798.9   37.76  4799.8   37.17  4801.4   36.12
  4809.9   22.74 4810.01   22.57  4810.1   22.43  4810.2   22.27  4814.4   15.66
  4814.5    15.5  4822.8    14.4  4824.1   15.91  4838.6    14.2  4854.8   13.55
  4869.8   12.88  4886.2   12.38  4901.9   11.71  4916.6   10.55  4924.3   10.24
  4936.1    2.63  4939.3    -.17  4947.4   -4.48  4951.5   -3.99  4965.9   -8.65
  4986.5   -12.2  5014.3  -16.88  5019.6  -16.01  5054.6  -10.26 5060.39    -.61
  5060.5    -.42 5060.61    -.24  5060.7    -.09  5063.7    1.53  5063.8    2.96
  5068.9    7.21  5069.6    7.76  5074.1    9.83  5076.5   10.36 5076.59   10.38
  5076.7    10.4  5080.6   11.26  5080.8   11.31  5092.3   13.84  5108.3   15.22
  5123.3      16  5140.7   37.05  5197.7   36.43  5206.7   35.94  5206.8   35.93
  5223.6   35.01  5283.6   37.04    5299   36.74    5309   36.54    5319   36.35
  5353.6   35.67  5455.1   35.49  5609.6   35.22  5679.6      39  5736.7   39.33
  5756.7   39.06  5806.7   40.13  5906.7   39.89  6007.9   43.36
BR D #Mann= 4
  3229.7      .2  4799.8     .08  4924.3     .04  5069.6      .2
BR D Banks=4924.3,5069.6
BC Design=,, 0 ,, 0 ,,,,,,
BC HTab HWMax=53.82
BC Use User HTab Curves=0
BC User HTab FreeFlow(D)= 0

Type RM Length L Ch R = 1 ,-643.5  ,231.2,231.2,231.2
BEGIN DESCRIPTION:
Downstream Section of Bridge/Culvert/Weir
Buffalo Bayou Section 109350.2
END DESCRIPTION:
XS GIS Cut Line= 6
      3124480.37      13844682.3      3124223.67       13843977.
      3123975.19     13842988.46      3123886.11     13842813.87
      3123635.94     13842465.59      3123337.88     13842225.69
#Sta/Elev= 30
  3229.7   53.41  3239.7   43.04  3249.7   36.98  4799.8   37.16  4801.4   36.11
  4814.5   15.49  4822.8   14.39  4824.1    15.9  4838.6   14.19  4924.3   10.23
  4947.4   -4.49  4951.5      -4  4965.9   -8.66  5014.3  -16.89  5054.6  -10.27
  5060.7     -.1  5063.7    1.52  5063.8    2.95  5069.6    7.75  5074.1    9.82
  5092.3   13.83  5123.3   15.99  5140.7   37.04  5223.6      35  5283.6   37.03
  5353.6   35.66  5609.6   35.21  5679.6   38.99  5906.7   39.88  6007.9   43.35
#Mann= 4 , 1 , 0
  3229.7      .2       0  4799.8     .08       0  4924.3     .04       0
  5069.6      .2       0
#XS Ineff= 2 , 0
       0    4800    38.9    5140       0    37.3
Permanent Ineff=
       F       F
Bank Sta=4924.3,5069.6
XS Rating Curve= 0 ,0
Exp/Cntr=0.5,0.3