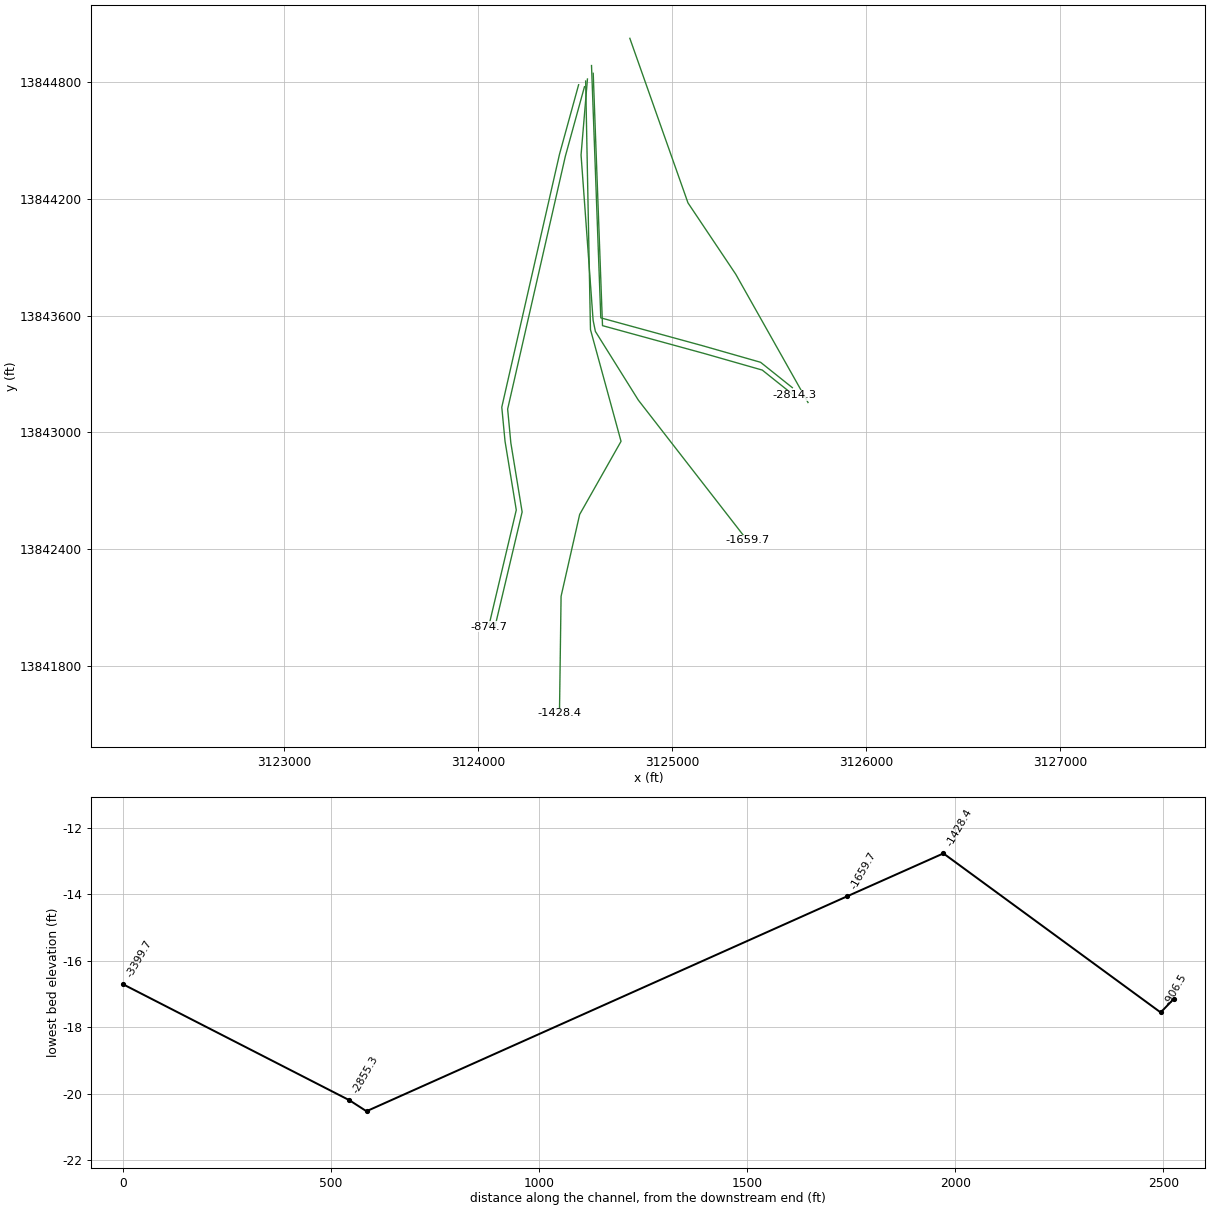
HEC-RAS study E100-00-00.prj: E100-00-00

--- E100-00-00.g01 (geometry) --- (continued)

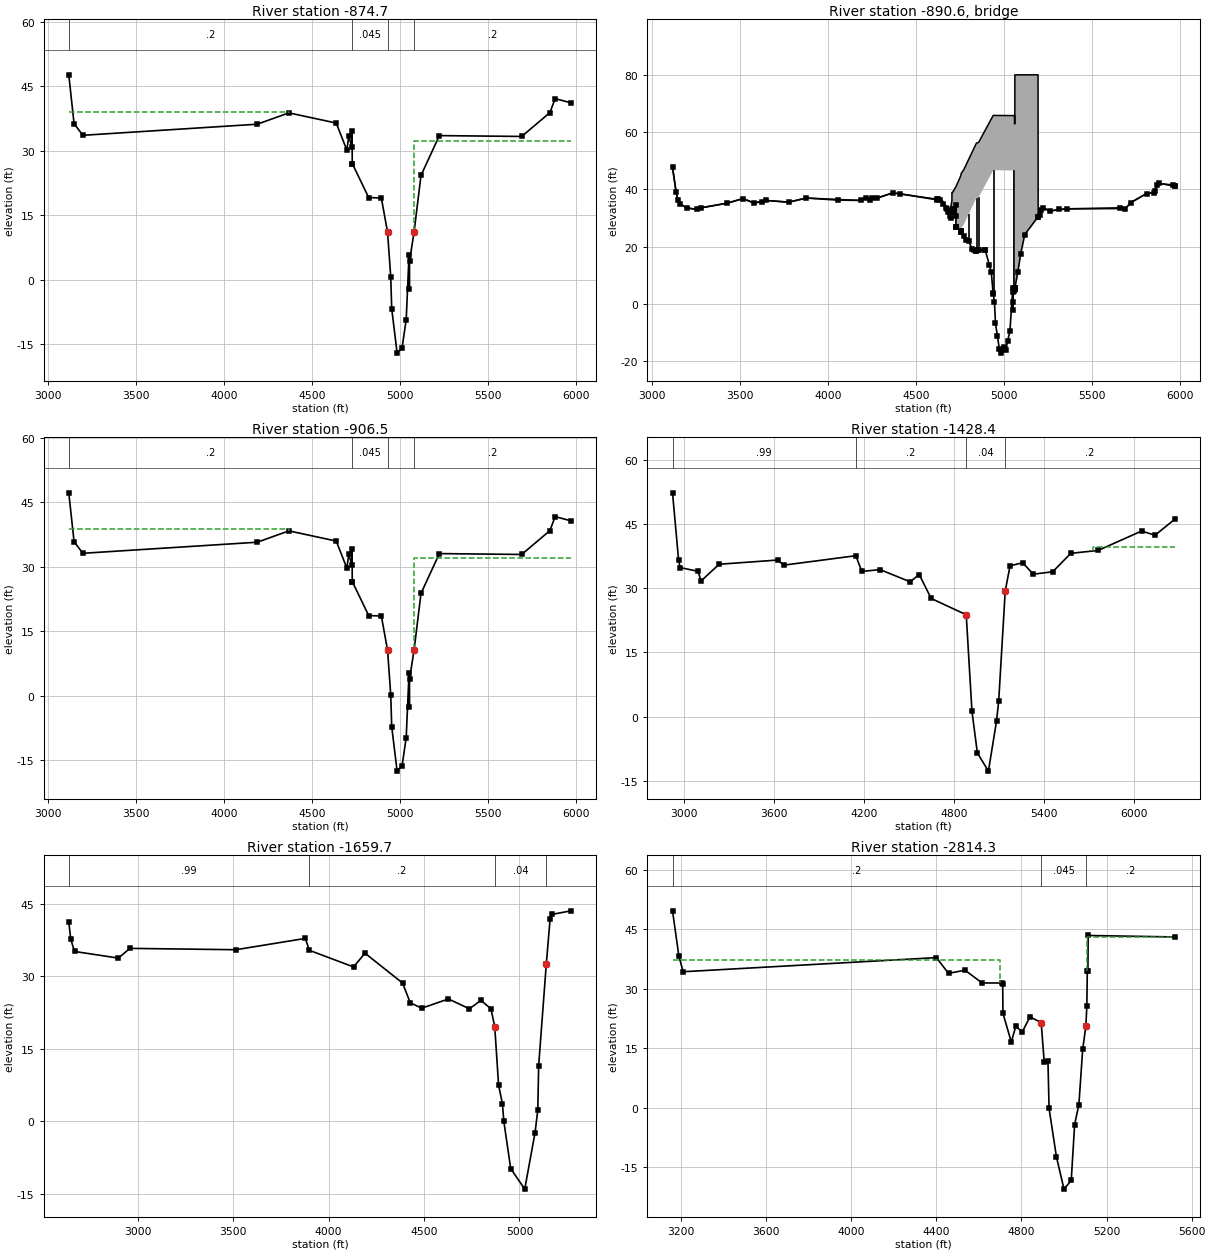
Type RM Length L Ch R = 1 ,-874.7  ,31.8,31.8,31.8
BEGIN DESCRIPTION:
Upstream Section of Bridge/Culvert/Weir
Buffalo Bayou Section 109119.0
END DESCRIPTION:
XS GIS Cut Line= 6
      3124517.92     13844785.64       3124419.4     13844428.76
      3124121.89     13843129.16      3124138.47     13842955.03
      3124196.59     13842600.66      3124054.41     13842002.09
#Sta/Elev= 30
  3118.6   47.66  3148.6   36.29  3198.6   33.58  4188.6   36.16  4368.6    38.8
  4637.5   36.43  4697.5   30.15 4709.02   33.33 4726.86   30.75 4727.47   34.54
 4728.42      27  4728.9   26.97 4821.69   19.09 4893.66   18.97  4928.9   11.03
    4947     .61 4952.46   -6.79  4983.2  -17.14 5011.34  -15.88 5034.73   -9.36
 5050.83    5.64 5052.74   -2.13 5053.78    4.29 5079.59   11.08 5118.73   24.24
  5223.2   33.51  5690.6   33.31  5850.6   38.85  5880.6   42.12  5971.3   41.13
#Mann= 4 , 1 , 0
  3118.6      .2       0  4728.9    .045       0  4928.9     .04       0
 5079.59      .2       0
#XS Ineff= 2 , 0
       0    4370    38.9    5080       0    32.2
Permanent Ineff=
       F       F
Bank Sta=4928.9,5079.59
XS Rating Curve= 0 ,0
Exp/Cntr=0.5,0.3

Type RM Length L Ch R = 3 ,-890.6  ,,,
BEGIN DESCRIPTION:
CROSSWALK - 30 Degree Skew Buffalo Bayou
Structure ID: WOO-17
END DESCRIPTION:
Bridge Culvert--1,0,-1,-1, 0
Deck Dist Width WeirC Skew NumUp NumDn MinLoCord MaxHiCord MaxSubmerge Is_Ogee
10,11.8,2.6,0, 60, 60, , , 0.95, 0, 1,1,,
  3118.6  3138.6  3148.6  3158.6  3198.6  3258.6  3278.6  3428.6  3518.6  3578.6
  3648.6  3778.6  3878.6  4188.6  4218.6  4238.6  4248.6  4278.6  4368.6  4637.5
  4653.3  4677.5  4693.3  4697.5 4705.18 4705.29 4709.02 4726.86 4727.47 4728.42
 4756.04 4757.78 4772.76 4844.55 4856.24 4939.73 5060.61 5060.72 5062.23 5062.34
 5062.53 5062.61 5079.59 5095.26 5118.73 5194.24 5195.11  5203.2  5213.2  5223.2
  5263.2  5360.6  5690.6  5720.6  5810.6  5850.6  5860.6  5870.6  5880.6  5971.3
   47.65   39.22   36.28   35.01   33.57   32.99   33.55   35.19    36.8    35.3
   36.15   35.55   36.99   36.15    36.9   36.44   37.17   36.93   38.79   36.43
    35.9   33.51    31.8    33.3   36.04   38.94   38.94   40.81   40.88   40.99
   44.84   45.57   46.92    56.2   56.35   65.83   65.76   62.86   62.86   62.86
   62.87      80      80      80      80      80    32.5   31.16   32.66    33.5
   32.46   33.22    33.3   35.39   38.55   38.84   39.42   41.57   42.11   41.12
   47.65   39.22   36.28   35.01   33.57   32.99   33.55   35.19    36.8    35.3
   36.15   35.55   36.99   36.15    36.9   36.44   37.17   36.93   38.79   36.42
   35.07   32.99   30.74   30.14   32.26   32.29   33.32   30.74   34.53   26.99
    25.4   26.43   27.78   37.06   37.21   46.69   46.62   46.62   46.62    5.52
    5.58     5.6   11.07   17.32   24.23   30.42    30.5   31.16   32.66    33.5
   32.46   33.22    33.3   35.39   38.55   38.84   39.42   41.57   42.11   41.12
  3118.6  3138.6  3148.6  3158.6  3198.6  3258.6  3278.6  3428.6  3518.6  3578.6
  3648.6  3778.6  3878.6  4188.6  4218.6  4238.6  4248.6  4278.6  4368.6  4637.5
  4653.3  4677.5  4693.3  4697.5 4705.18 4705.29 4709.02 4726.86 4727.47 4728.42
 4756.04 4757.78 4772.76 4844.55 4856.24 4939.73 5060.61 5060.72 5062.23 5062.34
 5062.53 5062.61 5079.59 5095.26 5118.73 5194.24 5195.11  5203.2  5213.2  5223.2
  5263.2  5360.6  5690.6  5720.6  5810.6  5850.6  5860.6  5870.6  5880.6  5971.3
   47.65   39.22   36.28   35.01   33.57   32.99   33.55   35.19    36.8    35.3
   36.15   35.55   36.99   36.15    36.9   36.44   37.17   36.93   38.79   36.43
    35.9   33.51    31.8    33.3   36.04   38.94   38.94   40.81   40.88   40.99
   44.84   45.57   46.92    56.2   56.35   65.83   65.76   62.86   62.86   62.86
   62.87      80      80      80      80      80    32.5   31.16   32.66    33.5
   32.46   33.22    33.3   35.39   38.55   38.84   39.42   41.57   42.11   41.12
   47.16   38.73   35.79   34.52   33.08    32.5   33.06    34.7   36.31   34.81
   35.66   35.06    36.5   35.66   36.41   35.95   36.68   36.44    38.3   35.93
   34.58    32.5   30.25   29.65   31.77    31.8   32.83   30.25   34.04    26.5
   24.91   25.94   27.29   36.57   36.72    46.2   46.13   46.13   46.13    5.03
    5.09    5.11   10.58   16.83   23.74   29.93   30.01   30.67   32.17   33.01
   31.97   32.73   32.81    34.9   38.06   38.35   38.93   41.08   41.62   40.63
Pier Skew, UpSta & Num, DnSta & Num=  ,4800.2, 2 ,4800.2, 2 , 0 , 0 , 0 ,,
     3.5     3.5
   20.65   32.56
     3.5     3.5
   20.16   32.07
Pier Skew, UpSta & Num, DnSta & Num=  ,4843.7, 2 ,4843.7, 2 , 0 , 0 , 0 ,,
     3.5     3.5
   17.64   38.07
     3.5     3.5
   17.15   37.58
Pier Skew, UpSta & Num, DnSta & Num=  ,4855.7, 2 ,4855.7, 2 , 0 , 0 , 0 ,,
     3.5     3.5
   17.74   38.35
     3.5     3.5
   17.25   37.86
Pier Skew, UpSta & Num, DnSta & Num=  ,4939, 2 ,4939, 2 , 0 , 0 , 0 ,,
       6       6
    1.68   47.68
       6       6
    1.19   47.19
Pier Skew, UpSta & Num, DnSta & Num=  ,5050.8, 2 ,5050.8, 2 , 0 , 0 , 0 ,,
       3       3
   -1.49    47.6
       3       3
   -1.98   47.11
Pier Skew, UpSta & Num, DnSta & Num=  ,5055.1, 2 ,5055.1, 2 , 0 , 0 , 0 ,,
       5       5
   -2.48   47.61
       5       5
   -2.97   47.12
Abutment Skew #Up #Dn= , 2 , 2
  5061.4 5062.43
    5.21   46.62
  5061.4 5062.43
    4.72   46.13
BR Coef= 1 , 1 , 0 ,1.25, 0 ,,,0.8,0,2,1,
WSPro=,,,, 1 ,,,, 0 ,,,, 0 ,,,,-1 ,-1 ,-1 , 0 , 0 , 0 , 0 , 0
BR U #Sta/Elev= 112
  3118.6   47.65  3138.6   39.22  3148.6   36.28  3158.6   35.01  3198.6   33.57
  3258.6   32.99  3278.6   33.55  3428.6   35.19  3518.6    36.8  3578.6    35.3
  3628.6   35.63  3648.6   36.15  3778.6   35.55  3878.6   36.99  4058.6   36.26
  4188.6   36.15  4218.6    36.9  4238.6   36.44  4248.6   37.17  4278.6   36.93
  4368.6   38.79  4408.4   38.49  4618.4   36.39  4623.3   36.49  4627.5   36.57
  4637.5   36.42  4653.3   35.07  4673.3   33.35  4677.5   32.99  4683.3   32.16
  4693.3   30.74  4697.5   30.14 4705.18   32.26 4705.29   32.29  4705.4   32.32
 4709.02   33.32 4710.32   33.13 4726.86   30.74 4727.47   34.53 4728.42   26.99
  4728.9   26.96 4731.11   26.84 4755.79   25.41 4756.04    25.4 4756.13    25.4
 4756.47   25.38 4756.57   25.37 4757.78   25.25 4757.87   25.24 4772.76   23.81
 4786.36    22.5 4800.21   21.88 4821.69   19.08 4832.26   18.86 4843.77   18.62
 4844.55   18.63 4855.72   18.76 4856.24   18.76  4893.4   18.96 4893.66   18.96
 4918.51   13.48  4928.9   11.02 4939.03    3.93 4939.73    3.64    4947      .6
 4952.46    -6.8 4963.63  -11.12 4974.19  -15.65  4983.2  -17.15 4991.95  -16.05
 5000.95  -14.87 5009.44   -15.7 5011.34  -15.89    5022  -12.88 5034.73   -9.37
 5050.83    5.63 5052.74   -2.14 5052.91     .56 5053.78    4.28 5055.08     4.4
  5060.5    5.06 5060.61    5.08 5060.72    5.09  5061.2    5.15  5061.3    5.18
 5062.23    5.48 5062.34    5.52 5062.44    5.55 5062.53    5.58 5062.61     5.6
 5079.59   11.07 5095.26   17.32 5118.73   24.23 5194.24   30.42 5195.11    30.5
  5203.2   31.16  5213.2   32.66  5223.2    33.5  5263.2   32.46  5313.2   33.05
  5360.6   33.22  5660.6   33.56  5690.6    33.3  5720.6   35.39  5810.6   38.55
  5850.6   38.84  5860.6   39.42  5870.6   41.57  5880.6   42.11  5960.6   41.52
  5970.6   41.16  5971.3   41.12
BR U #Mann= 4
  3118.6      .2  4728.9    .045  4928.9     .04 5079.59      .2
BR U Banks=4928.9,5079.59
BR D #Sta/Elev= 112
  3118.6   47.16  3138.6   38.73  3148.6   35.79  3158.6   34.52  3198.6   33.08
  3258.6    32.5  3278.6   33.06  3428.6    34.7  3518.6   36.31  3578.6   34.81
  3628.6   35.14  3648.6   35.66  3778.6   35.06  3878.6    36.5  4058.6   35.77
  4188.6   35.66  4218.6   36.41  4238.6   35.95  4248.6   36.68  4278.6   36.44
  4368.6    38.3  4408.4      38  4618.4    35.9  4623.3      36  4627.5   36.08
  4637.5   35.93  4653.3   34.58  4673.3   32.86  4677.5    32.5  4683.3   31.67
  4693.3   30.25  4697.5   29.65 4705.18   31.77 4705.29    31.8  4705.4   31.83
 4709.02   32.83 4710.32   32.64 4726.86   30.25 4727.47   34.04 4728.42    26.5
  4728.9   26.47 4731.11   26.35 4755.79   24.92 4756.04   24.91 4756.13   24.91
 4756.47   24.89 4756.57   24.88 4757.78   24.76 4757.87   24.75 4772.76   23.32
 4786.36   22.01 4800.21   21.39 4821.69   18.59 4832.26   18.37 4843.77   18.13
 4844.55   18.14 4855.72   18.27 4856.24   18.27  4893.4   18.47 4893.66   18.47
 4918.51   12.99  4928.9   10.53 4939.03    3.44 4939.73    3.15    4947     .11
 4952.46   -7.29 4963.63  -11.61 4974.19  -16.14  4983.2  -17.64 4991.95  -16.54
 5000.95  -15.36 5009.44  -16.19 5011.34  -16.38    5022  -13.37 5034.73   -9.86
 5050.83    5.14 5052.74   -2.63 5052.91     .07 5053.78    3.79 5055.08    3.91
  5060.5    4.57 5060.61    4.59 5060.72     4.6  5061.2    4.66  5061.3    4.69
 5062.23    4.99 5062.34    5.03 5062.44    5.06 5062.53    5.09 5062.61    5.11
 5079.59   10.58 5095.26   16.83 5118.73   23.74 5194.24   29.93 5195.11   30.01
  5203.2   30.67  5213.2   32.17  5223.2   33.01  5263.2   31.97  5313.2   32.56
  5360.6   32.73  5660.6   33.07  5690.6   32.81  5720.6    34.9  5810.6   38.06
  5850.6   38.35  5860.6   38.93  5870.6   41.08  5880.6   41.62  5960.6   41.03
  5970.6   40.67  5971.3   40.63
BR D #Mann= 4
  3118.6      .2  4728.9    .045  4928.9     .04 5079.59      .2
BR D Banks=4928.9,5079.59
BC Design=,, 0 ,, 0 ,,,,,,
BC HTab HWMax=47.66
BC Use User HTab Curves=0
BC User HTab FreeFlow(D)= 0

Type RM Length L Ch R = 1 ,-906.5  ,521.9,521.9,521.9
BEGIN DESCRIPTION:
Downstream Section of Bridge/Culvert/Weir
Buffalo Bayou Section 109087.2
END DESCRIPTION:
XS GIS Cut Line= 6
      3124548.09      13844775.6      3124449.58     13844418.72
      3124152.07     13843119.12      3124168.65     13842944.99
      3124226.77     13842590.62      3124084.58     13841992.04
#Sta/Elev= 30
  3118.6   47.25  3148.6   35.88  3198.6   33.17  4188.6   35.75  4368.6   38.39
  4637.5   36.02  4697.5   29.74 4709.02   32.92 4726.86   30.34 4727.47   34.13
 4728.42   26.59  4728.9   26.56 4821.69   18.68 4893.66   18.56  4928.9   10.62
    4947      .2 4952.46    -7.2  4983.2  -17.55 5011.34  -16.29 5034.73   -9.77
 5050.83    5.23 5052.74   -2.54 5053.78    3.88 5079.59   10.67 5118.73   23.83
  5223.2    33.1  5690.6    32.9  5850.6   38.44  5880.6   41.71  5971.3   40.72
#Mann= 4 , 1 , 0
  3118.6      .2       0  4728.9    .045       0  4928.9     .04       0
 5079.59      .2       0
#XS Ineff= 2 , 0
       0    4370    38.9    5080       0      32
Permanent Ineff=
       F       F
Bank Sta=4928.9,5079.59
XS Rating Curve= 0 ,0
Exp/Cntr=0.5,0.3

Type RM Length L Ch R = 1 ,-1428.4 ,213.6,231.3,730.5
BEGIN DESCRIPTION:
Buffalo Bayou Section 108565.3
END DESCRIPTION:
XS GIS Cut Line= 6
      3124554.12     13844804.36      3124578.87     13843527.83
      3124736.44     13842953.51       3124523.2     13842577.91
      3124427.46     13842157.49      3124419.13     13841555.99
#Sta/Elev= 30
  2925.1   52.37  2965.1   36.74  2975.1   34.88  3095.1      34  3115.1   31.74
  3235.1   35.65  3625.1   36.64  3665.1   35.44  4145.1   37.65  4185.1   33.97
  4306.4    34.4  4506.9   31.54  4566.9   33.25  4646.9   27.64  4880.1   23.83
  4918.2    1.24  4954.1   -8.51  5027.7  -12.77  5081.7   -1.06  5096.1    3.59
  5139.7    29.4  5171.6   35.28    5256   36.01    5326   33.32    5456    33.9
    5576   38.21  5757.2   38.88  6047.2   43.42  6137.2   42.45  6268.8   46.21
#Mann= 4 , 1 , 0
  2925.1     .99       0  4145.1      .2       0  4880.1     .04       0
  5139.7      .2       0
#XS Ineff= 2 , 0
       0                    5725       0   39.75
Permanent Ineff=
       F       F
Bank Sta=4880.1,5139.7
XS Rating Curve= 0 ,0
Exp/Cntr=0.3,0.1

Type RM Length L Ch R = 1 ,-1659.7 ,378.4,1154.6,832.3
BEGIN DESCRIPTION:
Cross Section 108334.0-Interpolated
Buffalo Bayou Section 108334.0
END DESCRIPTION:
XS GIS Cut Line= 6
       3124563.3     13844814.93       3124530.4     13844424.84
      3124592.56      13843575.3      3124604.22     13843518.31
      3124825.67      13843165.1      3125386.75     13842445.23
#Sta/Elev= 30
  2639.4   41.25  2649.4    37.7  2669.4   35.12  2899.4   33.75  2959.4   35.76
  3514.6   35.48  3878.5   37.82  3899.4   35.36    4131   31.92    4191   34.76
  4387.9   28.58  4427.9   24.51  4487.9   23.38  4627.9   25.29  4737.9   23.26
  4797.9   24.99  4850.6   23.27  4870.6   19.55  4890.6     7.5  4910.6    3.64
  4918.2    -.05  4954.1    -9.8  5027.7  -14.06  5081.7   -2.35  5096.1     2.3
  5100.6    11.5  5140.6   32.52  5160.6   41.91  5170.6    42.8  5270.6   43.53
#Mann= 4 , 1 , 0
  2639.4     .99       0  3899.4      .2       0  4870.6     .04       0
  5140.6      .1       0
Bank Sta=4870.6,5140.6
XS Rating Curve= 0 ,0
Exp/Cntr=0.5,0.3

Type RM Length L Ch R = 1 ,-2814.3 ,41,41,41
BEGIN DESCRIPTION:
Upstream Section of Bridge/Culvert/Weir
Buffalo Bayou Section 107179.4
END DESCRIPTION:
XS GIS Cut Line= 5
      3124593.07     13844844.16      3124640.89     13843547.89
      3125164.29     13843405.03      3125464.17     13843319.65
      3125627.95     13843189.32
#Sta/Elev= 30
  3160.3   49.66  3190.3   38.16  3210.3    34.3  4400.3   37.86  4457.3   33.89
  4534.9   34.69  4614.9   31.47  4708.6   31.46  4711.9   31.21  4713.3   23.79
  4752.4   16.57  4773.3   20.52  4804.2   19.15  4840.2   22.94  4892.8   21.46
  4907.1   11.59  4924.7   11.72  4929.9    -.16  4964.3  -12.32    5000  -20.52
  5034.1  -18.34    5050   -4.24    5070     .77    5088   14.78  5102.9   20.62
  5107.5    25.7  5109.5   34.46  5112.4   34.49  5113.7   43.44  5521.1   43.07
#Mann= 3 , 1 , 0
  3160.3      .2       0  4892.8    .045       0  5102.9      .2       0
#XS Ineff= 2 , 0
       0    4700    37.2    5110       0      43
Permanent Ineff=
       F       F
Bank Sta=4892.8,5102.9
XS Rating Curve= 0 ,0
Exp/Cntr=0.5,0.3

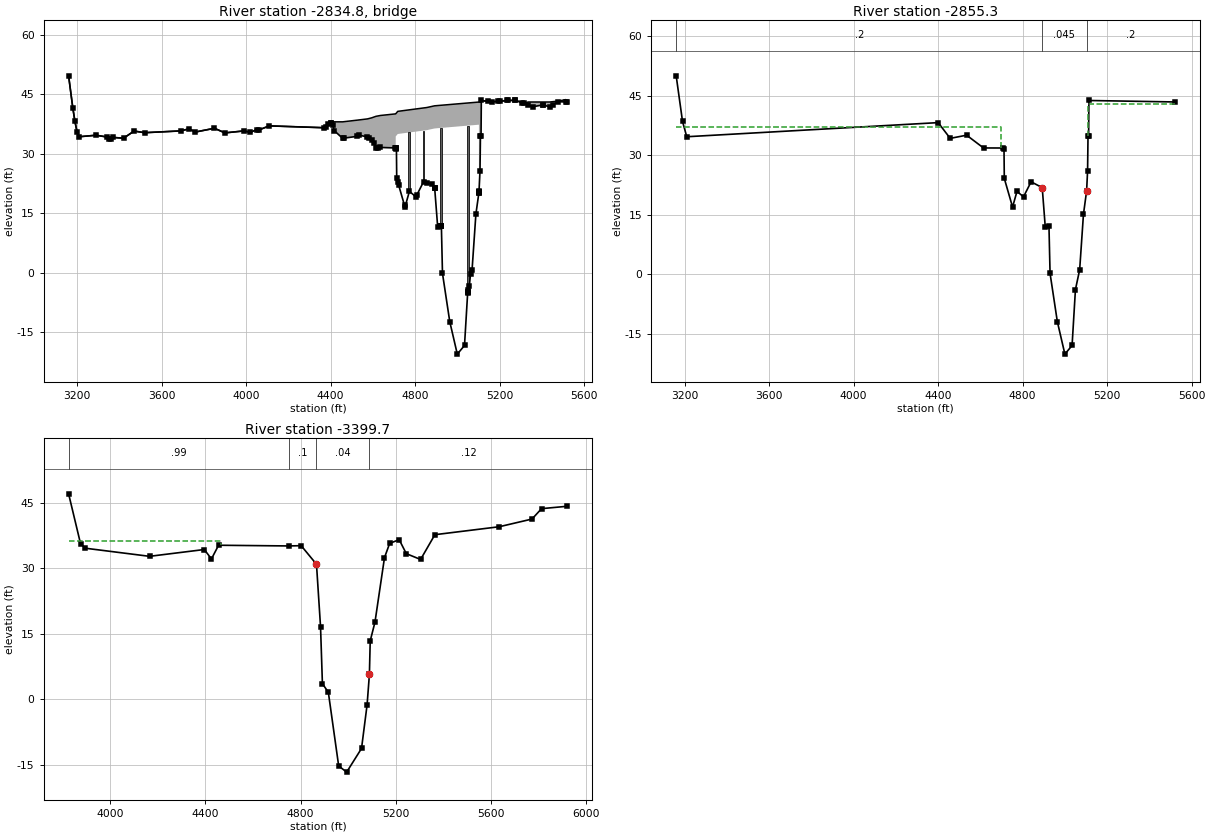
Type RM Length L Ch R = 3 ,-2834.8 ,,,
BEGIN DESCRIPTION:
SOUTHERN PACIFIC RAILROAD Buffalo Bayou
Structure ID: W00-16A
END DESCRIPTION:
Bridge Culvert--1,0,-1,-1, 0
Deck Dist Width WeirC Skew NumUp NumDn MinLoCord MaxHiCord MaxSubmerge Is_Ogee
10,21,2.6,0, 60, 60, , , 0.95, 0, 1,1,,
  3160.3  3180.3  3190.3  3200.3  3210.3  3290.3  3340.3  3350.3  3360.3  3370.3
  3420.3  3470.3  3520.3  3690.3  3730.3  3760.3  3850.3  3900.3  3990.3  4020.3
  4050.3  4060.3  4110.3  4370.3  4380.3  4390.3  4400.3  4403.4  4410.3  4417.3
  4457.3  4527.3  4534.9  4574.9  4594.9  4604.9  4614.9  4635.9 4708.51  4708.6
  4718.1  4855.9  4892.8 5102.39  5102.5  5102.8  5107.5  5109.5  5112.4  5113.7
  5162.2  5274.3    5315    5335  5357.4  5407.4  5437.4  5477.4  5512.7  5521.1
    49.6   41.46    38.1   35.44   34.24   34.62   34.19   33.66   33.64   34.07
   33.87   35.67   35.26   35.71   36.22   35.43   36.37   35.21   35.71   35.36
   36.01   35.94   36.98   36.51   36.77   37.49    37.8      38      38      38
      38   38.43   38.48   38.74   39.01    39.2   39.39    39.6   40.01   40.02
   40.64   41.61   42.04   42.99   42.99   42.99   42.96   42.95   42.94   43.39
   43.05   43.45   42.65      43      43      43      43   43.23    43.6   43.01
    49.6   41.46    38.1   35.44   34.24   34.62   34.19   33.66   33.64   34.07
   33.87   35.67   35.26   35.71   36.22   35.43   36.37   35.21   35.71   35.36
   36.01   35.94   36.98   36.51   36.77   37.49    37.8   37.63   37.24   35.79
   33.83   34.35   34.63    34.2   33.44   32.64   31.41   31.54    31.4   34.31
   34.93    35.9   36.33   37.28   20.25   20.36   25.64    34.4   34.43   43.38
   43.04   43.44   42.64   42.24    41.8   42.28   41.73   43.06   43.02   43.01
  3160.3  3180.3  3190.3  3200.3  3210.3  3290.3  3340.3  3350.3  3360.3  3370.3
  3420.3  3470.3  3520.3  3690.3  3730.3  3760.3  3850.3  3900.3  3990.3  4020.3
  4050.3  4060.3  4110.3  4370.3  4380.3  4390.3  4400.3  4410.3  4417.3  4457.3
  4527.3  4534.9  4574.9  4594.9  4604.9  4614.9  4635.9 4708.51  4708.6  4718.1
  4855.9  4892.8 5102.39  5102.5  5102.8  5102.9  5107.5  5109.5  5112.4  5113.7
  5162.2  5274.3    5315  5357.4  5407.4  5437.4    5455  5477.4  5512.7  5521.1
   49.92   41.78   38.42   35.76   34.56   34.94   34.51   33.98   33.96   34.39
   34.19   35.99   35.58   36.03   36.54   35.75   36.69   35.53   36.03   35.68
   36.33   36.26    37.3   36.83   37.09   37.81   38.12      38      38      38
   38.43   38.48   38.74   39.01    39.2   39.39    39.6   40.01   40.02   40.64
   41.61   42.04   42.99   42.99   42.99   42.99   42.96   42.95   42.94    43.7
   43.36   43.76   42.96      43      43      43      43   43.38    43.6   43.33
   49.92   41.78   38.42   35.76   34.56   34.94   34.51   33.98   33.96   34.39
   34.19   35.99   35.58   36.03   36.54   35.75   36.69   35.53   36.03   35.68
   36.33   36.26    37.3   36.83   37.09   37.81   38.12   37.56   36.11   34.15
   34.67   34.95   34.52   33.76   32.96   31.73   31.86   31.72   34.63   35.25
   36.22   36.65    37.6   20.57   20.68   20.88   25.96   34.72   34.75    43.7
   43.36   43.76   42.96   42.12    42.6   42.05   42.64   43.38   43.34   43.33
Pier Skew, UpSta & Num, DnSta & Num=  ,4773.3, 2 ,4773.3, 2 , 0 , 0 , 0 ,,
       9       9
   18.61   36.41
       9       9
   18.93   36.73
Pier Skew, UpSta & Num, DnSta & Num=  ,4840.2, 2 ,4840.2, 2 , 0 , 0 , 0 ,,
       9       9
   21.41   36.84
       9       9
   21.73   37.16
Pier Skew, UpSta & Num, DnSta & Num=  ,4924.7, 2 ,4924.7, 2 , 0 , 0 , 0 ,,
       9       9
     .38   37.49
       9       9
      .7   37.81
Pier Skew, UpSta & Num, DnSta & Num=  ,5050, 2 ,5050, 2 , 0 , 0 , 0 ,,
       9       9
   -9.29   38.06
       9       9
   -8.97   38.38
Abutment Skew #Up #Dn= , 2 , 2
  4708.4  4722.8
   34.31   21.98
  4708.4  4722.8
   34.63    22.3
BR Coef= 1 , 1 , 0 ,1.25, 0 ,,,0.8,0,2,0,
WSPro=,,,, 1 ,,,, 0 ,,,, 0 ,,,,-1 ,-1 ,-1 , 0 , 0 , 0 , 0 , 0
BR U #Sta/Elev= 107
  3160.3    49.6  3180.3   41.46  3190.3    38.1  3200.3   35.44  3210.3   34.24
  3290.3   34.62  3340.3   34.19  3350.3   33.66  3360.3   33.64  3370.3   34.07
  3420.3   33.87  3470.3   35.67  3520.3   35.26  3690.3   35.71  3730.3   36.22
  3760.3   35.43  3850.3   36.37  3900.3   35.21  3990.3   35.71  4020.3   35.36
  4050.3   36.01  4060.3   35.94  4110.3   36.98  4370.3   36.51  4380.3   36.77
  4390.3   37.49  4400.3    37.8  4403.4   37.63  4410.3   37.24  4417.3   35.79
  4457.3   33.83  4463.4   33.88  4527.3   34.35  4534.9   34.63  4574.9    34.2
  4583.4   33.88  4594.9   33.44  4604.9   32.64  4614.9   31.41    4623   31.46
  4635.9   31.54  4707.3   31.41  4708.4   31.41 4708.51    31.4  4708.6    31.4
  4711.9   31.15  4713.3   23.73  4718.1   22.84  4722.8   21.98  4752.4   16.51
  4754.8   16.96  4773.3   20.46  4804.2   19.09  4809.6   19.66  4840.2   22.88
  4855.9   22.67  4880.7   22.33  4892.8    21.4  4892.9   21.33    4893   21.26
  4907.1   11.53 4924.29   11.66  4924.4   11.66 4924.51   11.66  4924.7   11.66
  4929.9    -.22  4964.3  -12.38    5000  -20.58  5034.1   -18.4 5049.09   -5.11
  5049.2   -5.01 5049.31   -4.91    5050    -4.3  5056.7   -3.46  5062.7    -.37
    5070     .71    5088   14.72  5102.2   20.13  5102.3   20.17 5102.39    20.2
  5102.5   20.25  5102.6   20.28  5102.8   20.36  5102.9   20.56  5107.5   25.64
  5109.5    34.4  5112.4   34.43  5113.7   43.38    5143   43.17  5162.2   43.04
  5193.3    43.2  5203.1   43.25  5234.6   43.38    5239    43.4    5274   43.44
  5274.3   43.44  5308.1   42.77    5315   42.64    5335   42.24  5357.4    41.8
    5405   42.26  5407.4   42.28  5437.4   41.73    5455   42.32  5477.4   43.06
  5512.7   43.02  5521.1   43.01
BR U #Mann= 3
  3160.3      .2  4892.8    .045  5102.9      .2
BR U Banks=4892.8,5102.9
BR D #Sta/Elev= 107
  3160.3   49.92  3180.3   41.78  3190.3   38.42  3200.3   35.76  3210.3   34.56
  3290.3   34.94  3340.3   34.51  3350.3   33.98  3360.3   33.96  3370.3   34.39
  3420.3   34.19  3470.3   35.99  3520.3   35.58  3690.3   36.03  3730.3   36.54
  3760.3   35.75  3850.3   36.69  3900.3   35.53  3990.3   36.03  4020.3   35.68
  4050.3   36.33  4060.3   36.26  4110.3    37.3  4370.3   36.83  4380.3   37.09
  4390.3   37.81  4400.3   38.12  4403.4   37.95  4410.3   37.56  4417.3   36.11
  4457.3   34.15  4463.4    34.2  4527.3   34.67  4534.9   34.95  4574.9   34.52
  4583.4    34.2  4594.9   33.76  4604.9   32.96  4614.9   31.73    4623   31.78
  4635.9   31.86  4707.3   31.73  4708.4   31.73 4708.51   31.72  4708.6   31.72
  4711.9   31.47  4713.3   24.05  4718.1   23.16  4722.8    22.3  4752.4   16.83
  4754.8   17.28  4773.3   20.78  4804.2   19.41  4809.6   19.98  4840.2    23.2
  4855.9   22.99  4880.7   22.65  4892.8   21.72  4892.9   21.65    4893   21.58
  4907.1   11.85 4924.29   11.98  4924.4   11.98 4924.51   11.98  4924.7   11.98
  4929.9      .1  4964.3  -12.06    5000  -20.26  5034.1  -18.08 5049.09   -4.79
  5049.2   -4.69 5049.31   -4.59    5050   -3.98  5056.7   -3.14  5062.7    -.05
    5070    1.03    5088   15.04  5102.2   20.45  5102.3   20.49 5102.39   20.52
  5102.5   20.57  5102.6    20.6  5102.8   20.68  5102.9   20.88  5107.5   25.96
  5109.5   34.72  5112.4   34.75  5113.7    43.7    5143   43.49  5162.2   43.36
  5193.3   43.52  5203.1   43.57  5234.6    43.7    5239   43.72    5274   43.76
  5274.3   43.76  5308.1   43.09    5315   42.96    5335   42.56  5357.4   42.12
    5405   42.58  5407.4    42.6  5437.4   42.05    5455   42.64  5477.4   43.38
  5512.7   43.34  5521.1   43.33
BR D #Mann= 3
  3160.3      .2  4892.8    .045  5102.9      .2
BR D Banks=4892.8,5102.9
BC Design=,, 0 ,, 0 ,,,,,,
BC HTab HWMax=49.66
BC Use User HTab Curves=0
BC User HTab FreeFlow(D)= 0

Type RM Length L Ch R = 1 ,-2855.3 ,544.4,544.4,544.4
BEGIN DESCRIPTION:
Downstream Section of Bridge/Culvert/Weir
Buffalo Bayou Section 107138.4
END DESCRIPTION:
XS GIS Cut Line= 5
      3124584.29     13844884.21      3124632.11     13843587.93
      3125155.51     13843445.07      3125455.39     13843359.69
      3125619.17     13843229.37
#Sta/Elev= 30
  3160.3   49.99  3190.3   38.49  3210.3   34.63  4400.3   38.19  4457.3   34.22
  4534.9   35.02  4614.9    31.8  4708.6   31.79  4711.9   31.54  4713.3   24.12
  4752.4    16.9  4773.3   20.85  4804.2   19.48  4840.2   23.27  4892.8   21.79
  4907.1   11.92  4924.7   12.05  4929.9     .17  4964.3  -11.99    5000  -20.19
  5034.1  -18.01    5050   -3.91    5070     1.1    5088   15.11  5102.9   20.95
  5107.5   26.03  5109.5   34.79  5112.4   34.82  5113.7   43.77  5521.1    43.4
#Mann= 3 , 1 , 0
  3160.3      .2       0  4892.8    .045       0  5102.9      .2       0
#XS Ineff= 2 , 0
       0    4700    37.2    5110       0      43
Permanent Ineff=
       F       F
Bank Sta=4892.8,5102.9
XS Rating Curve= 0 ,0
Exp/Cntr=0.5,0.3

Type RM Length L Ch R = 1 ,-3399.7 ,492.1,442.6,336.3
BEGIN DESCRIPTION:
Buffalo Bayou Section 106594.0
Cross Section 106594.0-Interpolated
END DESCRIPTION:
XS GIS Cut Line= 4
      3124781.79      13845023.9      3125081.44     13844178.45
      3125327.62     13843811.92      3125699.99     13843153.08
#Sta/Elev= 30
  3825.3   47.11  3875.3   35.71  3895.3   34.64  4165.3   32.78  4395.3   34.34
  4425.3   32.18  4455.3   35.32  4749.7   35.16  4802.3   35.22  4866.6   30.96
  4883.6   16.65  4891.5    3.59  4916.4     1.6  4959.8  -15.28  4993.3   -16.7
  5055.8  -11.27  5079.2   -1.26  5088.9     5.7  5092.3   13.39  5112.3    17.7
  5152.3   32.49  5173.9   35.74  5213.9   36.61  5243.9   33.39  5303.9   32.06
  5363.9   37.74  5633.9   39.56    5772   41.33    5812   43.71  5920.6   44.26
#Mann= 4 , 1 , 0
  3825.3     .99       0  4749.7      .1       0  4866.6     .04       0
  5088.9     .12       0
#XS Ineff= 2 , 0
       0    4465    36.2               0
Permanent Ineff=
       F       F
Bank Sta=4866.6,5088.9
XS Rating Curve= 0 ,0
Exp/Cntr=0.5,0.3